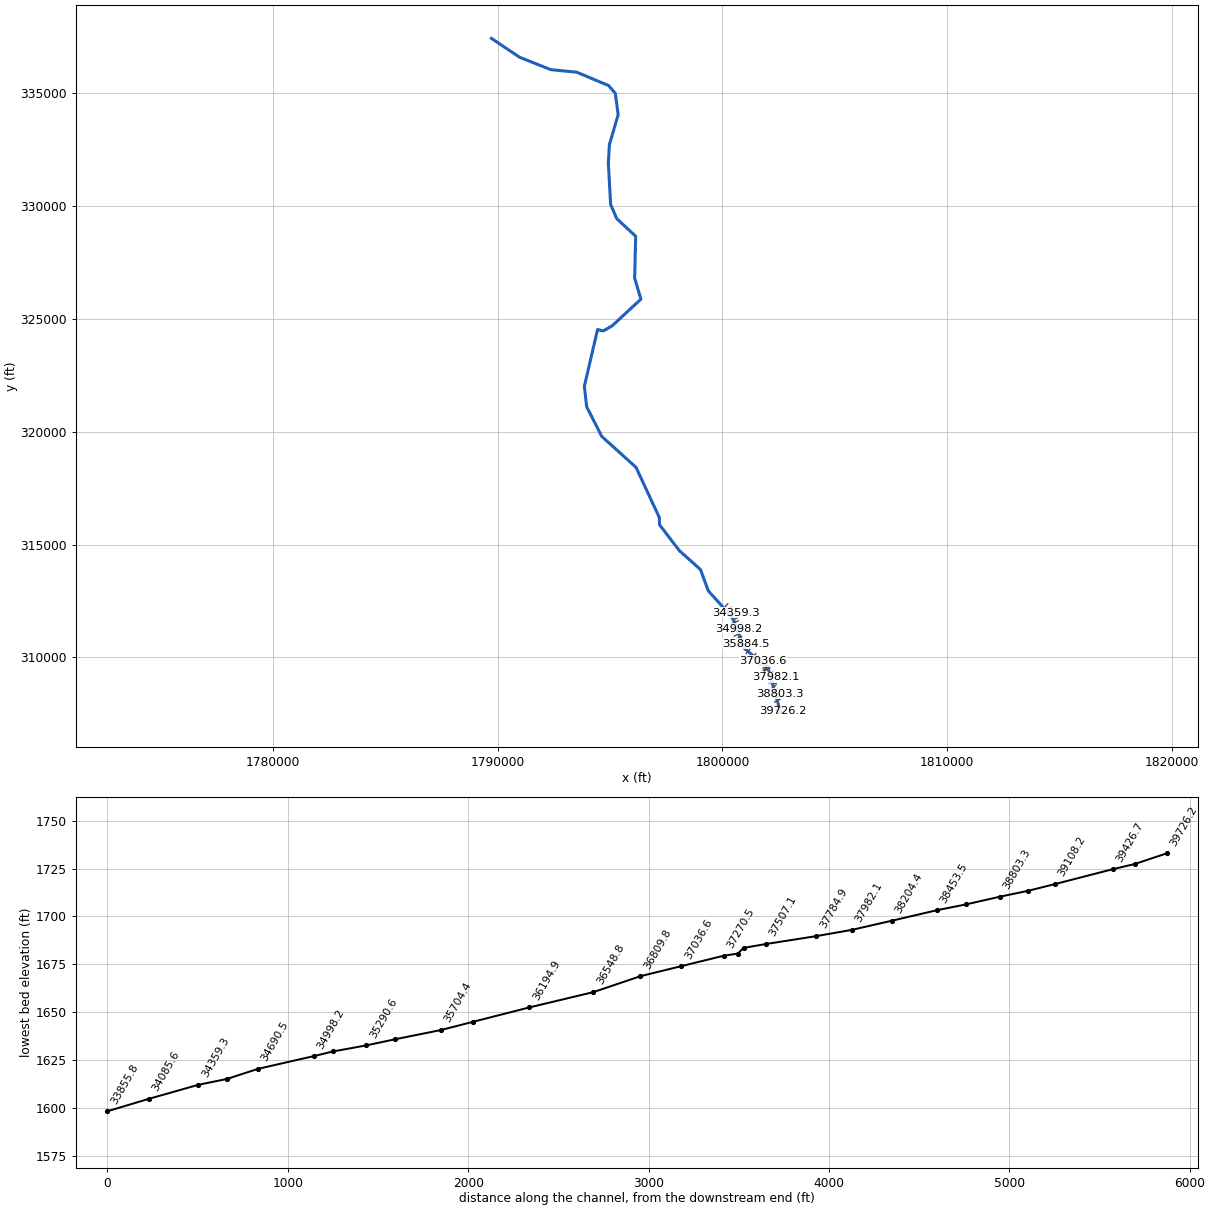
--- WESTFK1.prj (project) ---

Proj Title=WESTFK1
Current Plan=p01
Default Exp/Contr=0,0
English Units
Geom File=g01
Flow File=f01
Plan File=p01
BEGIN DESCRIPTION:
END DESCRIPTION:
DSS Export Rating Curves= 0
DSS Export Rating Curve Sorted= 0
DSS Export Volume Flow Curves= 0
DXF Filename=.\backup\WESTFK1.
DXF OffsetX= 0
DXF OffsetY= 0
DXF ScaleX= 0
DXF ScaleY= 0

--- WESTFK1.p01 (plan) ---

Plan Title=Floodplain
Program Version=4.00
Geom File=g01
Flow File=f01
K Sum by GR=0
Std Step Tol=0.01
Critical Tol=0.01
Num of Std Step Trials=20
Max Error Tol=0.3
Flow Tol Ratio=0.001
Split Flow NTrial=30
Split Flow Tol=0.02
Split Flow Ratio=0.02
Log Output Level=0
Friction Slope Method=1
Unsteady Friction Slope Method=2
Unsteady Bridges Friction Slope Method=1
Global Log Level=0
CheckData=False
Run HTab=0
Run UNet=0
Run PostProcess=0
UNET Theta=0
UNET Theta Warmup=0
UNET ZTol=0
UNET ZSATol=0
UNET MxIter=0
UNET MaxInSteps=0
UNET DtIC=0
UNET DtMin=0
UNET MaxCRTS=0
UNET WFStab=0
UNET SFStab=0
UNET WFX=0
UNET SFX=0
UNET DSS MLevel=0
UNET DZMax Abort=0
UNET Convert EG Bridges=0
UNET Use Existing IB Tables=0
UNET Froude Limit=0
UNET Froude Power=0
Write IC File=0
Echo Input=False
Echo Output=False
Write Detailed=0

--- WESTFK1.f01 (steady flow) ---

Flow Title=NFF Regression Equation
Program Version=4.10
Number of Profiles= 1
Profile Names=P100yr
River Rch & RM=WESTFK1,Main            ,39726.2
886.6804
River Rch & RM=WESTFK1,Main            ,38204.4
944.2891
River Rch & RM=WESTFK1,Main            ,36194.9
1020.136
River Rch & RM=WESTFK1,Main            ,35704.4
1132.273
River Rch & RM=WESTFK1,Main            ,34998.2
1140.191
River Rch & RM=WESTFK1,Main            ,33855.8
1284.695
River Rch & RM=WESTFK1,Main            ,30351.2
1415.719
River Rch & RM=WESTFK1,Main            ,26476.4
1570.939
River Rch & RM=WESTFK1,Main            ,21735.3
1744.345
River Rch & RM=WESTFK1,Main            ,18620.2
1910.887
River Rch & RM=WESTFK1,Main            ,13619.6
2058.458
River Rch & RM=WESTFK1,Main            ,13078.5
2777.084
River Rch & RM=WESTFK1,Main            ,5763.6
3000.087
River Rch & RM=WESTFK1,Main            ,5201
 3747.59
River Rch & RM=WESTFK1,Main            ,1595.7
 3810.69
River Rch & RM=WESTFK1,Main            ,70.1
3973.341
Boundary for River Rch & Prof#=WESTFK1,Main            , 1
Up Type= 0
Dn Type= 1
Dn Known WS=1076.85
DSS Import GetInterval= 0
DSS Import GetPeak= 0
DSS Import FillOption= 0

--- WESTFK1.g01 (geometry) ---

Geom Title=USGS 10m DEM
Program Version=4.10

River Reach=WESTFK1         ,Main
Reach XY= 30
     1802588.321      307568.339     1802029.656       309535.25
     1800974.183      310401.539      1800469.76      311737.507
     1799373.923      312947.373     1799024.794      313893.063
       1798086.6      314729.174     1797203.784      315878.102
     1797194.235      316198.415     1796162.294      318415.979
     1794635.208      319790.776     1793966.805      321097.373
     1793860.902      322005.359     1794448.406      324522.229
     1794703.897      324462.507     1795091.461      324682.646
     1796376.183      325867.368     1796099.231      326793.838
     1796143.177      328654.559     1795304.656      329431.952
      1795030.35      330061.813     1794928.961      331897.924
     1794973.906      332704.906     1795365.399      334039.454
     1795237.795      334988.066     1794941.788      335329.212
     1793523.406      335921.535     1792364.748      336036.026
     1790982.602      336582.228      1789728.62       337421.43

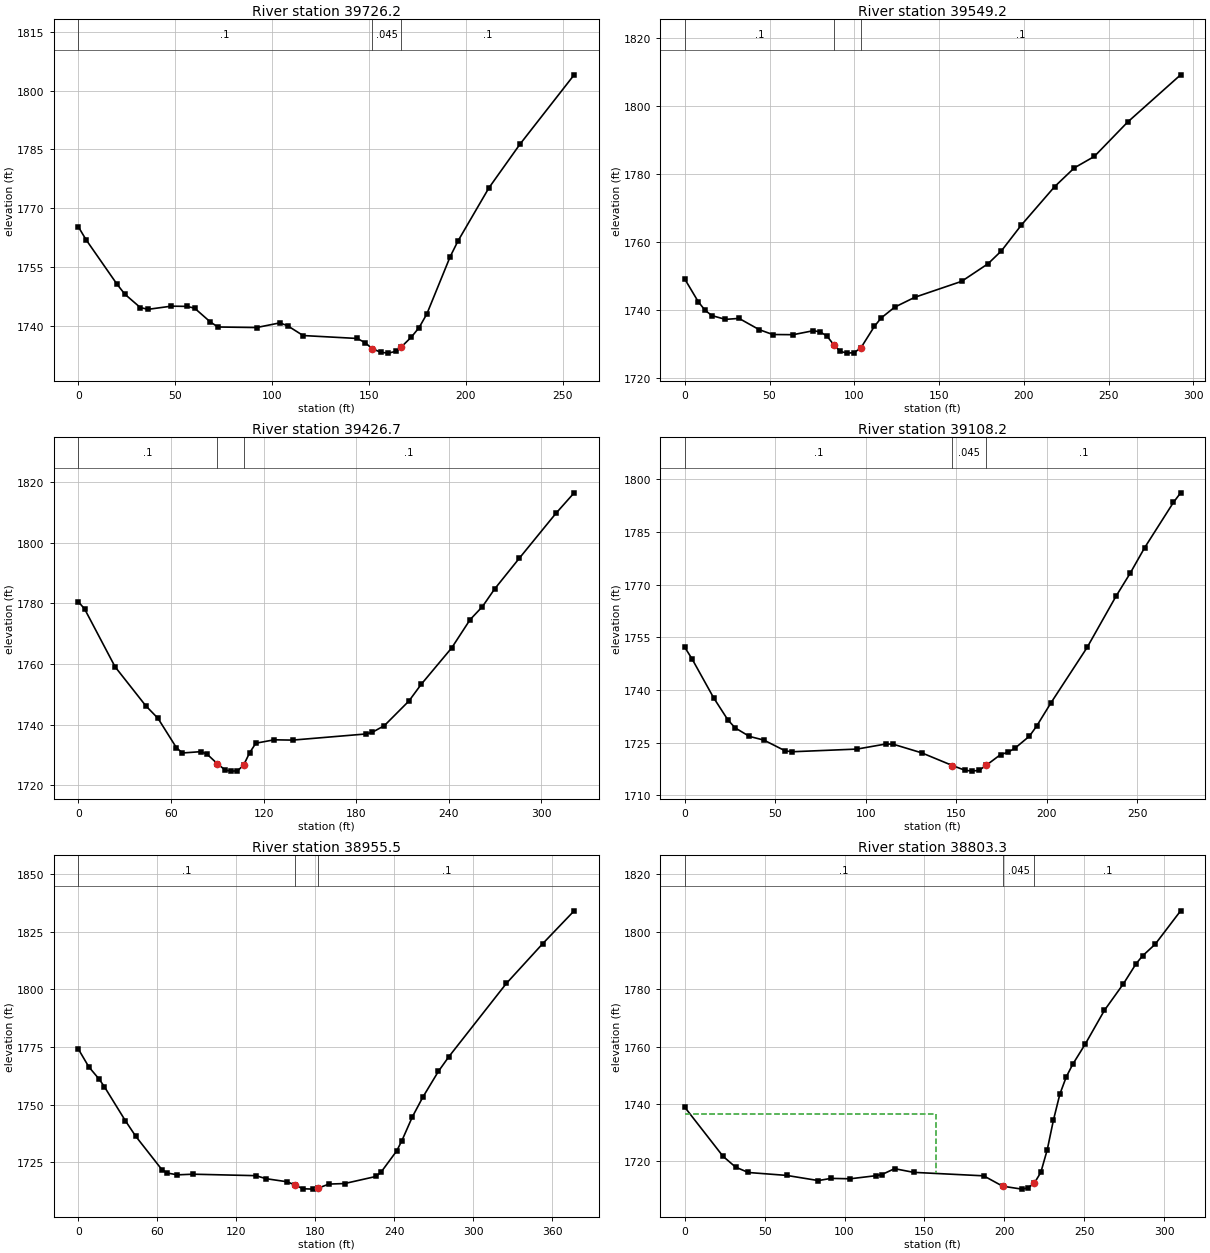
Type RM Length L Ch R = 1 ,39726.2 ,165.9,177,187.1
XS GIS Cut Line= 2
     1802439.255      307522.013      1802677.97      307614.244
#Sta/Elev= 30
       0 1765.22       4 1761.91      20 1750.54      24 1748.02      32  1744.6
      36 1744.15      48 1744.96      56  1744.9      60 1744.45      68 1740.98
      72 1739.64      92  1739.5     104 1740.69     108 1739.96     116 1737.46
     144 1736.71     148 1735.63   151.6 1734.15     156 1733.19     160 1732.97
   163.9 1733.44   166.6  1734.5   171.9 1737.08   175.9 1739.51   179.9    1743
   191.9 1757.58   195.9 1761.56   211.9 1775.15   227.9 1786.28   255.9 1804.01
#Mann= 3 , 0 , 0
       0      .1       0   151.6    .045       0   166.6      .1       0
Bank Sta=151.6,166.6
XS Rating Curve= 0 ,0
Exp/Cntr=0.3,0.1

Type RM Length L Ch R = 1 ,39549.2 ,140.8,122.6,104.2
XS GIS Cut Line= 3
     1802404.533       307632.69     1802498.934      307735.772
     1802649.758      307759.643
#Sta/Elev= 30
       0 1749.18       8 1742.47      12 1739.99      16 1738.44      24 1737.33
      32 1737.62    43.9 1734.31    51.9 1732.88    63.9 1732.83    75.9 1734.01
    79.9 1733.63    83.9 1732.42    88.1 1729.72    91.8 1727.91    95.8 1727.41
    99.8 1727.55   103.8 1728.89   111.8 1735.24   115.8 1737.72   123.8 1740.92
   135.8 1743.85   163.3 1748.51   178.9 1753.69   186.8 1757.48   198.5 1765.03
   218.1 1776.31   229.8 1781.87   241.6 1785.23   261.2 1795.31   292.5 1809.22
#Mann= 3 , 0 , 0
       0      .1       0    88.1    .045       0   103.8      .1       0
Bank Sta=88.1,103.8
XS Rating Curve= 0 ,0
Exp/Cntr=0.3,0.1

Type RM Length L Ch R = 1 ,39426.7 ,305.1,318.5,331.6
XS GIS Cut Line= 2
     1802323.152      307808.471     1802644.333      307814.982
#Sta/Elev= 30
       0 1780.54       4 1778.24    23.8  1759.1    43.6  1746.3    51.6  1742.1
    63.5 1732.45    67.4 1730.67    79.3 1731.11    83.3 1730.33      90 1727.16
    95.2 1725.02    99.2 1724.69   103.1 1724.78   107.1  1726.7     111 1730.78
     115  1733.9   126.9 1735.02   138.8 1734.92   186.4 1736.95   190.4 1737.48
   198.3 1739.72   214.2 1747.84   222.1 1753.31   241.9 1765.36   253.8 1774.66
   261.8 1778.97   269.7 1784.78   285.6 1794.86   309.4 1809.72   321.2 1816.48
#Mann= 3 , 0 , 0
       0      .1       0      90    .045       0   107.1      .1       0
Bank Sta=90,107.1
XS Rating Curve= 0 ,0
Exp/Cntr=0.3,0.1

Type RM Length L Ch R = 1 ,39108.2 ,166.3,152.7,138.9
XS GIS Cut Line= 3
     1802325.323        308024.4     1802484.828      308128.567
     1802568.378      308131.822
#Sta/Elev= 30
       0 1752.19       4  1748.9    15.9 1737.86    23.8 1731.54    27.8 1729.27
    35.7 1726.83    43.7 1725.78    55.6 1722.69    59.5 1722.46    95.2 1723.22
   111.1 1724.66   115.1 1724.62     131 1722.14   147.9 1718.54   154.8  1717.2
   158.8 1716.94   162.7 1717.17   166.7 1718.62   174.6 1721.67   178.6  1722.3
   182.6  1723.5   190.5 1726.89   194.5 1729.75   202.4 1736.37   222.4 1752.15
   238.3 1766.67   246.2 1773.28   254.2 1780.56   270.1 1793.44   274.1 1796.19
#Mann= 3 , 0 , 0
       0      .1       0   147.9    .045       0   166.7      .1       0
Bank Sta=147.9,166.7
XS Rating Curve= 0 ,0
Exp/Cntr=0.3,0.1

Type RM Length L Ch R = 1 ,38955.5 ,152.3,152.2,152
XS GIS Cut Line= 2
     1802232.007       308255.52     1802608.526       308246.84
#Sta/Elev= 30
       0 1774.14     7.9 1766.45    15.9    1761    19.8 1757.77    35.7 1743.05
    43.6 1736.28    63.4 1721.85    67.4 1720.34    75.3 1719.54    87.2 1719.82
   134.8 1719.18   142.7 1717.86   158.6 1716.53   164.9 1715.04   170.5  1713.5
   178.4 1713.34   182.4 1713.82   190.3 1715.53   202.2 1715.76     226 1718.83
   229.9 1720.68   241.8 1729.91   245.8 1734.43   253.7  1744.7   261.6 1753.19
   273.5 1764.46   281.5 1770.87   325.1 1802.61   352.8 1819.92   376.6 1834.12
#Mann= 3 , 0 , 0
       0      .1       0   164.9    .045       0   182.4      .1       0
Bank Sta=164.9,182.4
XS Rating Curve= 0 ,0
Exp/Cntr=0.3,0.1

Type RM Length L Ch R = 1 ,38803.3 ,172.4,188.7,205
XS GIS Cut Line= 2
     1802229.836       308405.26     1802540.166      308396.579
#Sta/Elev= 30
       0 1738.87    23.9 1721.81    31.8 1718.02    39.8 1716.15    63.7 1715.14
    83.6 1713.34    91.5  1714.1   103.5 1713.96   119.4 1715.02   123.4 1715.44
   131.3 1717.48   143.3  1716.2   187.1 1714.99     199 1711.38     211 1710.36
   214.9 1710.79   218.9 1712.51   222.9 1716.23   226.9 1724.07   230.8 1734.46
   234.8 1743.43   238.8 1749.42   242.8 1753.77   250.8 1760.96   262.7 1772.61
   274.6 1781.86   282.6  1788.9   286.6 1791.58   294.5 1795.64   310.4 1807.25
#Mann= 3 , 0 , 0
       0      .1       0     199    .045       0   218.9      .1       0
#XS Ineff= 2 , 0
          157.48 1736.43
Permanent Ineff=
       F       F
Bank Sta=199,218.9
XS Rating Curve= 0 ,0
Exp/Cntr=0.3,0.1

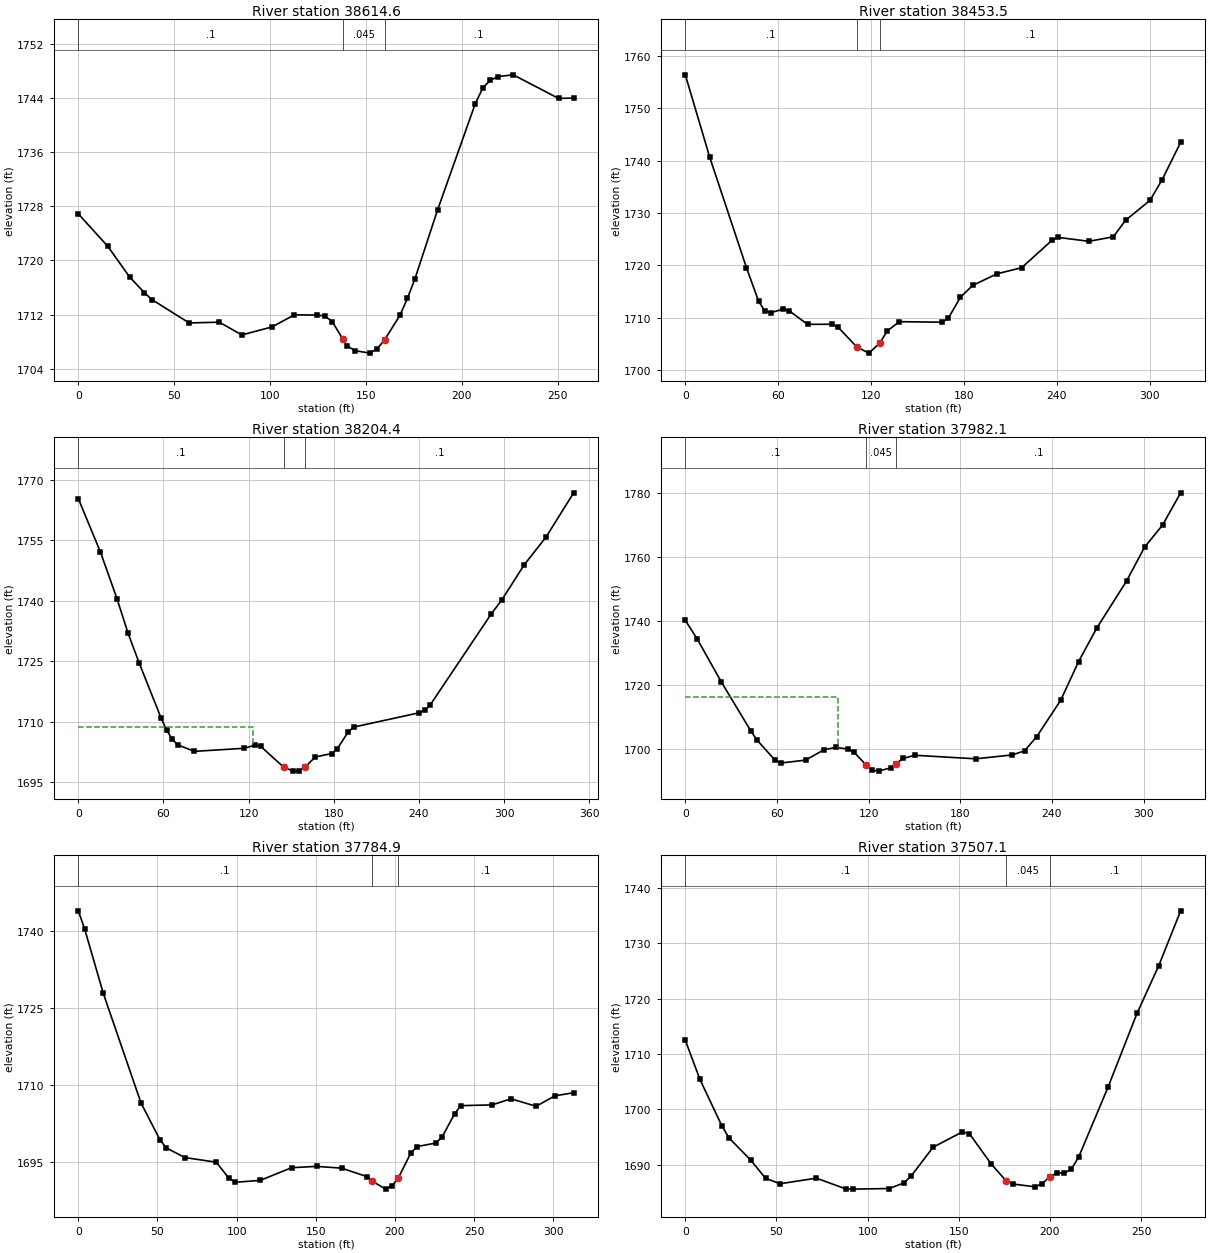
Type RM Length L Ch R = 1 ,38614.6 ,162.1,161.1,160.1
XS GIS Cut Line= 4
     1802226.581       308488.81     1802272.154       308495.32
     1802371.981      308577.786      1802440.34      308624.444
#Sta/Elev= 30
       0 1726.88    15.4 1722.08    26.8 1717.54    34.5 1715.23    38.4 1714.21
    57.8 1710.77    73.5 1710.88    85.3    1709     101 1710.18   112.7 1711.97
   124.5 1711.93   128.4  1711.8   132.4 1710.98   137.8 1708.43   140.2  1707.4
   144.1 1706.68     152 1706.31   155.9 1706.98   159.8  1708.3   167.7  1711.9
   171.6 1714.39   175.5 1717.26   187.3 1727.44     207 1743.16     211 1745.53
   214.9 1746.62   218.9 1747.17   226.8 1747.42   250.4 1743.94   258.3 1743.98
#Mann= 3 , 0 , 0
       0      .1       0   137.8    .045       0   159.8      .1       0
Bank Sta=137.8,159.8
XS Rating Curve= 0 ,0
Exp/Cntr=0.3,0.1

Type RM Length L Ch R = 1 ,38453.5 ,269,249.1,228.5
XS GIS Cut Line= 2
     1802122.415      308578.871     1802378.491      308770.928
#Sta/Elev= 30
       0 1756.37    15.8 1740.64    39.5 1719.61    47.4 1713.17    51.4 1711.32
    55.3 1711.01    63.2 1711.66    67.2 1711.34      79 1708.77    94.8 1708.79
    98.8 1708.21   110.8 1704.46   118.6 1703.28   125.8 1705.22   130.4 1707.48
   138.3 1709.28     166 1709.18   169.9  1709.9   177.8 1713.94   185.7  1716.2
   201.5 1718.42   217.4 1719.58   237.1 1724.84   241.1 1725.35   260.8 1724.61
   276.6 1725.47   284.5 1728.62   300.3 1732.42   308.2  1736.4   320.1 1743.49
#Mann= 3 , 0 , 0
       0      .1       0   110.8    .045       0   125.8      .1       0
Bank Sta=110.8,125.8
XS Rating Curve= 0 ,0
Exp/Cntr=0.3,0.1

Type RM Length L Ch R = 1 ,38204.4 ,215.6,222.3,228.6
XS GIS Cut Line= 4
     1802059.481       308880.52     1802191.859       308882.69
      1802288.43      308856.649     1802404.533      308844.713
#Sta/Elev= 30
       0 1765.36    15.6  1752.1    27.3 1740.51      35 1732.04    42.8 1724.69
    58.4  1710.9    62.3 1707.92    66.2 1705.73    70.1 1704.31    81.8  1702.7
   116.8 1703.46   124.6 1704.25   128.5 1703.95   144.9 1698.73   151.6  1697.8
   155.5 1697.82   159.9 1698.84     167  1701.3   178.6 1702.16   182.4 1703.28
   190.1 1707.46     194 1708.71   240.2 1712.26   244.1 1712.85     248 1714.21
   290.8 1736.66   298.6 1740.32   314.1 1748.87   329.7 1755.86   349.1 1766.79
#Mann= 3 , 0 , 0
       0      .1       0   144.9    .045       0   159.9      .1       0
#XS Ineff= 2 , 0
          122.76 1708.67
Permanent Ineff=
       F       F
Bank Sta=144.9,159.9
XS Rating Curve= 0 ,0
Exp/Cntr=0.3,0.1

Type RM Length L Ch R = 1 ,37982.1 ,183,197.2,211.3
XS GIS Cut Line= 4
     1802067.076      309057.386     1802109.394      309085.598
      1802288.43      309093.194     1802379.576      309117.065
#Sta/Elev= 30
       0 1740.25     7.8  1734.4    23.5 1721.01      43 1705.51      47  1702.7
    58.8 1696.42    62.8 1695.56    78.7 1696.44    90.7 1699.67    98.6 1700.46
   106.6 1699.91   110.6 1698.85   118.6 1694.83   122.5  1693.3   126.5    1693
   134.5 1694.03   138.2 1695.35   142.4 1696.98   150.4 1697.96   190.2 1696.86
   214.1 1698.08   222.1 1699.34   230.1 1703.83   245.8 1715.22   257.5 1727.33
   269.3 1737.75   288.9 1752.56   300.7 1763.18   312.5 1770.11   324.3 1780.18
#Mann= 3 , 0 , 0
       0      .1       0   118.6    .045       0   138.2      .1       0
#XS Ineff= 2 , 0
          100.13 1716.12
Permanent Ineff=
       F       F
Bank Sta=118.6,138.2
XS Rating Curve= 0 ,0
Exp/Cntr=0.3,0.1

Type RM Length L Ch R = 1 ,37784.9 ,275.3,277.8,274.6
XS GIS Cut Line= 2
     1801987.866      309160.468     1802237.432       309349.27
#Sta/Elev= 30
       0 1744.03       4  1740.5    15.8 1727.91    39.6 1706.54    51.5  1699.4
    55.5 1697.79    67.3 1695.89    87.2 1694.98    95.1 1691.85      99 1691.07
   114.9 1691.43   134.7 1693.91   150.5 1694.17   166.4 1693.82   182.2 1692.18
   185.4 1691.35   194.1 1689.73   198.1 1690.37     202 1691.83   209.9 1696.69
   213.9 1698.04   225.8 1698.71   229.8 1699.92   237.7 1704.42   241.6 1706.02
   261.4 1706.16   273.3 1707.36   289.2 1705.89     301 1707.93   312.9 1708.54
#Mann= 3 , 0 , 0
       0      .1       0   185.4    .045       0     202      .1       0
Bank Sta=185.4,202
XS Rating Curve= 0 ,0
Exp/Cntr=0.3,0.1

Type RM Length L Ch R = 1 ,37507.1 ,97.2,125.8,124.4
XS GIS Cut Line= 2
     1801872.849      309401.353     1802108.309      309536.987
#Sta/Elev= 30
       0  1712.5       8 1705.45      20 1697.08      24 1694.86      36 1690.82
      44 1687.58      52 1686.59    71.9  1687.6    87.9 1685.67    91.9 1685.62
   111.9 1685.73   119.9 1686.74   123.9 1687.99   135.9 1693.18   151.8 1695.92
   155.8 1695.65   167.8 1690.16   175.8 1687.17   179.8 1686.54   191.8 1686.04
   195.8 1686.62   199.8  1687.8   203.8 1688.54   207.8 1688.48   211.8 1689.25
   215.8 1691.44   231.8 1703.97   247.8 1717.38   259.7 1725.97   271.7 1735.86
#Mann= 3 , 0 , 0
       0      .1       0   175.8    .045       0   199.8      .1       0
Bank Sta=175.8,199.8
XS Rating Curve= 0 ,0
Exp/Cntr=0.3,0.1

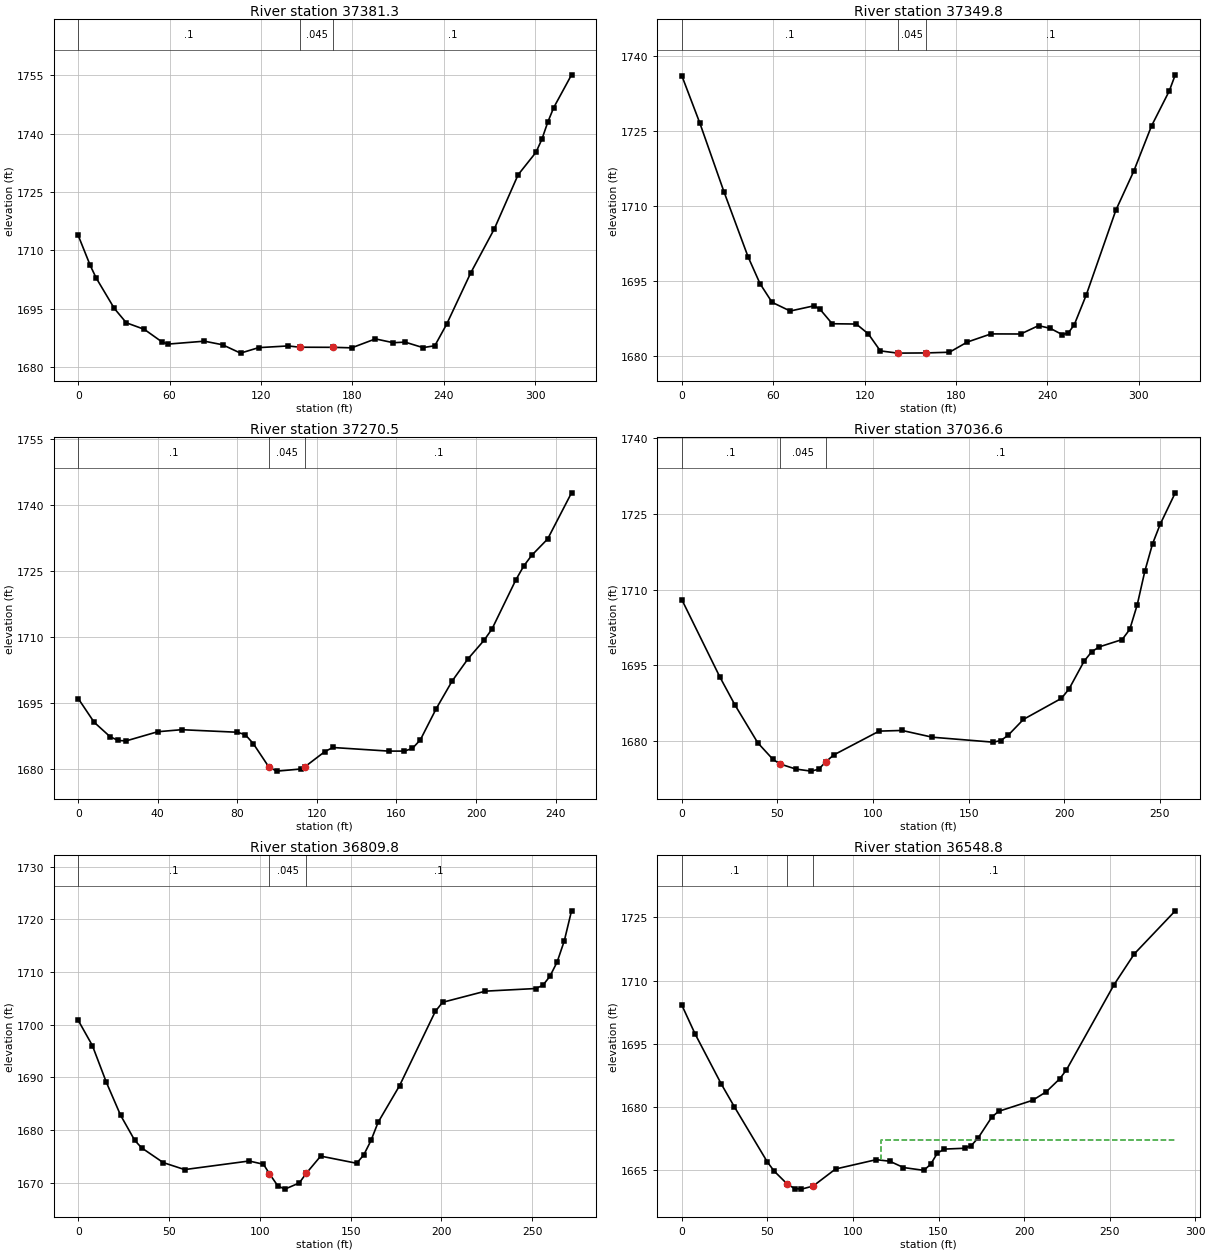
Type RM Length L Ch R = 1 ,37381.3 ,39.8,31.4,57.8
XS GIS Cut Line= 4
     1801852.232      309429.565     1801961.824      309500.095
     1801945.548      309542.412     1802068.161      309625.963
#Sta/Elev= 30
       0 1713.83     7.9 1706.11    11.8 1702.89    23.7 1695.07    31.6 1691.37
    43.4 1689.69    55.3 1686.37    59.2  1685.9    82.9 1686.64    94.8 1685.72
   106.6 1683.57   118.5 1684.98   137.9 1685.42   145.4 1685.09   167.6 1685.06
   179.6 1684.93   195.2 1687.23   206.9 1686.25   214.7  1686.4   226.4 1684.99
   234.2 1685.46     242 1691.02   257.7 1704.13   273.3 1715.52   288.9 1729.42
   300.6 1735.18   304.5 1738.52   308.4 1742.96   312.3  1746.7     324 1755.12
#Mann= 3 , 0 , 0
       0      .1       0   145.4    .045       0   167.6      .1       0
Bank Sta=145.4,167.6
XS Rating Curve= 0 ,0
Exp/Cntr=0.3,0.1

Type RM Length L Ch R = 1 ,37349.8 ,98.6,79.4,56.7
XS GIS Cut Line= 4
     1801818.595      309431.735     1801928.187      309502.265
     1801911.911      309544.583     1802034.524      309628.133
#Sta/Elev= 30
       0 1735.97    11.8 1726.53    27.6 1712.85    43.4 1699.88    51.3 1694.48
    59.2 1690.76    71.1 1689.02    86.9 1690.07    90.8 1689.33    98.7 1686.48
   114.5 1686.42   122.4 1684.46   130.3 1681.06   141.7 1680.61   160.6 1680.65
   175.7 1680.79   187.4 1682.82     203 1684.45   222.5 1684.43   234.2  1686.1
     242 1685.55   249.8  1684.3   253.8 1684.65   257.7  1686.3   265.5 1692.19
     285 1709.17   296.7 1716.92   308.4 1725.98   320.1    1733     324  1736.2
#Mann= 3 , 0 , 0
       0      .1       0   141.7    .045       0   160.6      .1       0
Bank Sta=141.7,160.6
XS Rating Curve= 0 ,0
Exp/Cntr=0.3,0.1

Type RM Length L Ch R = 1 ,37270.5 ,230.4,233.9,236.6
XS GIS Cut Line= 2
     1801808.829      309517.456     1801990.036      309686.727
#Sta/Elev= 30
       0 1695.98       8 1690.58      16  1687.3      20 1686.44      24 1686.32
      40 1688.42      52 1688.88      80  1688.3      84 1687.74      88 1685.72
      96 1680.28     100 1679.45     112 1679.94     114 1680.45     124  1683.9
     128 1684.83     156 1684.01     164 1684.01     168 1684.62     172 1686.57
     180 1693.69     188 1699.97     196 1705.04     204 1709.22     208 1711.79
     220 1722.98     224 1726.16     228 1728.58     236  1732.3     248  1742.8
#Mann= 3 , 0 , 0
       0      .1       0      96    .045       0     114      .1       0
Bank Sta=96,114
XS Rating Curve= 0 ,0
Exp/Cntr=0.3,0.1

Type RM Length L Ch R = 1 ,37036.6 ,229,226.8,224.4
XS GIS Cut Line= 2
     1801650.409      309637.899     1801809.915      309840.807
#Sta/Elev= 30
       0 1707.97    19.8 1692.72    27.8  1687.1    39.7 1679.63    47.6 1676.37
    51.3 1675.45    59.6 1674.44    67.5 1674.03    71.5 1674.39    75.4 1675.92
    79.4 1677.23   103.2 1681.96   115.2 1682.09     131 1680.75   162.8 1679.77
   166.8 1680.08   170.7 1681.15   178.7 1684.29   198.5 1688.44   202.5 1690.29
   210.4 1695.81   214.4  1697.7   218.4 1698.66   230.3  1700.1   234.3 1702.12
   238.2 1706.98   242.2 1713.68   246.2 1719.05   250.2 1722.94   258.1 1729.18
#Mann= 3 , 0 , 0
       0      .1       0    51.3    .045       0    75.4      .1       0
Bank Sta=51.3,75.4
XS Rating Curve= 0 ,0
Exp/Cntr=0.3,0.1

Type RM Length L Ch R = 1 ,36809.8 ,259.5,261,262
XS GIS Cut Line= 3
     1801496.329      309785.468     1801516.946       309813.68
     1801675.366      309989.461
#Sta/Elev= 30
       0 1700.83     7.8 1696.04    15.5 1689.06    23.3 1682.83    31.1 1678.05
    34.9 1676.62    46.8 1673.82    58.6 1672.49    94.1 1674.12     102  1673.5
   105.3 1671.69   109.9 1669.39   113.8 1668.78   121.7 1669.95   125.6  1671.8
   133.5 1675.05   153.3 1673.69   157.2 1675.27   161.2 1678.02   165.1 1681.46
   176.9 1688.41   196.6 1702.52   200.6 1704.25   224.2 1706.37   251.9 1706.87
   255.8 1707.47   259.7 1709.19   263.7 1711.93   267.6 1715.91   271.6 1721.62
#Mann= 3 , 0 , 0
       0      .1       0   105.3    .045       0   125.6      .1       0
Bank Sta=105.3,125.6
XS Rating Curve= 0 ,0
Exp/Cntr=0.3,0.1

Type RM Length L Ch R = 1 ,36548.8 ,355.8,353.9,352
XS GIS Cut Line= 3
     1801308.612      309939.548     1801334.654      309977.525
     1801486.564      310166.327
#Sta/Elev= 30
       0 1704.11     7.7 1697.31      23 1685.42    30.7 1679.97      50 1666.85
      54 1664.69    61.7 1661.59    65.9 1660.58    69.9 1660.44    76.7 1661.17
    89.8 1665.22   113.6 1667.44   121.5 1667.07   129.5 1665.57   141.4  1664.9
   145.4 1666.34   149.3 1668.97   153.3 1669.95   165.2 1670.15   169.2  1670.8
   173.2 1672.62   181.1 1677.52   185.1 1678.92     205 1681.54   212.9 1683.54
   220.8 1686.62   224.8 1688.78   252.6    1709   264.5 1716.35   288.4 1726.56
#Mann= 3 , 0 , 0
       0      .1       0    61.7    .045       0    76.7      .1       0
#XS Ineff= 2 , 0
                          116.39         1672.05
Permanent Ineff=
       F       F
Bank Sta=61.7,76.7
XS Rating Curve= 0 ,0
Exp/Cntr=0.3,0.1

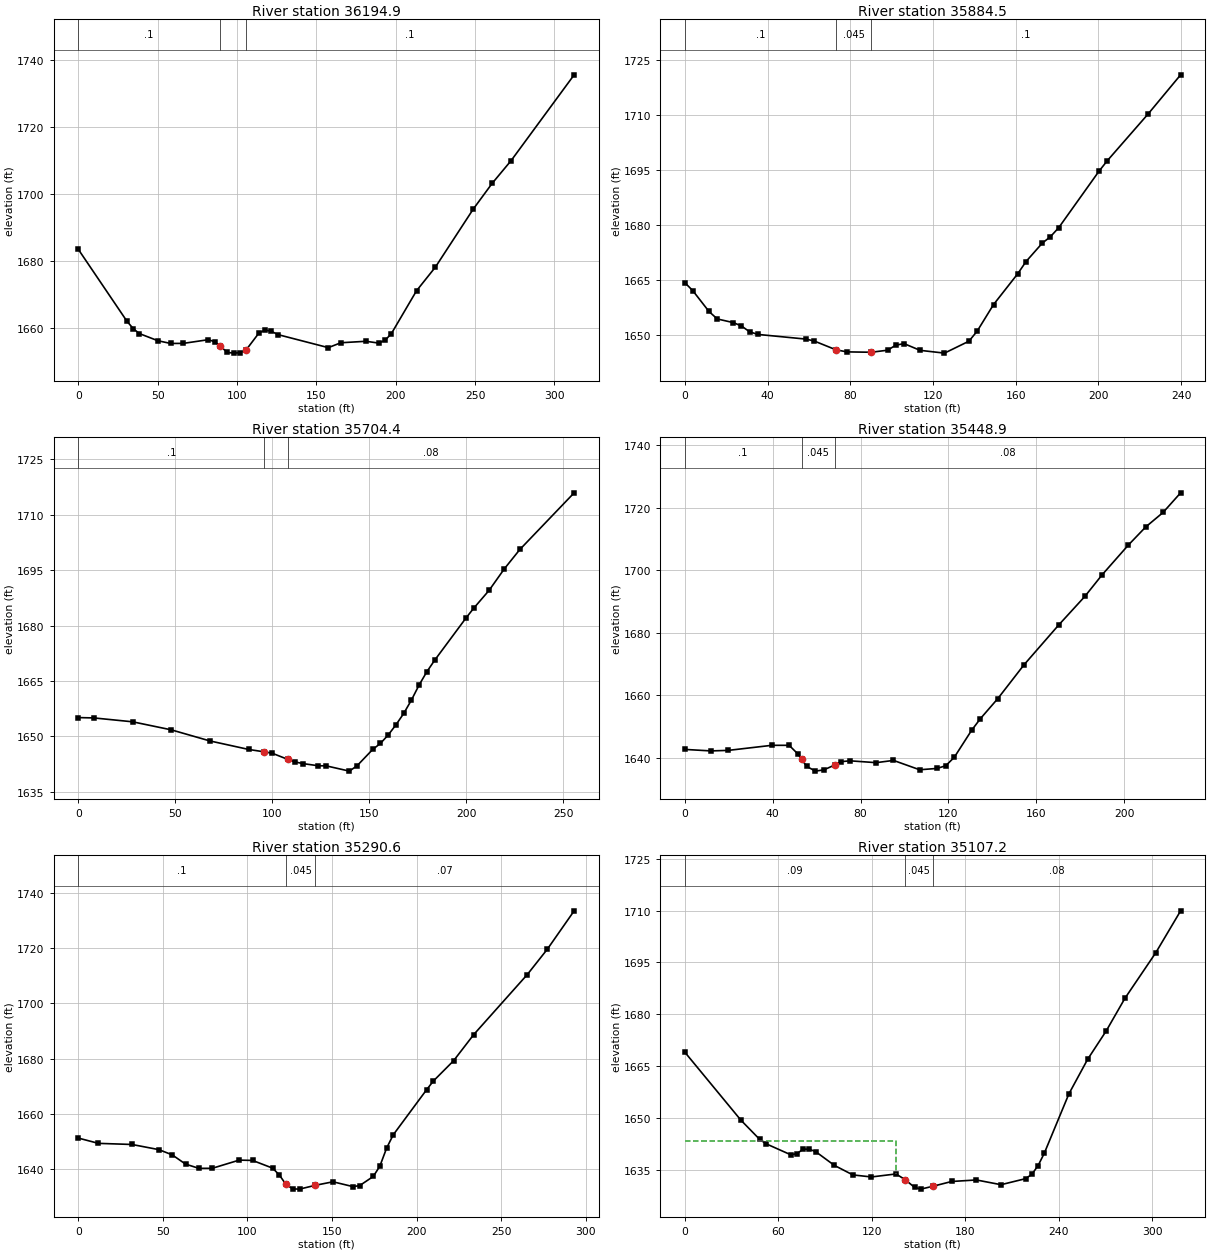
Type RM Length L Ch R = 1 ,36194.9 ,310,310.4,309.5
XS GIS Cut Line= 3
     1801065.557      310181.518     1801086.173      310218.411
     1801272.805      310413.723
#Sta/Elev= 30
       0 1683.46    30.7 1661.95    34.6 1659.79    38.4 1658.32    50.2 1656.16
    58.2 1655.36    66.1 1655.38      82 1656.49      86 1655.84    89.2 1654.61
    93.9 1652.68    97.9 1652.47   101.8  1652.6   105.8 1653.48   113.8 1658.48
   117.7 1659.38   121.7 1658.98   125.7 1658.01   157.5 1654.11   165.4 1655.57
   181.3 1656.01   189.2 1655.47   193.2 1656.28   197.2 1658.27   213.1 1671.11
     225 1678.18   248.8 1695.48   260.8 1703.22   272.7 1709.99   312.4  1735.6
#Mann= 3 , 0 , 0
       0      .1       0    89.2    .045       0   105.8      .1       0
Bank Sta=89.2,105.8
XS Rating Curve= 0 ,0
Exp/Cntr=0.3,0.1

Type RM Length L Ch R = 1 ,35884.5 ,180.9,180.1,178.4
XS GIS Cut Line= 3
     1800890.861      310426.744     1800917.987      310478.827
     1801047.111       310605.78
#Sta/Elev= 30
       0 1664.21     3.9 1661.99    11.7 1656.34    15.7  1654.3    23.5  1653.3
    27.4 1652.38    31.3 1650.82    35.2 1650.09    58.7  1648.8    62.7 1648.26
    73.1 1645.89    78.4 1645.32    90.2 1645.22    98.1 1645.78     102 1647.14
     106 1647.58   113.8 1645.74   125.6 1644.98   137.4 1648.23   141.4 1650.97
   149.3 1658.21   161.1 1666.69     165 1669.94   172.9 1674.98   176.8 1676.72
   180.8 1679.16   200.4 1694.66   204.4  1697.5   224.1 1710.22   239.8 1720.88
#Mann= 3 , 0 , 0
       0      .1       0    73.1    .045       0    90.2      .1       0
Bank Sta=73.1,90.2
XS Rating Curve= 0 ,0
Exp/Cntr=0.3,0.1

Type RM Length L Ch R = 1 ,35704.4 ,262.1,255.5,248.9
XS GIS Cut Line= 2
     1800751.972      310567.803     1800939.689      310741.414
#Sta/Elev= 30
       0 1655.11       8 1655.02      28 1653.97    47.9  1651.8    67.9 1648.79
    87.9 1646.49    95.9 1645.84    99.9 1645.49   107.9 1643.83   111.9  1643.1
   115.9 1642.66   123.8 1642.08   127.8 1642.06   139.8 1640.63   143.8 1642.11
   151.8 1646.49   155.8 1648.13   159.8 1650.41   163.8 1653.15   167.8 1656.23
   171.8 1659.87   175.8 1663.99   179.8 1667.57   183.8 1670.65   199.8 1681.96
   203.8 1684.63   211.8  1689.5   219.7 1695.35   227.7 1700.58   255.7  1715.9
#Mann= 3 , 0 , 0
       0      .1       0    95.9    .045       0   107.9     .08       0
Bank Sta=95.9,107.9
XS Rating Curve= 0 ,0
Exp/Cntr=0.3,0.1

Type RM Length L Ch R = 1 ,35448.9 ,157.4,158.3,159.2
XS GIS Cut Line= 2
     1800654.316       310832.56     1800857.224      310931.301
#Sta/Elev= 30
       0 1642.73    11.9 1642.25    19.8 1642.42    39.6 1644.04    47.5 1644.04
    51.5 1641.26    53.2 1639.56    55.4 1637.35    59.4 1635.78    63.3 1636.18
    68.2 1637.73    71.3 1638.82    75.2 1639.08    87.1 1638.49      95 1639.21
   106.9 1636.22   114.8 1636.64   118.8 1637.51   122.7 1640.24   130.6 1648.89
   134.6 1652.61   142.5 1659.01   154.4  1669.8   170.2 1682.55   182.1 1691.69
     190 1698.64   201.9 1708.13   209.8 1713.92   217.7 1718.56   225.7 1724.85
#Mann= 3 , 0 , 0
       0      .1       0    53.2    .045       0    68.2     .08       0
Bank Sta=53.2,68.2
XS Rating Curve= 0 ,0
Exp/Cntr=0.3,0.1

Type RM Length L Ch R = 1 ,35290.6 ,188.5,183.4,177.9
XS GIS Cut Line= 2
     1800533.873      310943.237     1800792.119      311082.126
#Sta/Elev= 30
       0 1651.13    11.9 1649.21    31.7 1648.81    47.6 1646.94    55.5 1645.05
    63.4 1641.68    71.3 1640.14    79.2 1640.16    95.1 1643.13     103 1643.02
   114.9 1640.22   118.9  1637.7   122.8 1634.28   126.8 1632.69   130.8  1632.6
   140.2    1634   150.6 1635.26   162.5  1633.5   166.4  1633.9   174.4 1637.19
   178.3 1640.94   182.3 1647.49   186.2  1652.3     206 1668.73     210 1671.88
   221.9  1679.2   233.8 1688.69   265.5  1710.5   277.4 1719.74   293.2 1733.62
#Mann= 3 , 0 , 0
       0      .1       0   122.8    .045       0   140.2     .07       0
Bank Sta=122.8,140.2
XS Rating Curve= 0 ,0
Exp/Cntr=0.3,0.1

Type RM Length L Ch R = 1 ,35107.2 ,114.3,109.1,102.8
XS GIS Cut Line= 4
     1800440.557      311105.998     1800525.192      311159.166
     1800655.401      311193.888     1800738.951      311190.633
#Sta/Elev= 30
       0 1669.06      36  1649.4      48 1643.87      52  1642.6      68 1639.39
      72  1639.7      76 1641.04      80 1640.97      84  1640.3      96 1636.32
   107.9 1633.56   119.8 1632.97   135.6 1633.84   141.6 1632.14   147.5 1629.96
   151.5 1629.45   159.4 1630.29   171.3 1631.66   187.2  1632.1     203 1630.73
   218.8 1632.48   222.8 1633.74   226.8 1636.25   230.8 1639.85   246.6 1657.02
   258.6 1666.99   270.5 1675.18   282.5  1684.6   302.4 1697.85   318.3 1709.93
#Mann= 3 , 0 , 0
       0     .09       0   141.6    .045       0   159.4     .08       0
#XS Ineff= 2 , 0
          135.78 1643.47
Permanent Ineff=
       F       F
Bank Sta=141.6,159.4
XS Rating Curve= 0 ,0
Exp/Cntr=0.3,0.1

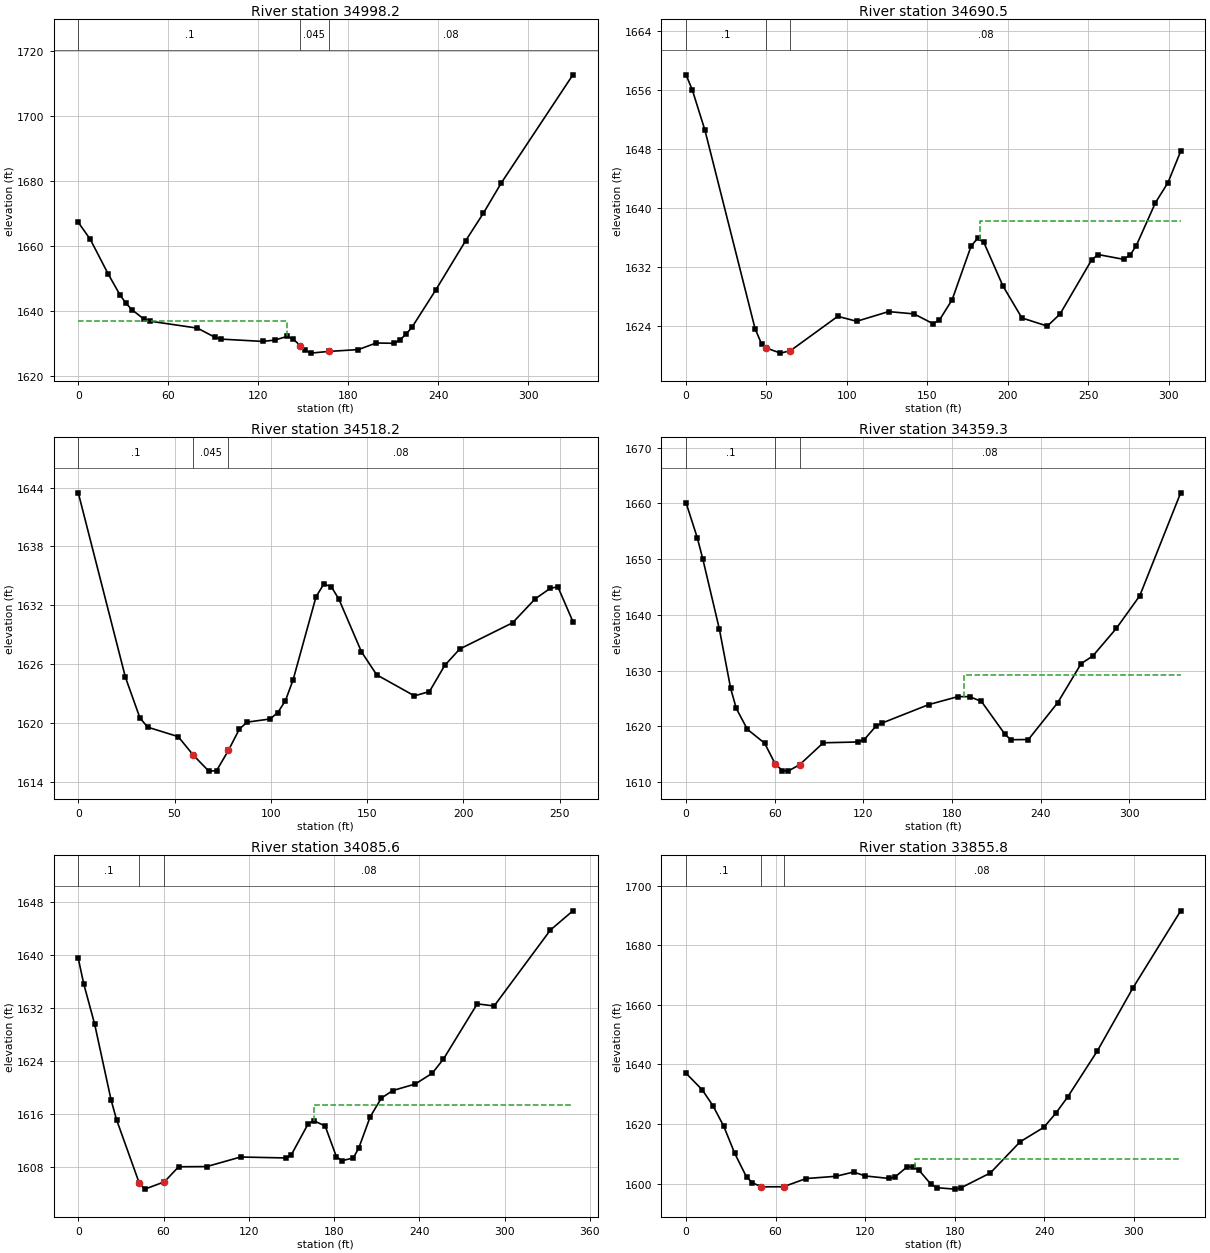
Type RM Length L Ch R = 1 ,34998.2 ,299,307.7,315.8
XS GIS Cut Line= 2
     1800416.685      311278.524     1800746.546      311278.524
#Sta/Elev= 30
       0  1667.2       8 1661.97    19.9 1651.35    27.8 1644.89    31.8  1642.3
    35.8 1640.32    43.7 1637.44    47.7  1636.8    79.5 1634.65    91.4 1631.77
    95.4 1631.27   123.2 1630.56   131.2 1630.98   139.1 1632.09   143.1 1631.38
   148.1 1629.25     151 1627.97     155 1626.96   166.9 1627.48   186.8 1628.05
   198.7 1630.08   210.6 1629.98   214.6 1631.01   218.6 1632.81   222.6 1634.93
   238.4 1646.36   258.3  1661.5   270.2 1670.01   282.2 1679.36   329.9 1712.58
#Mann= 3 , 0 , 0
       0      .1       0   148.1    .045       0   166.9     .08       0
#XS Ineff= 2 , 0
           139.5 1636.71
Permanent Ineff=
       F       F
Bank Sta=148.1,166.9
XS Rating Curve= 0 ,0
Exp/Cntr=0.3,0.1

Type RM Length L Ch R = 1 ,34690.5 ,173.1,172.3,170
XS GIS Cut Line= 3
     1800418.856      311500.963     1800445.982      311516.154
     1800702.059       311620.32
#Sta/Elev= 30
       0 1658.01     3.9 1655.95    11.7 1650.54    42.9 1623.65    46.9  1621.6
    49.9 1621.03    58.7 1620.34    64.9 1620.67    94.3 1625.32   106.1 1624.65
   125.9 1625.96   141.7 1625.65   153.5 1624.33   157.5 1624.81   165.4 1627.56
   177.2 1634.82   181.2 1635.87   185.1 1635.34     197 1629.43   208.8  1625.1
   224.6    1624   232.5 1625.63   252.2 1632.98   256.2 1633.68     272 1633.04
     276  1633.6   279.9 1634.89   291.8  1640.7   299.6 1643.42   307.5 1647.67
#Mann= 3 , 0 , 0
       0      .1       0    49.9    .045       0    64.9     .08       0
#XS Ineff= 2 , 0
                          182.91         1638.16
Permanent Ineff=
       F       F
Bank Sta=49.9,64.9
XS Rating Curve= 0 ,0
Exp/Cntr=0.3,0.1

Type RM Length L Ch R = 1 ,34518.2 ,150.3,158.9,167.2
XS GIS Cut Line= 4
     1800429.706      311661.553     1800452.493      311677.829
     1800546.894      311709.296     1800668.421      311753.784
#Sta/Elev= 30
       0 1643.46    24.5 1624.63      32  1620.5      36 1619.55    51.9 1618.58
    59.8 1616.68    67.8 1615.06    71.8  1615.1      78 1617.18    83.7 1619.36
    87.7 1620.06    99.6 1620.38   103.6 1621.03   107.6 1622.25   111.6 1624.39
   123.5 1632.86   127.5 1634.14   131.4 1633.89   135.4 1632.59   147.1 1627.23
     155 1624.89   174.6 1622.74   182.4 1623.18   190.3 1625.84   198.1 1627.52
   225.6  1630.2   237.3 1632.64   245.2 1633.72   249.1 1633.87   256.9 1630.32
#Mann= 3 , 0 , 0
       0      .1       0    59.8    .045       0      78     .08       0
Bank Sta=59.8,78
XS Rating Curve= 0 ,0
Exp/Cntr=0.3,0.1

Type RM Length L Ch R = 1 ,34359.3 ,269.1,273.8,277
XS GIS Cut Line= 3
     1800348.326      311771.145     1800380.878      311802.612
     1800603.317      311988.159
#Sta/Elev= 30
       0  1660.1     7.6 1653.83    11.3 1650.06    22.6 1637.39    30.2 1626.81
      34 1623.22    41.5 1619.48    53.2 1616.99    60.3  1613.3    65.1 1612.09
    69.1 1611.98      77 1613.15    92.9 1617.06   116.7 1617.21   120.7 1617.65
   128.6 1620.06   132.6 1620.59   164.3 1623.91   184.2 1625.35   192.1 1625.32
     200 1624.48   215.9 1618.59   219.9 1617.61   231.8 1617.65   251.6 1624.24
   267.5 1631.26   275.4 1632.63   291.3 1637.57   307.2 1643.43   334.9 1661.89
#Mann= 3 , 0 , 0
       0      .1       0    60.3    .045       0      77     .08       0
#XS Ineff= 2 , 0
                          187.87         1629.13
Permanent Ineff=
       F       F
Bank Sta=60.3,77
XS Rating Curve= 0 ,0
Exp/Cntr=0.3,0.1

Type RM Length L Ch R = 1 ,34085.6 ,230.5,229.8,228.8
XS GIS Cut Line= 3
     1800160.609      311956.692       1800175.8      311974.053
     1800385.218      312222.534
#Sta/Elev= 30
       0 1639.43     3.8 1635.63    11.5 1629.55    23.1 1618.08      27 1615.08
    42.9 1605.57    46.8 1604.66    60.6 1605.76    70.6 1608.03    90.4 1608.06
   114.2  1609.5   145.9 1609.36   149.9 1609.83   161.8 1614.53   165.7 1614.97
   173.7 1614.17   181.6 1609.54   185.6 1608.95   193.5 1609.35   197.4 1610.88
   205.4 1615.57   213.3 1618.39   221.2 1619.51   237.1  1620.5     249 1622.12
   256.9 1624.25   280.7 1632.58   292.6 1632.26   332.2 1643.71     348  1646.6
#Mann= 3 , 0 , 0
       0      .1       0    42.9    .045       0    60.6     .08       0
#XS Ineff= 2 , 0
                          166.16         1617.35
Permanent Ineff=
       F       F
Bank Sta=42.9,60.6
XS Rating Curve= 0 ,0
Exp/Cntr=0.3,0.1

Type RM Length L Ch R = 1 ,33855.8 ,230.8,236.5,241.7
XS GIS Cut Line= 3
      1800019.55      312131.388     1800039.081       312157.43
     1800239.819      312378.784
#Sta/Elev= 30
       0 1637.04    10.8  1631.5    18.1 1626.08    25.3  1619.2    32.6 1610.18
    40.5 1602.23    44.5 1600.33    50.3 1598.94    65.3 1598.97    80.4 1601.72
   100.3 1602.47   112.2 1603.89   120.2 1602.58   136.1 1601.75   140.1 1602.28
   148.1 1605.64   152.1 1605.64   156.1  1604.5     164 1599.85     168 1598.65
     180 1598.17     184 1598.56   203.9  1603.6   223.8 1614.04   239.7  1618.9
   247.7  1623.6   255.7  1629.1   275.6 1644.56   299.5 1665.75   331.4 1691.53
#Mann= 3 , 0 , 0
       0      .1       0    50.3    .045       0    65.3     .08       0
#XS Ineff= 2 , 0
                          153.45         1608.16
Permanent Ineff=
       F       F
Bank Sta=50.3,65.3
XS Rating Curve= 0 ,0
Exp/Cntr=0.3,0.1