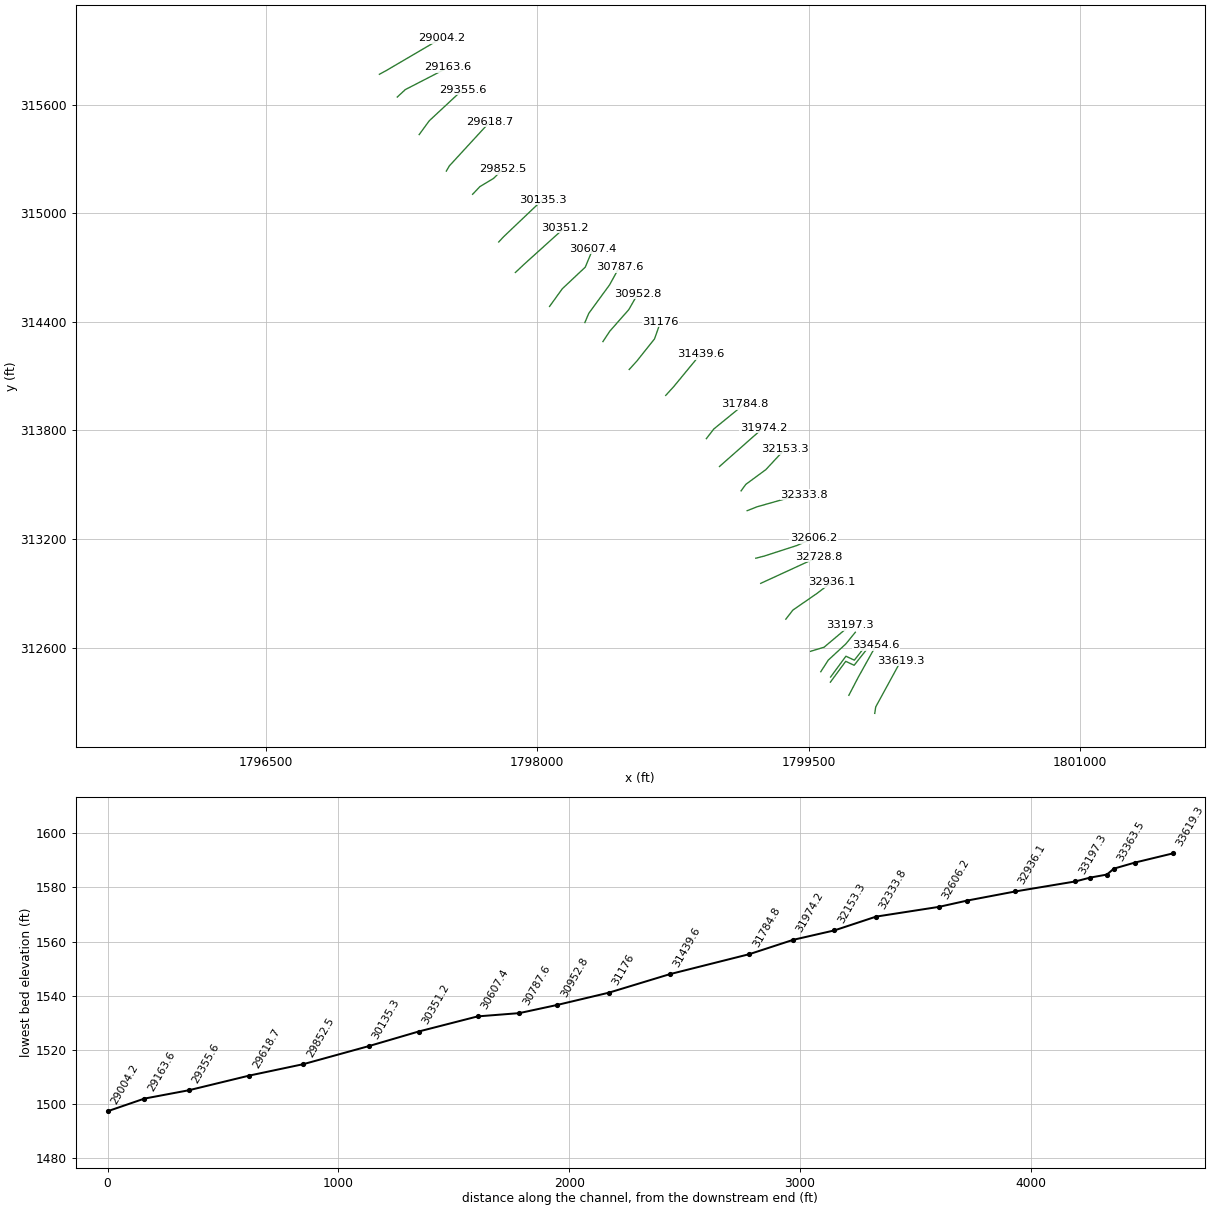
HEC-RAS study WESTFK1.prj: WESTFK1

--- WESTFK1.g01 (geometry) --- (continued)

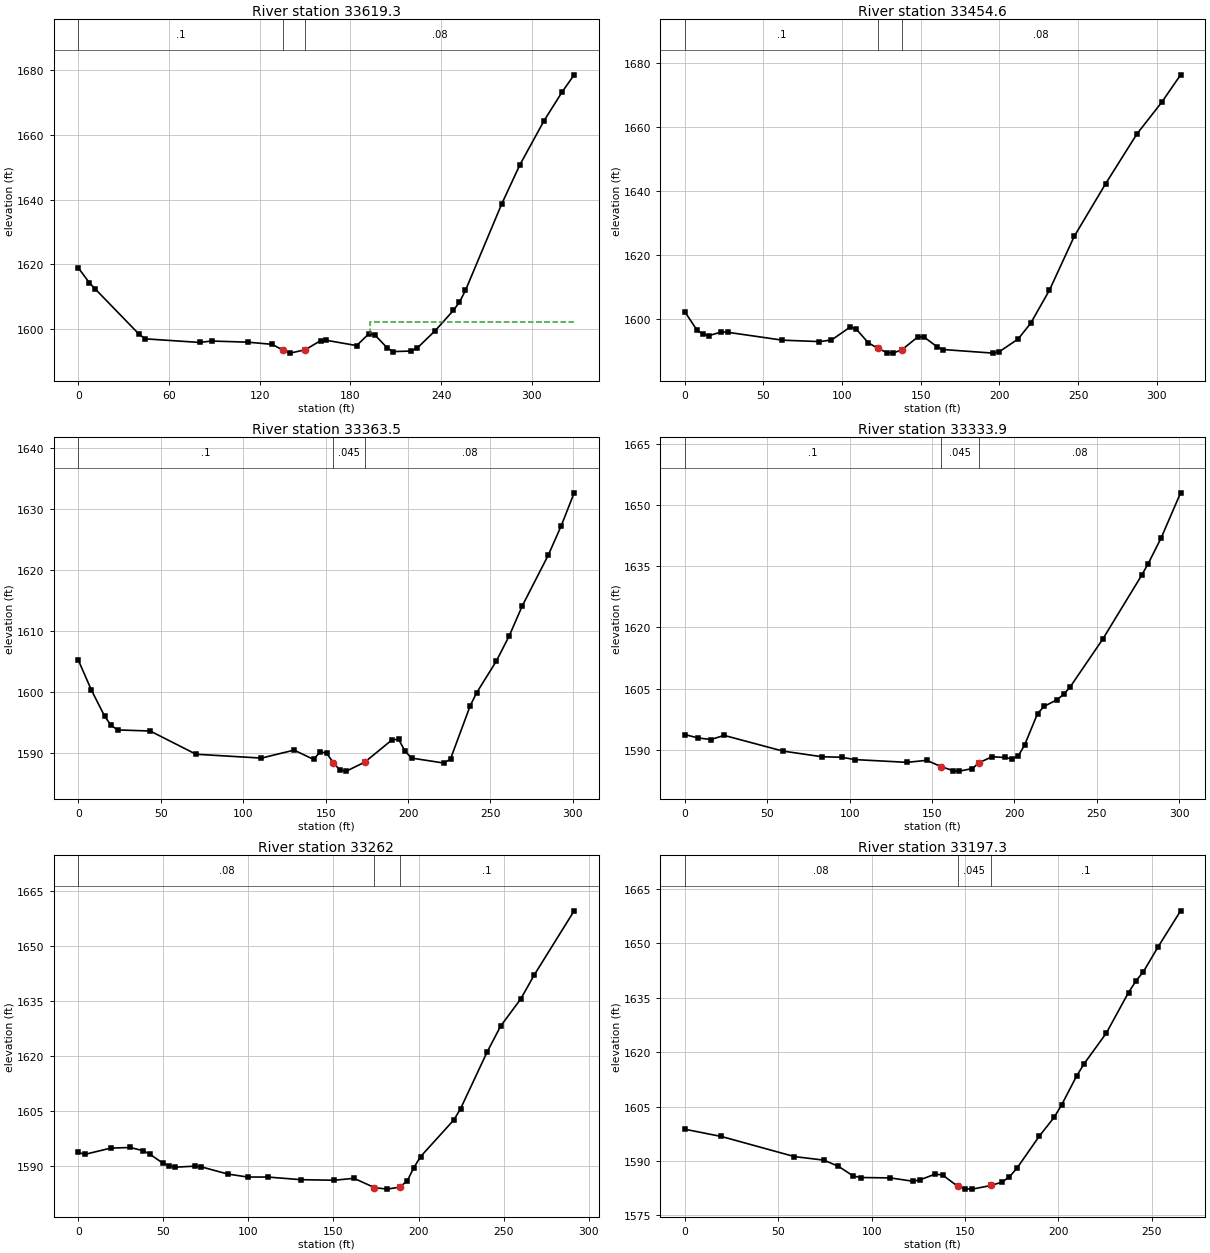
Type RM Length L Ch R = 1 ,33619.3 ,164.5,164.7,164.1
XS GIS Cut Line= 3
      1799865.47       312236.64     1799870.895      312272.447
     1800010.869      312528.524
#Sta/Elev= 30
       0  1618.9     7.2 1614.37    10.9 1612.53    40.2 1598.43    44.2 1597.02
    80.2 1595.91    88.2 1596.34   112.2 1595.99   128.2 1595.32   135.2 1593.56
   140.2 1592.61   150.2 1593.67   160.2 1596.44   164.1 1596.56   184.1 1594.94
   192.1 1598.53   196.1 1598.25   204.1 1594.34   208.1 1593.08   220.1 1593.25
   224.1 1594.14   236.1 1599.54   248.1 1605.78   252.1 1608.32   256.1 1611.96
   280.1 1638.66   292.1  1650.7   308.1 1664.32   320.1 1673.22     328 1678.46
#Mann= 3 , 0 , 0
       0      .1       0   135.2    .045       0   150.2     .08       0
#XS Ineff= 2 , 0
                          192.83         1602.07
Permanent Ineff=
       F       F
Bank Sta=135.2,150.2
XS Rating Curve= 0 ,0
Exp/Cntr=0.3,0.1

Type RM Length L Ch R = 1 ,33454.6 ,121.6,91.1,54.8
XS GIS Cut Line= 3
     1799722.241      312336.466     1799774.324      312436.293
     1799873.066      312613.159
#Sta/Elev= 30
       0 1602.19     7.8 1596.38    11.6 1595.07    15.5 1594.72    23.3 1595.85
    27.2 1595.75    62.1 1593.27    85.4 1592.83    93.2  1593.3   104.8 1597.26
   108.7 1596.92   116.6 1592.47   122.8 1590.69   128.5 1589.38   132.5 1589.28
   137.8 1590.19   148.3 1594.34   152.3 1594.18   160.3 1591.22   164.2 1590.34
     196 1589.21     200 1589.68   211.9 1593.64   219.8 1598.51   231.8 1608.93
   247.6 1625.84   267.5 1642.29   287.4  1657.9   303.2 1667.85   315.2 1676.44
#Mann= 3 , 0 , 0
       0      .1       0   122.8    .045       0   137.8     .08       0
Bank Sta=122.8,137.8
XS Rating Curve= 0 ,0
Exp/Cntr=0.3,0.1

Type RM Length L Ch R = 1 ,33363.5 ,23.8,29.7,30.8
XS GIS Cut Line= 4
     1799620.244      312409.166      1799704.88      312524.183
     1799751.538      312502.482     1799817.727      312586.032
#Sta/Elev= 30
       0 1605.17     7.9 1600.27    15.9    1596    19.8 1594.49    23.8 1593.72
    43.6 1593.54    71.4 1589.73   111.1  1589.1   130.9 1590.41   142.8 1588.87
   146.8 1590.17   150.7 1589.86   154.7 1588.37   158.6 1587.14   162.6 1586.96
   173.8 1588.44   190.3 1592.09   194.3 1592.18   198.2 1590.23   202.2  1589.1
   221.9 1588.28   225.8 1588.97   237.7 1597.66   241.6  1599.8   253.5 1604.97
   261.4 1609.14   269.3 1614.06   285.1  1622.4     293 1627.24   300.8 1632.62
#Mann= 3 , 0 , 0
       0      .1       0   154.7    .045       0   173.8     .08       0
Bank Sta=154.7,173.8
XS Rating Curve= 0 ,0
Exp/Cntr=0.3,0.1

Type RM Length L Ch R = 1 ,33333.9 ,53.7,71.9,98.9
XS GIS Cut Line= 4
     1799621.329      312437.378     1799705.965      312552.395
     1799752.623      312530.694     1799818.812      312614.244
#Sta/Elev= 30
       0 1593.74     7.9 1592.92    15.9 1592.51    23.8 1593.54    59.5 1589.69
    83.3  1588.3    95.2 1588.18   103.1 1587.61   134.9 1586.93   146.8 1587.43
   155.5 1585.88   162.6 1584.92   166.6 1584.78   174.5 1585.41   178.4 1586.82
   186.3 1588.29   194.3 1588.13   198.2 1587.77   202.2 1588.43   206.1 1591.12
     214 1598.88     218 1600.65   225.8 1602.26   229.8 1603.58   233.7 1605.35
   253.5 1617.08   277.2 1632.78   281.1 1635.58     289 1641.92   300.8 1652.95
#Mann= 3 , 0 , 0
       0      .1       0   155.5    .045       0   178.4     .08       0
Bank Sta=155.5,178.4
XS Rating Curve= 0 ,0
Exp/Cntr=0.3,0.1

Type RM Length L Ch R = 1 ,33262   ,65.6,64.7,63.6
XS GIS Cut Line= 4
     1799567.076      312466.675     1799608.309      312530.694
     1799705.965      312620.754     1799758.048      312684.774
#Sta/Elev= 30
       0  1593.7     3.8 1593.15      19 1594.86    30.5 1595.03    38.1 1594.16
    41.9 1593.25    49.5 1590.82    53.3 1590.02    57.1 1589.66    68.5 1589.94
    72.3 1589.74    87.9 1587.78    99.6 1586.97   111.3 1586.97   130.8 1586.25
   150.4 1586.09   162.1 1586.62   174.1 1584.08   181.6 1583.67   189.1 1584.23
   193.4 1585.96   197.3 1589.57   201.2 1592.54   220.8 1602.57   224.7  1605.6
   240.4 1621.15   248.3 1628.17   260.1 1635.56   267.9 1642.01   291.5 1659.61
#Mann= 3 , 0 , 0
       0     .08       0   174.1    .045       0   189.1      .1       0
Bank Sta=174.1,189.1
XS Rating Curve= 0 ,0
Exp/Cntr=0.3,0.1

Type RM Length L Ch R = 1 ,33197.3 ,263.5,261.2,259.1
XS GIS Cut Line= 3
     1799510.652      312579.522     1799585.522      312602.308
     1799728.751      312722.751
#Sta/Elev= 30
       0 1598.74    19.6 1596.74    58.7  1591.2    74.4 1590.23    82.2 1588.54
    90.2 1585.84    94.2 1585.44   110.1 1585.33   122.1 1584.41     126 1584.81
     134 1586.38     138 1586.13     146 1583.04   149.9 1582.32   153.9 1582.24
     164 1583.26   169.8 1584.18   173.8 1585.65   177.8 1588.01   189.8 1596.87
   197.7 1602.02   201.7 1605.45   209.7 1613.37   213.6 1616.68   225.6 1625.21
   237.5  1636.4   241.5 1639.59   245.5 1642.16   253.4 1649.04   265.4 1658.91
#Mann= 3 , 0 , 0
       0     .08       0     146    .045       0     164      .1       0
Bank Sta=146,164
XS Rating Curve= 0 ,0
Exp/Cntr=0.3,0.1

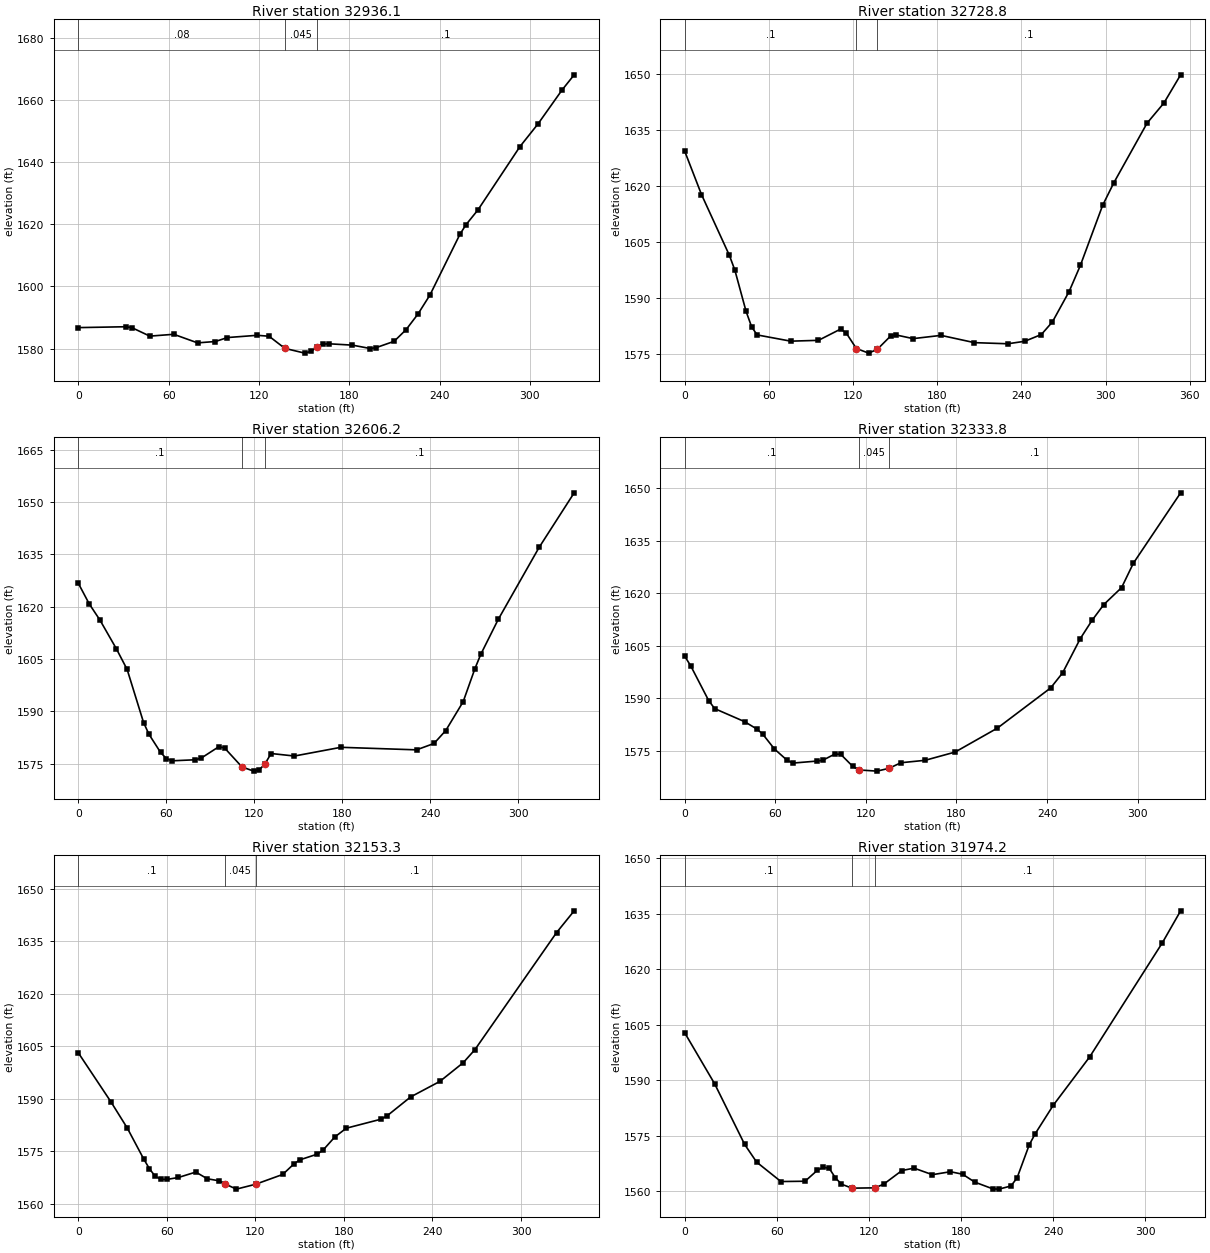
Type RM Length L Ch R = 1 ,32936.1 ,210.4,207.3,202.7
XS GIS Cut Line= 4
     1799373.934      312757.473     1799412.996      312807.386
      1799546.46      312899.617     1799628.925      312962.551
#Sta/Elev= 30
       0 1586.73    31.7 1587.01    35.6 1586.71    47.5 1583.99    63.4 1584.58
    79.2 1581.82    91.1 1582.26      99 1583.53   118.8 1584.25   126.7 1583.96
   137.2 1580.05   150.4 1578.52   154.4 1579.06   158.4 1580.38   162.3 1581.41
   166.3 1581.53   182.1 1581.09     194    1580   197.9  1580.3   209.8 1582.32
   217.7 1586.05   225.6 1591.07   233.6 1597.22   253.5 1616.74   257.5 1619.81
   265.5 1624.61   293.4 1644.98   305.4 1652.28   321.4 1663.21   329.4 1668.06
#Mann= 3 , 0 , 0
       0     .08       0   137.2    .045       0   158.4      .1       0
Bank Sta=137.2,158.4
XS Rating Curve= 0 ,0
Exp/Cntr=0.3,0.1

Type RM Length L Ch R = 1 ,32728.8 ,125.2,122.5,119.8
XS GIS Cut Line= 2
     1799235.045      312954.956     1799556.225      313102.525
#Sta/Elev= 30
       0 1629.25    11.9 1617.69    31.8 1601.37    35.7  1597.4    43.7 1586.34
    47.7 1582.16    51.6 1580.04    75.5 1578.37    95.3 1578.59   111.2 1581.63
   115.2 1580.49   122.3  1576.4   131.1 1575.16   137.3  1576.2   146.9 1579.81
   150.9 1580.01   162.8 1579.05   182.7 1579.92   206.5 1577.97   230.3 1577.67
   242.3 1578.33   254.2 1580.15   262.1 1583.54     274 1591.68     282 1598.66
   297.9 1614.79   305.8 1620.79   329.6 1636.85   341.6 1642.24   353.5 1649.79
#Mann= 3 , 0 , 0
       0      .1       0   122.3    .045       0   137.3      .1       0
Bank Sta=122.3,137.3
XS Rating Curve= 0 ,0
Exp/Cntr=0.3,0.1

Type RM Length L Ch R = 1 ,32606.2 ,272.8,272.5,271.2
XS GIS Cut Line= 4
     1799207.918      313093.845     1799254.576       313105.78
     1799435.783      313164.374     1799526.928      313204.522
#Sta/Elev= 30
       0 1626.68     7.4  1620.8    14.8  1616.1    25.9 1607.94    33.3 1601.97
    44.5 1586.76    48.2 1583.38    56.1 1578.19    60.1 1576.41      64 1575.79
    79.9 1576.09    83.9 1576.59    95.8 1579.82    99.7 1579.49   111.6 1574.04
   119.6 1572.83   123.5 1573.26   127.2 1574.84   131.5 1577.88   147.4 1577.16
   179.1 1579.66   230.7 1578.93   242.6 1580.76   250.6 1584.46   262.5 1592.74
   270.5  1602.2   274.5 1606.31   286.4 1616.32   314.3 1636.98   338.2 1652.62
#Mann= 3 , 0 , 0
       0      .1       0   111.6    .045       0   127.2      .1       0
Bank Sta=111.6,127.2
XS Rating Curve= 0 ,0
Exp/Cntr=0.3,0.1

Type RM Length L Ch R = 1 ,32333.8 ,171.7,180.4,186.9
XS GIS Cut Line= 4
     1799160.175      313356.432     1799215.513      313378.133
     1799365.253      313420.451      1799475.93      313445.407
#Sta/Elev= 30
       0 1602.03       4 1599.24    15.8  1589.4    19.8 1587.08    39.6 1583.36
    47.6 1581.29    51.5 1579.86    59.4 1575.54    67.4 1572.47    71.4 1571.51
    87.4 1572.09    91.4 1572.32    99.3 1574.08   103.3 1574.03   111.3 1570.56
   115.3 1569.56   127.3 1569.22   135.2 1570.01   143.2 1571.62   159.2 1572.31
   179.1 1574.67   207.1 1581.51   242.4    1593   250.3 1597.29     262 1607.07
   269.8  1612.3   277.6 1616.82   289.4 1621.67   297.2 1628.64   328.5 1648.75
#Mann= 3 , 0 , 0
       0      .1       0   115.3    .045       0   135.2      .1       0
Bank Sta=115.3,135.2
XS Rating Curve= 0 ,0
Exp/Cntr=0.3,0.1

Type RM Length L Ch R = 1 ,32153.3 ,176,179.1,182
XS GIS Cut Line= 4
     1799126.538      313466.024     1799152.579      313501.831
     1799263.257      313583.211     1799368.508      313696.058
#Sta/Elev= 30
       0 1603.11    22.1 1589.09    33.2 1581.57    44.3 1572.74    48.2 1569.95
    52.1 1567.78      56 1566.93      60 1566.89    67.8 1567.45    79.6    1569
    87.4 1567.08    95.3 1566.51    99.2 1565.65   107.1 1564.12   120.1 1565.51
   138.5 1568.32   146.3 1571.41   150.2 1572.51     162 1574.14     166 1575.36
   173.8 1579.04   181.6 1581.55   205.4 1584.16   209.4 1585.15   225.2  1590.5
     245 1594.94   260.8 1600.28   268.7    1604   324.1 1637.53     336 1643.74
#Mann= 3 , 0 , 0
       0      .1       0    99.2    .045       0   120.1      .1       0
Bank Sta=99.2,120.1
XS Rating Curve= 0 ,0
Exp/Cntr=0.3,0.1

Type RM Length L Ch R = 1 ,31974.2 ,189.6,189.4,189
XS GIS Cut Line= 3
      1799007.18      313600.572     1799045.158      313634.209
     1799249.151      313814.331
#Sta/Elev= 30
       0 1602.79    19.5 1589.01      39 1572.67    46.8 1567.91    62.6 1562.67
    78.3 1562.75    86.2 1565.66    90.2 1566.56    94.1  1566.2    98.1 1563.66
     102 1561.96   108.9 1560.88   123.9 1560.97   129.6 1561.98   141.4 1565.64
   149.3 1566.29   161.2 1564.52     173 1565.32   180.9 1564.65   188.8 1562.52
   200.6 1560.69   204.6 1560.62   212.4 1561.47   216.4 1563.66   224.3 1572.56
   228.2 1575.58     240 1583.29   263.7 1596.34     311 1627.13   322.9 1635.76
#Mann= 3 , 0 , 0
       0      .1       0   108.9    .045       0   123.9      .1       0
Bank Sta=108.9,123.9
XS Rating Curve= 0 ,0
Exp/Cntr=0.3,0.1

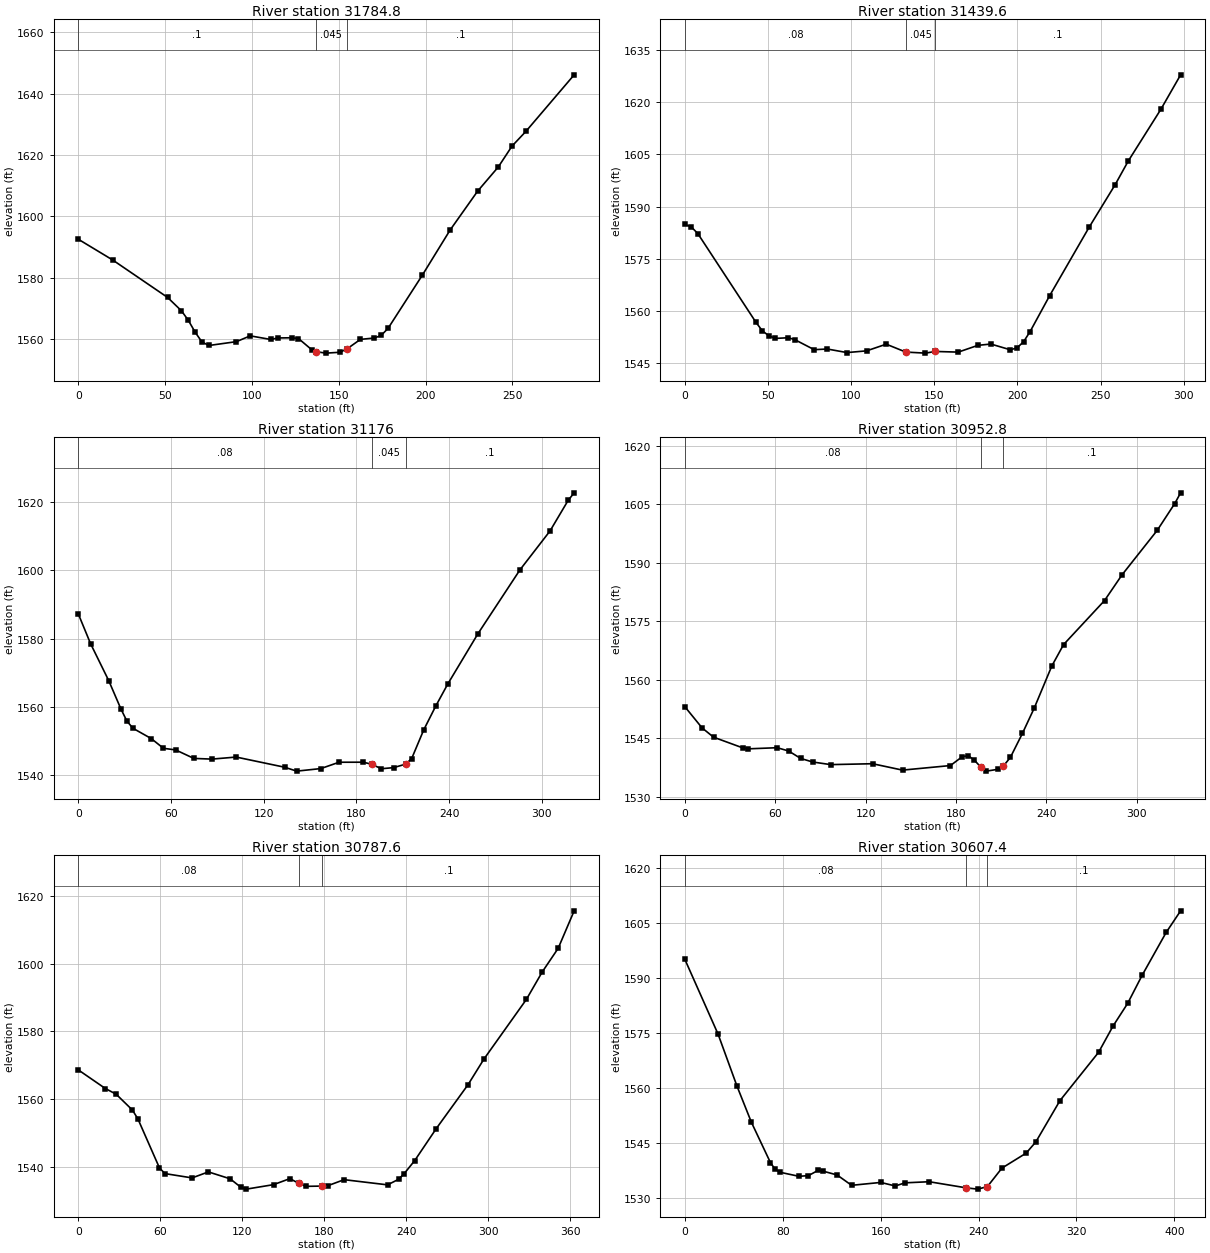
Type RM Length L Ch R = 1 ,31784.8 ,340.1,345.2,348.4
XS GIS Cut Line= 3
     1798934.481      313754.652     1798975.713       313807.82
     1799144.984      313945.624
#Sta/Elev= 30
       0 1592.49    19.8 1585.72    51.4 1573.51    59.4 1569.14    63.3 1566.08
    67.3 1562.15    71.2 1558.97    75.2 1557.82    91.1 1559.08      99 1560.97
   110.9 1559.78   114.9 1560.28   122.8 1560.34   126.8  1560.1   134.8 1556.27
   136.9 1555.79   142.7 1555.33   150.6 1555.61   154.6 1556.65   162.5 1559.82
   170.5 1560.26   174.4 1561.09   178.4 1563.41   198.2 1580.82   214.1 1595.46
     230 1608.19   241.9 1616.08   249.8 1622.89   257.8 1627.69   285.6 1646.15
#Mann= 3 , 0 , 0
       0      .1       0   136.9    .045       0   154.6      .1       0
Bank Sta=136.9,154.6
XS Rating Curve= 0 ,0
Exp/Cntr=0.3,0.1

Type RM Length L Ch R = 1 ,31439.6 ,262.4,263.6,263.2
XS GIS Cut Line= 3
     1798709.871      313993.367     1798754.359      314042.195
     1798901.928      314221.232
#Sta/Elev= 30
       0 1584.87     3.9 1584.14     7.8 1582.25    42.7 1556.81    46.6 1554.32
    50.5 1552.91    54.4 1552.13    62.2 1552.33    66.1 1551.79    77.8  1548.9
    85.7 1549.09    97.5 1548.07   109.3 1548.56   121.1 1550.48   132.9 1548.21
   144.7 1547.91   150.6 1548.39   164.4  1548.2   176.2 1550.14     184 1550.52
   195.8 1548.86   199.8 1549.44   203.7 1551.19   207.6  1554.1   219.4 1564.44
     243 1583.98   258.8 1596.32   266.6 1603.05   286.3 1617.97   298.1 1627.81
#Mann= 3 , 0 , 0
       0     .08       0   132.9    .045       0   150.6      .1       0
Bank Sta=132.9,150.6
XS Rating Curve= 0 ,0
Exp/Cntr=0.3,0.1

Type RM Length L Ch R = 1 ,31176   ,224.4,223.2,220.5
XS GIS Cut Line= 4
     1798508.048      314136.596     1798550.366      314183.254
     1798648.022      314305.867     1798681.659      314401.353
#Sta/Elev= 30
       0 1587.21     7.9 1578.51    19.7 1567.62    27.6 1559.29    31.5 1555.72
    35.4 1553.64    47.2 1550.63    55.1 1547.77      63  1547.3    74.8  1544.8
    86.5  1544.6   102.2  1545.2   133.5 1542.22   141.4 1541.07     157 1541.82
   168.8 1543.68   184.5 1543.69   189.8  1543.1   196.2 1541.77   204.1  1542.1
   211.9 1543.12   215.8 1544.75   223.6 1553.17   231.4 1560.18   239.2 1566.67
   258.7 1581.41   285.9 1600.16   305.4  1611.6   317.1 1620.56     321 1622.78
#Mann= 3 , 0 , 0
       0     .08       0   189.8    .045       0   211.9      .1       0
Bank Sta=189.8,211.9
XS Rating Curve= 0 ,0
Exp/Cntr=0.3,0.1

Type RM Length L Ch R = 1 ,30952.8 ,162.8,165.2,166.8
XS GIS Cut Line= 4
     1798362.649      314290.676     1798400.626      314348.185
     1798505.878      314467.543     1798555.791      314555.433
#Sta/Elev= 30
       0 1553.09    11.5 1547.62    19.1 1545.25    38.3 1542.53    42.1 1542.26
    61.3 1542.55    68.9 1541.71    76.9  1539.8    84.8 1538.89    96.8 1538.21
   124.6 1538.44   144.5  1536.8   176.3 1537.97   184.3 1540.29   188.3 1540.45
   192.2 1539.35   196.5 1537.56   200.2 1536.54   208.2 1537.03   211.5 1537.87
   216.1 1540.06   224.1 1546.23   231.9 1552.69   243.6 1563.52   251.4 1569.01
   278.6 1580.32   290.2 1586.91   313.6 1598.35   325.2 1605.21   329.1 1607.96
#Mann= 3 , 0 , 0
       0     .08       0   196.5    .045       0   211.5      .1       0
Bank Sta=196.5,211.5
XS Rating Curve= 0 ,0
Exp/Cntr=0.3,0.1

Type RM Length L Ch R = 1 ,30787.6 ,184.2,180.2,175.9
XS GIS Cut Line= 4
     1798262.823      314395.928     1798284.524      314446.926
     1798399.541      314604.261     1798453.795      314703.003
#Sta/Elev= 30
       0 1568.66    19.8 1563.17    27.7 1561.49    39.6 1556.82    43.6 1554.22
    59.4 1539.75    63.4 1538.08    83.3 1536.81    95.2 1538.58   111.1 1536.55
   119.1 1534.02     123  1533.5   142.9 1534.82   154.9  1536.6   161.3 1535.22
   166.8 1534.32   178.7  1534.4   182.7 1534.52   194.6 1536.29   226.4 1534.76
   234.4 1536.39   238.4 1537.99   246.3 1541.94     262 1551.33   285.3  1564.3
   296.9 1571.83     328 1589.44   339.7  1597.6   351.3 1604.53     363 1615.58
#Mann= 3 , 0 , 0
       0     .08       0   161.3    .045       0   178.7      .1       0
Bank Sta=161.3,178.7
XS Rating Curve= 0 ,0
Exp/Cntr=0.3,0.1

Type RM Length L Ch R = 1 ,30607.4 ,255.5,256.2,254.6
XS GIS Cut Line= 4
      1798067.51      314484.904      1798138.04       314582.56
     1798264.993      314701.918      1798307.31      314803.914
#Sta/Elev= 30
       0 1595.07    27.2  1574.6    42.7 1560.36    54.4 1550.55      70 1539.51
    73.8 1537.71    77.7  1536.9    93.3 1535.79     101 1535.98   108.8 1537.39
   112.7 1537.22   124.4 1536.16   136.3 1533.33   160.1 1534.12     172 1533.15
   179.9 1534.01   199.7 1534.31   229.9 1532.64   239.3 1532.29   247.2 1532.97
   259.1 1538.03   278.9 1542.12   286.8 1545.18   306.5 1556.45   338.1 1569.66
   349.9 1576.83   361.8 1582.99   373.6 1590.65   393.3 1602.39   405.1 1608.28
#Mann= 3 , 0 , 0
       0     .08       0   229.9    .045       0   247.2      .1       0
Bank Sta=229.9,247.2
XS Rating Curve= 0 ,0
Exp/Cntr=0.3,0.1

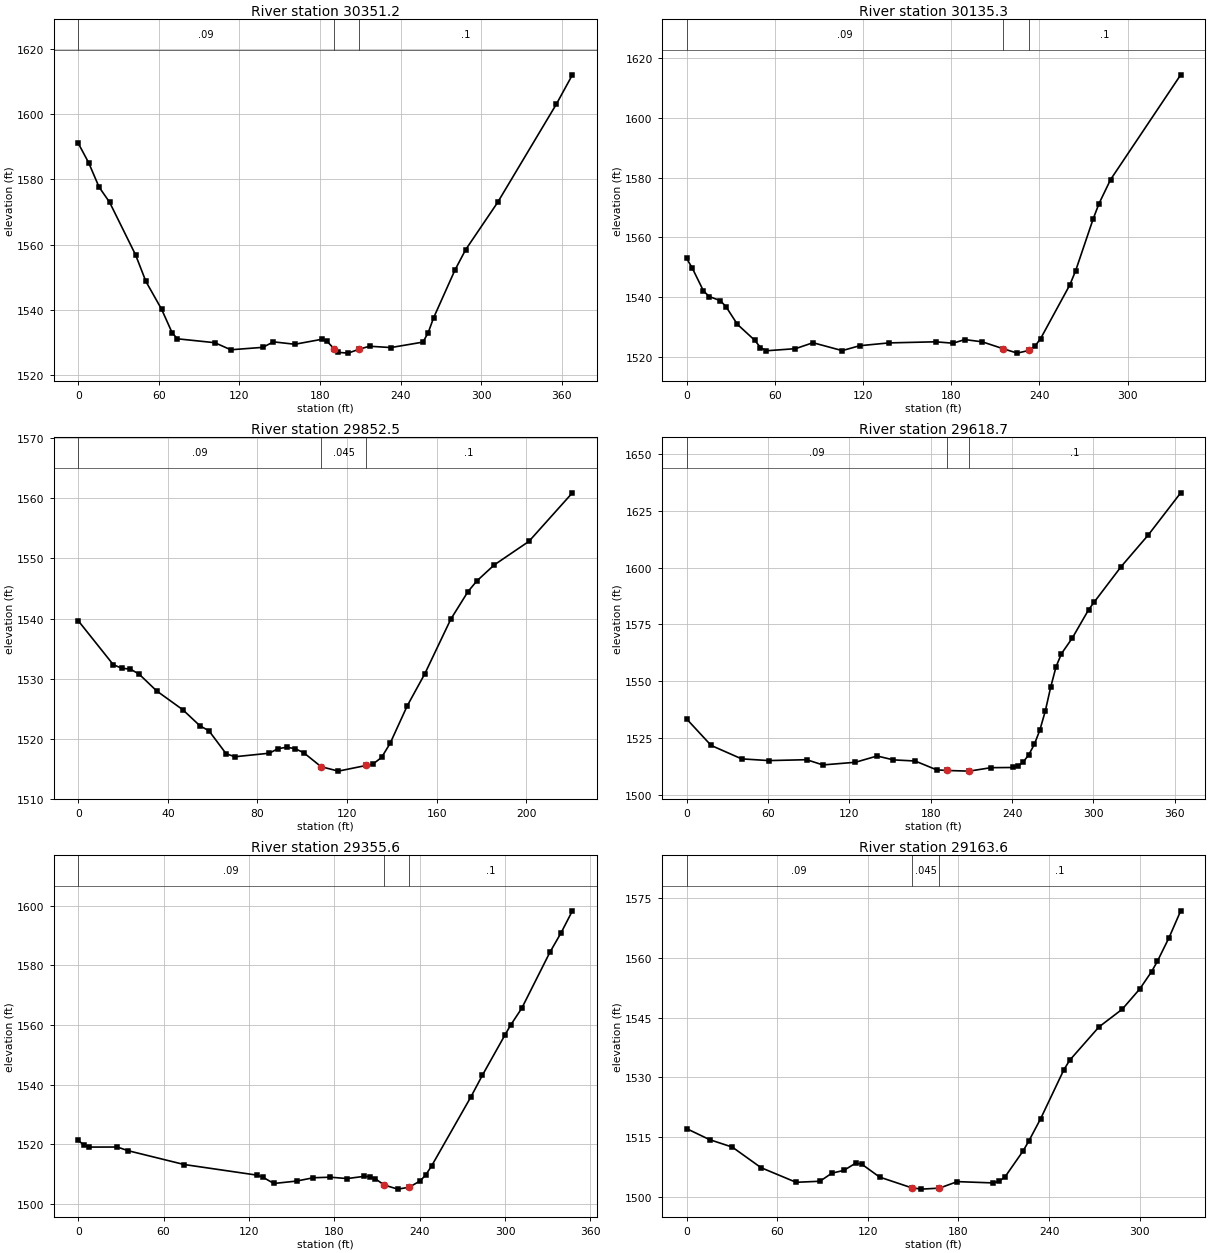
Type RM Length L Ch R = 1 ,30351.2 ,214.4,215.9,216
XS GIS Cut Line= 3
     1797878.708      314672.621     1797929.706      314720.364
      1798151.06      314920.017
#Sta/Elev= 30
       0 1591.08     7.8 1585.06    15.5 1577.63    23.3    1573    42.7 1556.82
    50.4 1548.66    62.1 1540.12    69.9 1532.94    73.8 1531.08   101.7 1529.88
   113.6 1527.71   137.4 1528.45   145.4 1530.14   161.3  1529.4   181.2 1530.91
   185.1  1530.4   190.6 1527.96   193.1 1526.93     201 1526.68     209 1527.86
   216.9 1528.79   232.8 1528.39   256.7 1530.06   260.6 1532.95   264.6 1537.48
   280.5 1552.14   288.5 1558.42   312.3 1572.91     356 1603.03     368 1612.07
#Mann= 3 , 0 , 0
       0     .09       0   190.6    .045       0     209      .1       0
Bank Sta=190.6,209
XS Rating Curve= 0 ,0
Exp/Cntr=0.3,0.1

Type RM Length L Ch R = 1 ,30135.3 ,286.8,282.8,276.9
XS GIS Cut Line= 3
     1797786.477      314840.807     1797812.519      314869.018
     1798028.448      315074.096
#Sta/Elev= 30
       0 1552.98     3.8 1549.82    11.5 1542.09    15.4 1540.22      23 1538.82
    26.9 1536.77    34.6  1530.9    46.3 1525.62    50.3 1523.16    54.3 1522.07
    74.1 1522.77      86 1524.76   105.9 1522.12   117.8 1523.76   137.7  1524.7
   169.4 1525.07   181.3  1524.6   189.3 1525.81   201.2 1525.06   215.6 1522.72
     225 1521.28     233  1522.2   236.9 1523.51   240.9 1526.16   260.8 1544.14
   264.7 1548.83   276.6 1566.12   280.6 1571.29   288.5 1579.35   336.2 1614.38
#Mann= 3 , 0 , 0
       0     .09       0   215.6    .045       0     233      .1       0
Bank Sta=215.6,233
XS Rating Curve= 0 ,0
Exp/Cntr=0.3,0.1

Type RM Length L Ch R = 1 ,29852.5 ,226,233.8,241.6
XS GIS Cut Line= 4
     1797642.163      315104.478      1797682.31      315146.796
     1797758.265      315192.369     1797810.349      315244.452
#Sta/Elev= 30
       0 1539.63    15.6 1532.34    19.4 1531.73    23.3 1531.58    27.2 1530.74
      35 1527.96    46.7 1524.82    54.4 1522.13    58.3 1521.35      66 1517.52
    69.9 1517.01    85.3  1517.6    89.1 1518.34      93 1518.59    96.8 1518.36
   100.7 1517.67   108.4 1515.36   116.1 1514.62   128.5 1515.56   131.5 1515.78
   135.4 1516.89   139.2 1519.22   146.9  1525.5   154.7  1530.8   166.3 1539.88
     174 1544.48   177.9 1546.23   185.7 1548.91   201.2 1552.83   220.6  1560.9
#Mann= 3 , 0 , 0
       0     .09       0   108.4    .045       0   128.5      .1       0
Bank Sta=108.4,128.5
XS Rating Curve= 0 ,0
Exp/Cntr=0.3,0.1

Type RM Length L Ch R = 1 ,29618.7 ,265.7,263,259.8
XS GIS Cut Line= 3
     1797496.763      315232.517      1797513.04      315260.728
     1797737.649      315504.869
#Sta/Elev= 30
       0  1533.4    18.1 1521.72    40.6  1515.8    60.6 1515.04    88.5 1515.43
   100.5 1513.13   124.5  1514.3   140.5 1517.06   152.5 1515.35   168.5 1514.86
   184.4 1510.96   192.1 1510.68   208.4  1510.4   224.4 1511.92   240.4    1512
   244.4 1512.64   248.4 1514.54   252.4 1517.72   256.4 1522.21   260.4 1528.36
   264.4 1536.69   268.4 1547.24   272.4 1556.36   276.4 1562.12   284.4 1569.01
   296.4 1581.45   300.4 1584.73   320.4 1600.45   340.3  1614.3   364.3 1632.92
#Mann= 3 , 0 , 0
       0     .09       0   192.1    .045       0   208.4      .1       0
Bank Sta=192.1,208.4
XS Rating Curve= 0 ,0
Exp/Cntr=0.3,0.1

Type RM Length L Ch R = 1 ,29355.6 ,199.6,192.1,185.1
XS GIS Cut Line= 3
     1797346.807       315434.34     1797402.145      315510.294
     1797587.692       315682.82
#Sta/Elev= 30
       0 1521.25     3.9 1519.75     7.8 1519.04    27.4 1519.06    35.2 1517.81
    74.4  1513.2   125.6 1509.64   129.6 1508.98   137.5 1506.84   153.4 1507.65
   165.2 1508.76   177.1 1508.95     189 1508.49   200.9 1509.23   204.8 1509.14
   208.8 1508.41   215.1 1506.31   224.6 1504.95   232.5 1505.58   240.4 1507.72
   244.4 1509.83   248.4 1512.77   276.1 1535.98     284 1543.09   299.8 1556.52
   303.8 1559.85   311.7 1565.57   331.5 1584.34   339.4  1590.9   347.3 1598.22
#Mann= 3 , 0 , 0
       0     .09       0   215.1    .045       0   232.5      .1       0
Bank Sta=215.1,232.5
XS Rating Curve= 0 ,0
Exp/Cntr=0.3,0.1

Type RM Length L Ch R = 1 ,29163.6 ,156.8,159.4,161.4
XS GIS Cut Line= 4
     1797225.496      315641.588     1797269.984       315682.82
     1797417.553      315758.775     1797506.529      315805.433
#Sta/Elev= 30
       0  1517.1    15.2 1514.33    30.3 1512.44    49.3 1507.27    72.5 1503.59
    88.3 1503.85    96.2 1505.89   104.1 1506.58     112 1508.42     116 1508.14
   127.8  1504.9   148.9 1502.22   155.5 1501.87   167.4 1502.12   179.2 1503.76
   202.9 1503.43   206.9 1503.84   210.8 1504.95   222.7 1511.44   226.6    1514
   234.4  1519.6   249.8 1531.94   253.7 1534.34     273 1542.68   288.4 1547.14
     300 1552.23   307.8 1556.58   311.6 1559.15   319.4 1565.16   327.1 1571.89
#Mann= 3 , 0 , 0
       0     .09       0   148.9    .045       0   167.4      .1       0
Bank Sta=148.9,167.4
XS Rating Curve= 0 ,0
Exp/Cntr=0.3,0.1

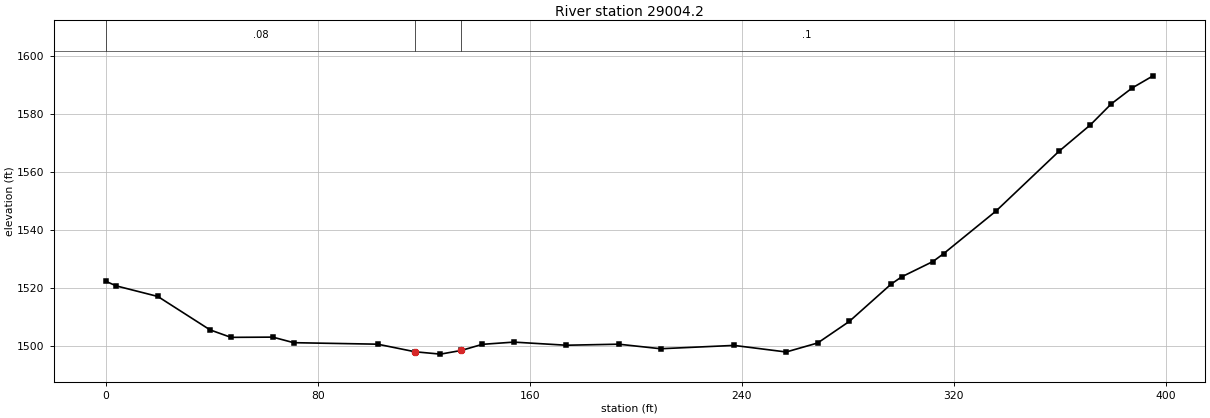
Type RM Length L Ch R = 1 ,29004.2 ,282.3,283.8,281.8
XS GIS Cut Line= 3
     1797126.755      315767.456     1797164.732      315788.072
     1797468.552      315966.024
#Sta/Elev= 30
       0 1522.33     3.9 1520.75    19.6  1517.1    39.3 1505.57    47.2 1502.98
      63 1503.06    70.9 1501.14   102.6 1500.62   116.7    1498   126.3 1497.19
   134.2 1498.47   142.1 1500.57     154 1501.34   173.8 1500.26   193.6 1500.62
   209.4 1499.05   237.1  1500.2   256.8 1497.93   268.7 1501.04   280.6 1508.46
   296.4 1521.35   300.4 1523.87   312.2 1529.16   316.2 1531.85     336 1546.58
   359.7 1567.15   371.6  1576.3   379.5 1583.56   387.4 1589.07   395.3 1593.27
#Mann= 3 , 0 , 0
       0     .08       0   116.7    .045       0   134.2      .1       0
Bank Sta=116.7,134.2
XS Rating Curve= 0 ,0
Exp/Cntr=0.3,0.1