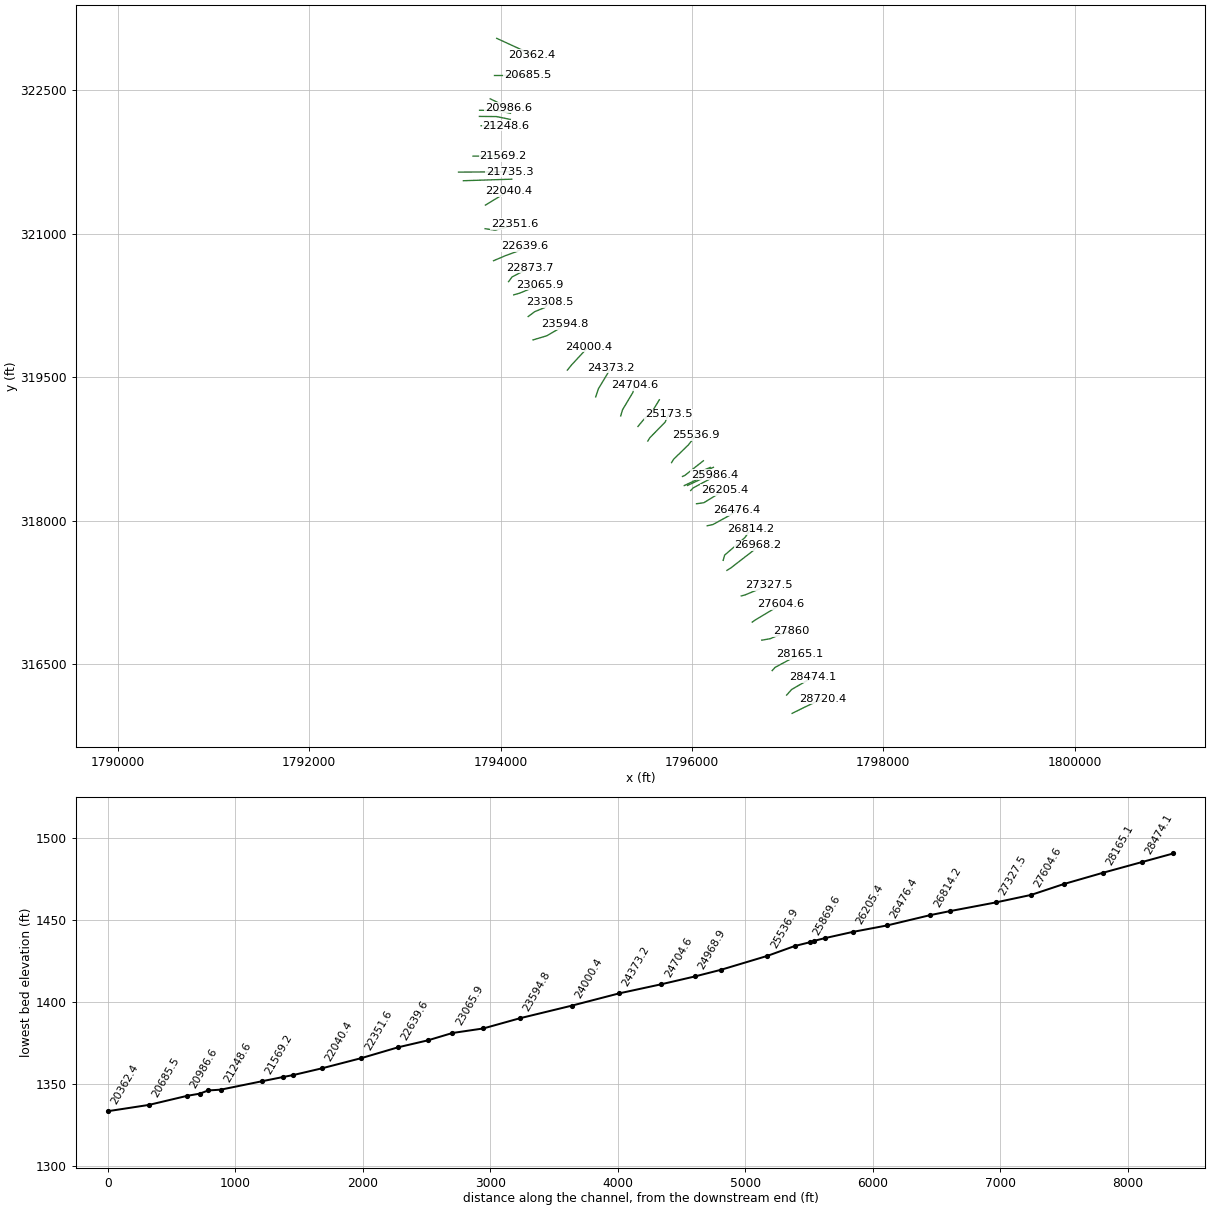
HEC-RAS study WESTFK1.prj: WESTFK1

--- WESTFK1.g01 (geometry) --- (continued)

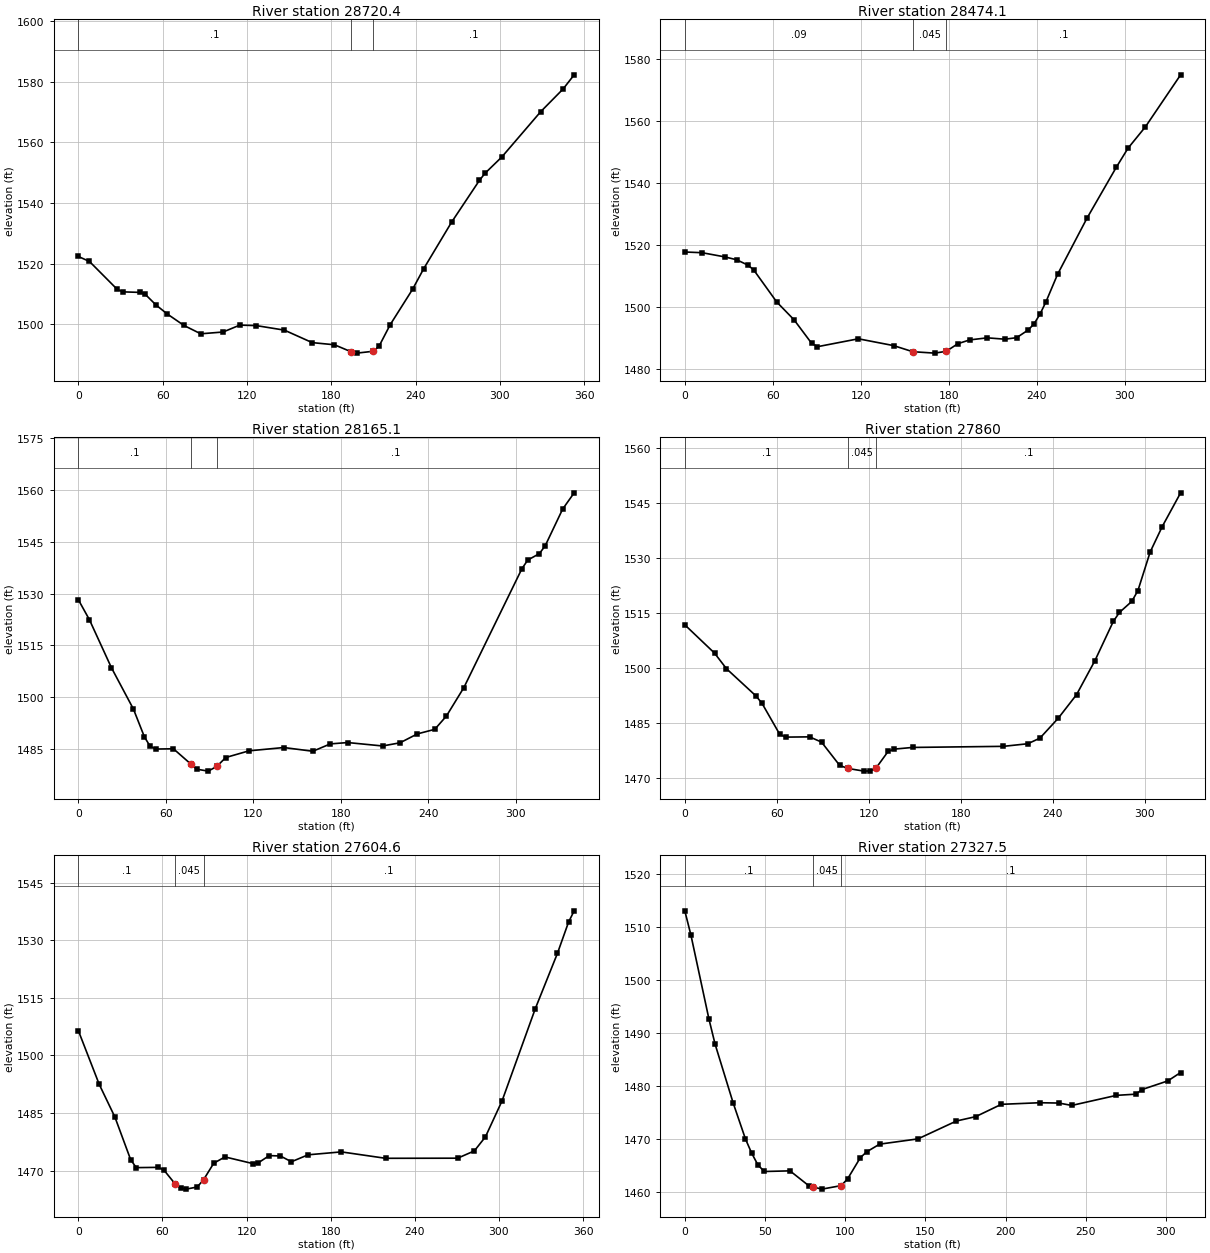
Type RM Length L Ch R = 1 ,28720.4 ,247.6,246.3,246.7
XS GIS Cut Line= 3
     1797047.545       315988.81     1797178.838      316053.914
      1797365.47      316141.805
#Sta/Elev= 30
       0 1522.38     7.9 1520.74    27.7 1511.51    31.7  1510.7    43.6 1510.53
    47.5 1509.94    55.4 1506.31    63.4 1503.36    75.2  1499.6    87.1 1496.86
     103 1497.45   114.9 1499.73   126.7 1499.56   146.6 1498.07   166.4 1493.95
   182.2 1493.24   194.2 1490.91   198.1 1490.48     210  1491.1     214 1492.79
   221.9 1499.86   237.8 1511.53   245.7 1518.31   265.6 1533.71   285.4  1547.5
   289.4 1549.85   301.3  1555.2     329 1570.17   344.9 1577.64   352.8 1582.33
#Mann= 3 , 0 , 0
       0      .1       0   194.2    .045       0     210      .1       0
Bank Sta=194.2,210
XS Rating Curve= 0 ,0
Exp/Cntr=0.3,0.1

Type RM Length L Ch R = 1 ,28474.1 ,305.2,309,308.6
XS GIS Cut Line= 3
     1796990.036      316179.782     1797042.119      316238.376
     1797266.729      316368.584
#Sta/Elev= 30
       0 1517.82    11.8 1517.59    27.4 1516.23    35.3 1515.32    43.1 1513.58
      47 1512.02    62.7 1501.69    74.5 1495.95    86.4 1488.42    90.4 1487.29
   118.3 1489.84   142.3 1487.65   155.4 1485.68   170.3 1485.22   178.2  1485.8
   186.2 1488.27   194.2 1489.48   206.2 1490.15   218.2 1489.71   226.2  1490.2
   234.2 1492.71   238.2 1494.74   242.2 1497.84   246.2 1501.76   254.1 1510.61
   274.1 1528.66   294.1 1545.09   302.1 1551.25     314 1558.17     338 1574.93
#Mann= 3 , 0 , 0
       0     .09       0   155.4    .045       0   178.2      .1       0
Bank Sta=155.4,178.2
XS Rating Curve= 0 ,0
Exp/Cntr=0.3,0.1

Type RM Length L Ch R = 1 ,28165.1 ,306.9,305.2,302.8
XS GIS Cut Line= 3
     1796839.211      316435.859     1796869.593      316469.496
     1797128.925       316609.47
#Sta/Elev= 30
       0 1528.23     7.6 1522.44    22.7 1508.54    37.8 1496.56    45.3 1488.54
    49.3 1485.75    53.3 1485.01    65.2 1485.09    77.2 1480.65    81.2 1479.18
    89.1 1478.62      95    1480   101.1 1482.56     117 1484.49   140.9 1485.45
   160.8 1484.37   172.8  1486.5   184.7 1486.89   208.6  1485.9   220.6 1486.82
   232.5  1489.4   244.4 1490.71   252.4 1494.56   264.4 1502.82   304.2 1537.22
   308.2 1539.71   316.1 1541.55   320.1  1543.8   332.1 1554.45     340 1559.16
#Mann= 3 , 0 , 0
       0      .1       0    77.2    .045       0      95      .1       0
Bank Sta=77.2,95
XS Rating Curve= 0 ,0
Exp/Cntr=0.3,0.1

Type RM Length L Ch R = 1 ,27860   ,252.4,255.3,258.8
XS GIS Cut Line= 4
     1796729.619      316753.784      1796817.51      316768.975
     1796948.803      316824.313     1797037.779        316847.1
#Sta/Elev= 30
       0 1511.75    19.4 1504.02    27.2 1499.76    46.5  1492.3    50.4 1490.29
      62  1481.8    65.9 1481.08    81.4 1481.15    89.2 1479.72   101.1 1473.33
   106.6 1472.51   116.9 1471.79   120.9 1471.85   124.8 1472.64   132.7  1477.2
   136.7  1477.8   148.6 1478.26   207.9 1478.56   223.8 1479.27   231.7  1480.8
   243.6 1486.21   255.6 1492.68   267.6 1501.98   279.6  1512.7   283.6 1515.14
   291.6 1518.13   295.6 1521.06   303.6 1531.61   311.5 1538.59   323.5  1547.8
#Mann= 3 , 0 , 0
       0      .1       0   106.6    .045       0   124.8      .1       0
Bank Sta=106.6,124.8
XS Rating Curve= 0 ,0
Exp/Cntr=0.3,0.1

Type RM Length L Ch R = 1 ,27604.6 ,280.1,277.2,273.3
XS GIS Cut Line= 3
     1796630.878      316942.586      1796661.26      316964.287
     1796932.527      317127.048
#Sta/Elev= 30
       0 1506.48    14.9 1492.48    26.1 1483.95    37.3 1472.89    41.3 1470.79
    57.1 1470.86    61.1 1470.13      69 1466.57    72.9 1465.47    76.9 1465.19
    84.8 1465.74    89.3 1467.62    96.6 1471.94   104.6 1473.58   124.3 1471.86
   128.3 1472.03   136.2 1473.92   144.1 1473.83     152 1472.32   163.9 1474.13
   187.6 1474.89   219.2 1473.22   270.6 1473.25   282.5 1475.15   290.4  1478.8
   302.3 1488.21     326 1512.22   341.8 1526.63   349.7 1534.74   353.7 1537.68
#Mann= 3 , 0 , 0
       0      .1       0      69    .045       0    89.3      .1       0
Bank Sta=69,89.3
XS Rating Curve= 0 ,0
Exp/Cntr=0.3,0.1

Type RM Length L Ch R = 1 ,27327.5 ,352.7,359.2,365.2
XS GIS Cut Line= 3
     1796515.861      317216.024     1796556.008      317226.874
     1796803.404      317328.871
#Sta/Elev= 30
       0 1513.01     3.8 1508.47    15.1 1492.57    18.9 1487.89    30.2 1476.79
    37.8 1470.07    41.6 1467.44    45.6 1465.15    49.6 1463.92    65.6 1464.04
    77.5  1461.2    79.9 1461.01    85.5  1460.6    97.5 1461.26   101.5 1462.52
   109.5 1466.54   113.5 1467.64   121.5 1469.07   145.4 1470.06   169.4 1473.43
   181.4 1474.25   197.4 1476.57   221.3 1476.87   233.3 1476.81   241.3 1476.36
   269.2 1478.26   281.2 1478.48   285.2 1479.36   301.2 1480.98   309.2 1482.56
#Mann= 3 , 0 , 0
       0      .1       0    79.9    .045       0    97.5      .1       0
Bank Sta=79.9,97.5
XS Rating Curve= 0 ,0
Exp/Cntr=0.3,0.1

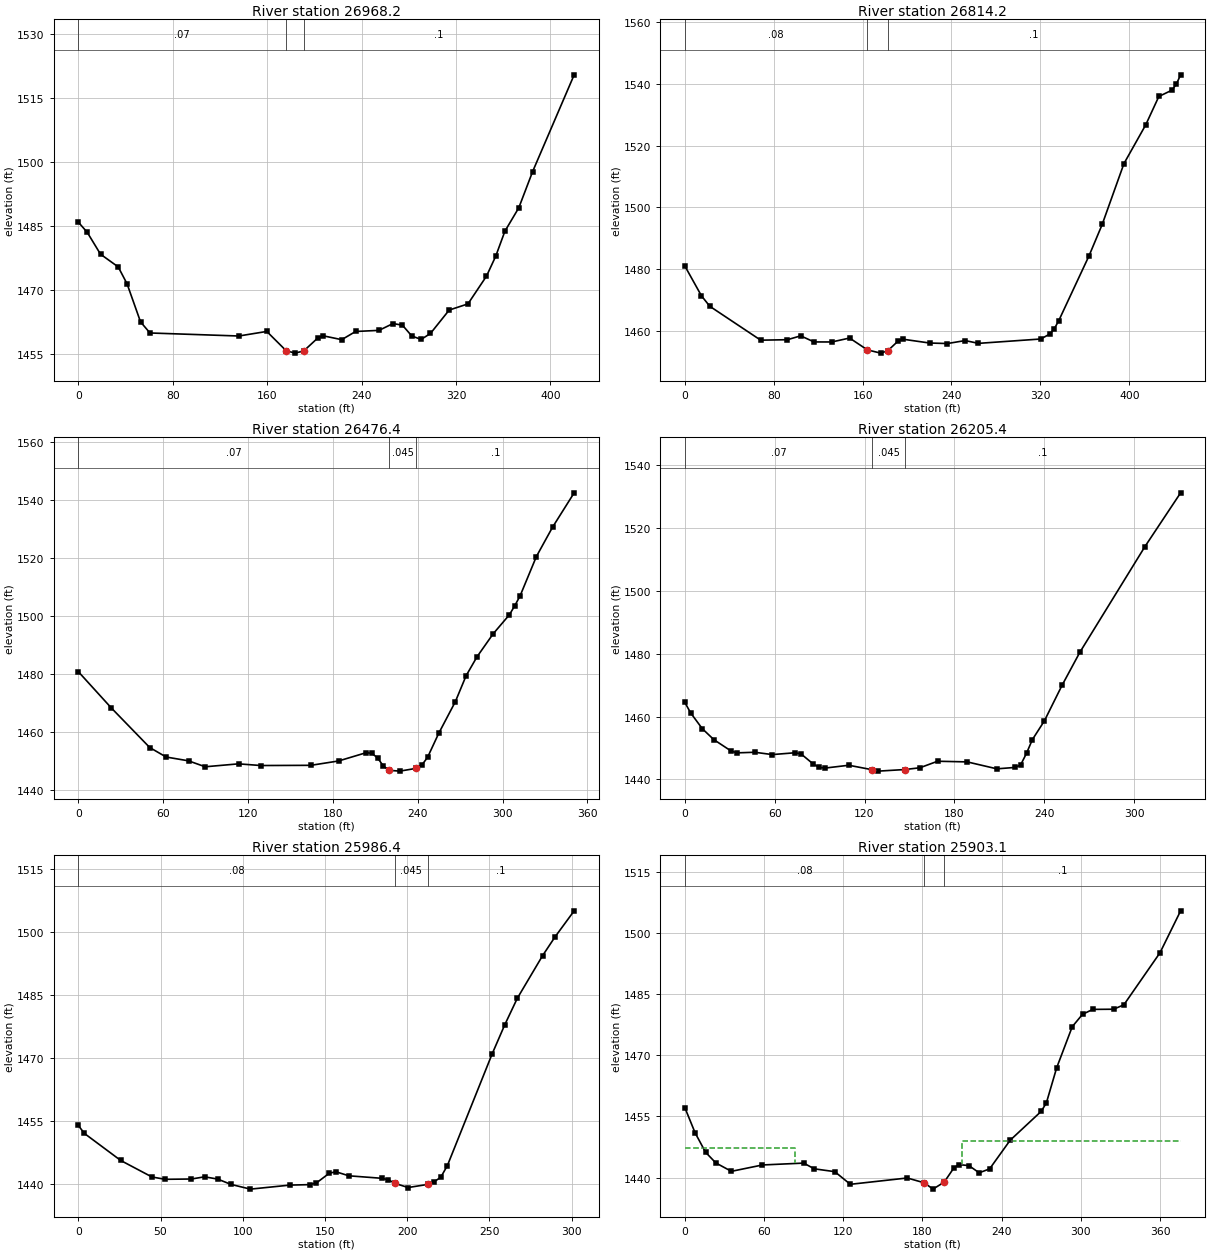
Type RM Length L Ch R = 1 ,26968.2 ,153.2,154.1,155.4
XS GIS Cut Line= 4
     1796366.121      317482.951     1796407.354      317508.992
     1796636.303      317685.859     1796692.727      317745.537
#Sta/Elev= 30
       0 1485.98     7.5 1483.62    18.8 1478.48    33.8  1475.5    41.3 1471.54
    52.7 1462.64    60.7 1460.03     136 1459.32   159.7 1460.39     176 1455.91
   183.5 1455.31     191 1455.81   203.3 1458.95   207.3 1459.38   223.2 1458.46
     235 1460.38   254.8 1460.64   266.7 1462.24   274.7 1461.85   282.6 1459.32
   290.5 1458.52   298.4 1459.91   314.3  1465.4   330.2 1466.84   345.9 1473.34
   353.7 1477.99   361.5 1483.86   373.3 1489.36     385 1497.83   420.2 1520.49
#Mann= 3 , 0 , 0
       0     .07       0     176    .045       0     191      .1       0
Bank Sta=176,191
XS Rating Curve= 0 ,0
Exp/Cntr=0.3,0.1

Type RM Length L Ch R = 1 ,26814.2 ,341.7,337.8,332.3
XS GIS Cut Line= 4
     1796327.059      317588.202      1796342.25      317642.456
     1796553.838      317825.833     1796616.772      317915.893
#Sta/Elev= 30
       0 1481.09      15 1471.41    22.5 1468.03    68.3 1457.07    92.3 1457.22
   104.3 1458.47   116.3  1456.5   132.3 1456.49   148.3 1457.76   164.3 1453.93
   176.3 1452.88   182.6 1453.64   192.3  1456.9   196.3 1457.38   220.3 1456.15
   236.3 1455.98   252.3 1456.94   264.3 1456.04   320.3 1457.45   328.3 1459.02
   332.3 1460.64   336.3 1463.21   363.8 1484.38   375.6 1494.49   395.2 1514.19
   414.8 1526.72   426.6  1535.9   438.4 1537.94   442.3 1539.86   446.2  1542.9
#Mann= 3 , 0 , 0
       0     .08       0   164.3    .045       0   182.6      .1       0
Bank Sta=164.3,182.6
XS Rating Curve= 0 ,0
Exp/Cntr=0.3,0.1

Type RM Length L Ch R = 1 ,26476.4 ,269.2,271,270.6
XS GIS Cut Line= 4
     1796159.958       317949.53     1796220.722      317962.551
     1796399.758      318061.293     1796468.118      318110.121
#Sta/Elev= 30
       0 1480.88    23.3 1468.39    50.5 1454.73    62.1 1451.46    77.9 1450.15
    89.7  1448.1   113.3 1449.11     129 1448.53   164.4  1448.6     184  1450.1
   203.7 1452.98   207.6 1452.72   211.6 1451.15   215.5 1448.49   219.4 1446.89
   227.3  1446.6   239.1 1447.57     243 1448.77   246.9 1451.31   254.8  1459.6
   266.6 1470.55   274.2 1479.48   281.9    1486   293.3 1493.91   304.8 1500.49
   308.6  1503.6   312.4 1507.04   323.9 1520.57   335.3 1530.66   350.6 1542.52
#Mann= 3 , 0 , 0
       0     .07       0   219.4    .045       0   239.1      .1       0
Bank Sta=219.4,239.1
XS Rating Curve= 0 ,0
Exp/Cntr=0.3,0.1

Type RM Length L Ch R = 1 ,26205.4 ,219.6,219,217.5
XS GIS Cut Line= 3
     1796048.196      318179.565     1796125.236      318190.416
     1796341.165      318322.794
#Sta/Elev= 30
       0 1464.53     3.9 1461.17    11.7 1456.13    19.4 1452.65    31.1 1448.97
      35 1448.44    46.7 1448.63    58.4 1447.89    73.9 1448.48    77.8 1448.04
    85.7 1444.91    89.7 1443.83    93.6 1443.59   109.5 1444.49   125.3 1443.05
   129.2 1442.62     147 1443.13     157 1443.69   168.8 1445.77   188.6 1445.56
   208.4 1443.35   220.3 1443.79   224.2 1444.54   228.2 1448.32   232.1 1452.66
   240.1 1458.61   251.9 1469.94   263.8 1480.47   307.3 1514.17   331.1 1531.27
#Mann= 3 , 0 , 0
       0     .07       0   125.3    .045       0     147      .1       0
Bank Sta=125.3,147
XS Rating Curve= 0 ,0
Exp/Cntr=0.3,0.1

Type RM Length L Ch R = 1 ,25986.4 ,53.2,83.3,113.2
XS GIS Cut Line= 4
     1795987.432      318317.369     1796012.388      318344.496
     1796184.915      318436.727     1796234.828       318484.47
#Sta/Elev= 30
       0 1453.98     3.7 1452.08    25.8 1445.64    44.8 1441.71    52.8 1441.16
    68.8 1441.23    76.8 1441.75    84.8 1441.21    92.8 1439.95   104.7 1438.82
   128.7 1439.78   140.7 1439.89   144.7 1440.26   152.6 1442.59   156.6 1442.96
   164.6 1441.99   184.6  1441.4   188.6 1441.04   192.6 1440.19   200.6  1439.2
   212.5 1439.94   216.5 1440.58   220.5 1441.67   224.5 1444.44   251.7 1471.01
   259.4 1477.96     267 1484.25   282.4 1494.42     290  1498.9   301.6 1505.09
#Mann= 3 , 0 , 0
       0     .08       0   192.6    .045       0   212.5      .1       0
Bank Sta=192.6,212.5
XS Rating Curve= 0 ,0
Exp/Cntr=0.3,0.1

Type RM Length L Ch R = 1 ,25903.1 ,33.6,33.5,33.4
XS GIS Cut Line= 4
     1795953.795      318370.537     1796099.194      318438.897
     1796085.088      318499.661     1796225.062      318560.425
#Sta/Elev= 30
       0 1457.19     7.8 1450.99    15.7 1446.24    23.5 1443.61    35.3 1441.55
    58.8 1443.11    90.1 1443.57      98 1442.17   113.6 1441.47   125.4 1438.37
   168.5 1439.92   181.5 1438.73     188 1437.19   196.5 1438.91   203.6 1442.28
   207.4  1443.2   215.2 1442.96     223 1441.19   230.9 1442.15   246.5 1449.18
     270 1456.25   273.9 1458.32   281.7 1466.92   293.5 1476.99   301.3 1480.03
   309.1 1481.23   324.8 1481.27   332.6 1482.35     360 1495.12   375.6 1505.38
#Mann= 3 , 0 , 0
       0     .08       0   181.5    .045       0   196.5      .1       0
#XS Ineff= 2 , 0
           83.26 1447.24   210.1         1448.88
Permanent Ineff=
       F       F
Bank Sta=181.5,196.5
XS Rating Curve= 0 ,0
Exp/Cntr=0.3,0.1

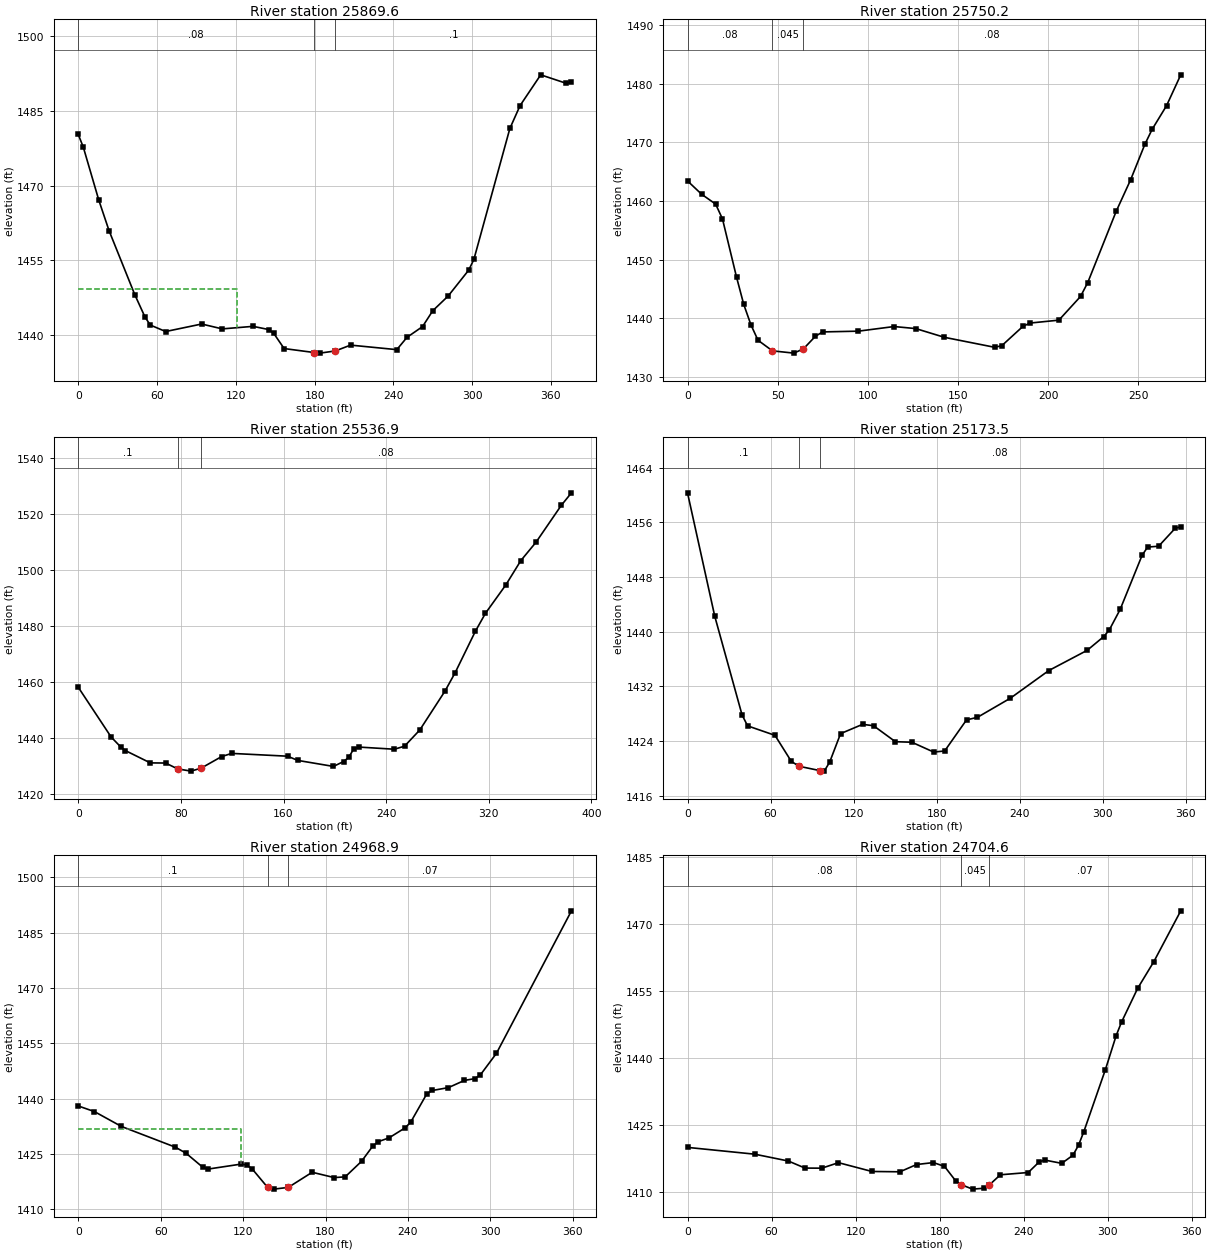
Type RM Length L Ch R = 1 ,25869.6 ,145,119.4,93.8
XS GIS Cut Line= 4
     1795920.158      318369.452     1796065.557      318437.812
     1796051.451      318498.576     1796191.425       318559.34
#Sta/Elev= 30
       0 1480.29     3.9  1477.7    15.7 1467.06    23.5 1460.93    43.1 1448.07
    50.9 1443.56    54.9 1441.97    66.6 1440.67      94 1442.18   109.7  1441.2
   133.2 1441.71     145 1441.07   148.9  1440.3   156.8 1437.25   179.7 1436.45
   184.1 1436.33   195.8 1436.77   207.4 1437.94   242.6 1437.03   250.4 1439.51
   262.2 1441.66     270 1444.85   281.7  1447.8   297.4 1453.02   301.3 1455.16
   328.7 1481.47   336.5 1486.08   352.2 1492.25   371.7 1490.54   375.6 1490.83
#Mann= 3 , 0 , 0
       0     .08       0   179.7    .045       0   195.8      .1       0
#XS Ineff= 2 , 0
          120.81  1449.2
Permanent Ineff=
       F       F
Bank Sta=179.7,195.8
XS Rating Curve= 0 ,0
Exp/Cntr=0.3,0.1

Type RM Length L Ch R = 1 ,25750.2 ,210.9,213.3,215.4
XS GIS Cut Line= 3
     1795901.711      318464.938     1795926.668      318475.789
      1796119.81      318628.784
#Sta/Elev= 30
       0 1463.42     7.8 1461.15    15.6 1459.46    19.4 1456.93    27.2 1446.99
    31.2 1442.33    35.2 1438.84    39.1 1436.22    47.1 1434.41      59 1434.02
    64.3 1434.75    70.9 1436.88    74.9 1437.64    94.8 1437.77   114.6 1438.56
   126.6 1438.21   142.5 1436.72   170.3 1435.02   174.3 1435.28   186.2 1438.63
   190.2 1439.16     206 1439.65     218 1443.69     222 1446.06   237.8 1458.24
   245.8 1463.62   253.7 1469.67   257.7 1472.21   265.7 1476.25   273.6 1481.53
#Mann= 3 , 0 , 0
       0     .08       0    47.1    .045       0    64.3     .08       0
Bank Sta=47.1,64.3
XS Rating Curve= 0 ,0
Exp/Cntr=0.3,0.1

Type RM Length L Ch R = 1 ,25536.9 ,360.6,363.3,364.2
XS GIS Cut Line= 4
     1795787.779      318609.253     1795808.395      318643.975
     1795964.645      318795.885     1796041.685      318895.711
#Sta/Elev= 30
       0 1458.01    25.7  1440.2      33 1436.74    36.7 1435.39    56.2 1430.98
    68.1 1430.93    77.5 1428.84    87.9 1428.04    95.8  1429.1   111.7 1433.22
   119.6 1434.37   163.2 1433.37   171.1 1431.87   198.9 1429.72   206.8 1431.46
   210.8 1432.94   214.7 1435.95   218.7 1436.63   246.4 1435.86   254.3 1436.94
   266.2 1442.72   285.9 1456.66   293.8 1463.22   309.5 1477.95   317.4 1484.41
   333.2 1494.49     345 1503.24   356.8 1509.78   376.5 1522.95   384.4 1527.41
#Mann= 3 , 0 , 0
       0      .1       0    77.5    .045       0    95.8     .08       0
Bank Sta=77.5,95.8
XS Rating Curve= 0 ,0
Exp/Cntr=0.3,0.1

Type RM Length L Ch R = 1 ,25173.5 ,205.1,204.6,202.9
XS GIS Cut Line= 4
     1795539.298      318834.947     1795559.915      318868.584
     1795720.505       319032.43     1795755.227      319112.725
#Sta/Elev= 30
       0 1460.32    19.7 1442.24    39.4 1427.81    43.4  1426.2    63.2 1424.81
      75    1421    80.6 1420.28    95.6 1419.65    98.8 1419.57   102.7 1420.88
   110.6 1425.06   126.5 1426.42   134.4 1426.22   150.2 1423.88   162.1  1423.8
   177.9 1422.36   185.8 1422.52   201.6 1427.07   209.5 1427.45   233.3 1430.25
     261 1434.29   288.8 1437.26   300.7 1439.26   304.7 1440.22   312.6 1443.24
   328.5 1451.19   332.5 1452.38   340.4  1452.5   352.4 1455.13   356.4 1455.35
#Mann= 3 , 0 , 0
       0      .1       0    80.6    .045       0    95.6     .08       0
Bank Sta=80.6,95.6
XS Rating Curve= 0 ,0
Exp/Cntr=0.3,0.1

Type RM Length L Ch R = 1 ,24968.9 ,258.8,264.3,268.7
XS GIS Cut Line= 4
     1795436.217      318986.857      1795486.13      319047.621
     1795598.977      319165.893     1795659.741       319265.72
#Sta/Elev= 30
       0 1438.06    11.8 1436.53    31.4 1432.51    70.8 1426.87    78.6 1425.21
    90.6 1421.46    94.6 1420.95   118.5 1422.29   122.5 1422.06   126.5 1421.04
   137.9 1415.97   142.4 1415.51   152.9 1415.98   170.3 1420.08   186.3 1418.64
   194.3 1418.83   206.2 1423.04   214.2 1427.08   218.2 1428.35   226.2  1429.4
   238.1 1432.16   242.1 1433.73   253.8 1441.39   257.7 1442.25   269.4 1443.02
   281.1 1444.98   288.8 1445.47   292.8 1446.52   304.4 1452.32     359 1490.95
#Mann= 3 , 0 , 0
       0      .1       0   137.9    .045       0   152.9     .07       0
#XS Ineff= 2 , 0
          118.69 1431.89
Permanent Ineff=
       F       F
Bank Sta=137.9,152.9
XS Rating Curve= 0 ,0
Exp/Cntr=0.3,0.1

Type RM Length L Ch R = 1 ,24704.6 ,331.1,331.4,331.3
XS GIS Cut Line= 4
     1795256.095      319097.534     1795275.626      319162.638
     1795384.133      319343.845     1795398.239      319415.459
#Sta/Elev= 30
       0 1420.07      48 1418.55      72 1417.02    83.9 1415.44    95.9 1415.42
   107.8 1416.65   131.7 1414.68   151.7 1414.61   163.6 1416.24   175.6 1416.67
   183.5 1415.82   191.5 1412.57   195.5 1411.72   203.5 1410.73   211.4 1410.92
   215.4 1411.63   223.4 1413.94   243.3 1414.45   251.3 1416.88   255.3 1417.22
   267.2  1416.5   275.2 1418.31   279.2 1420.55     283  1423.6   298.4 1437.48
   306.1  1445.1   309.9  1448.1   321.4 1455.65     333 1461.65   352.2 1473.01
#Mann= 3 , 0 , 0
       0     .08       0   195.5    .045       0   215.4     .07       0
Bank Sta=195.5,215.4
XS Rating Curve= 0 ,0
Exp/Cntr=0.3,0.1

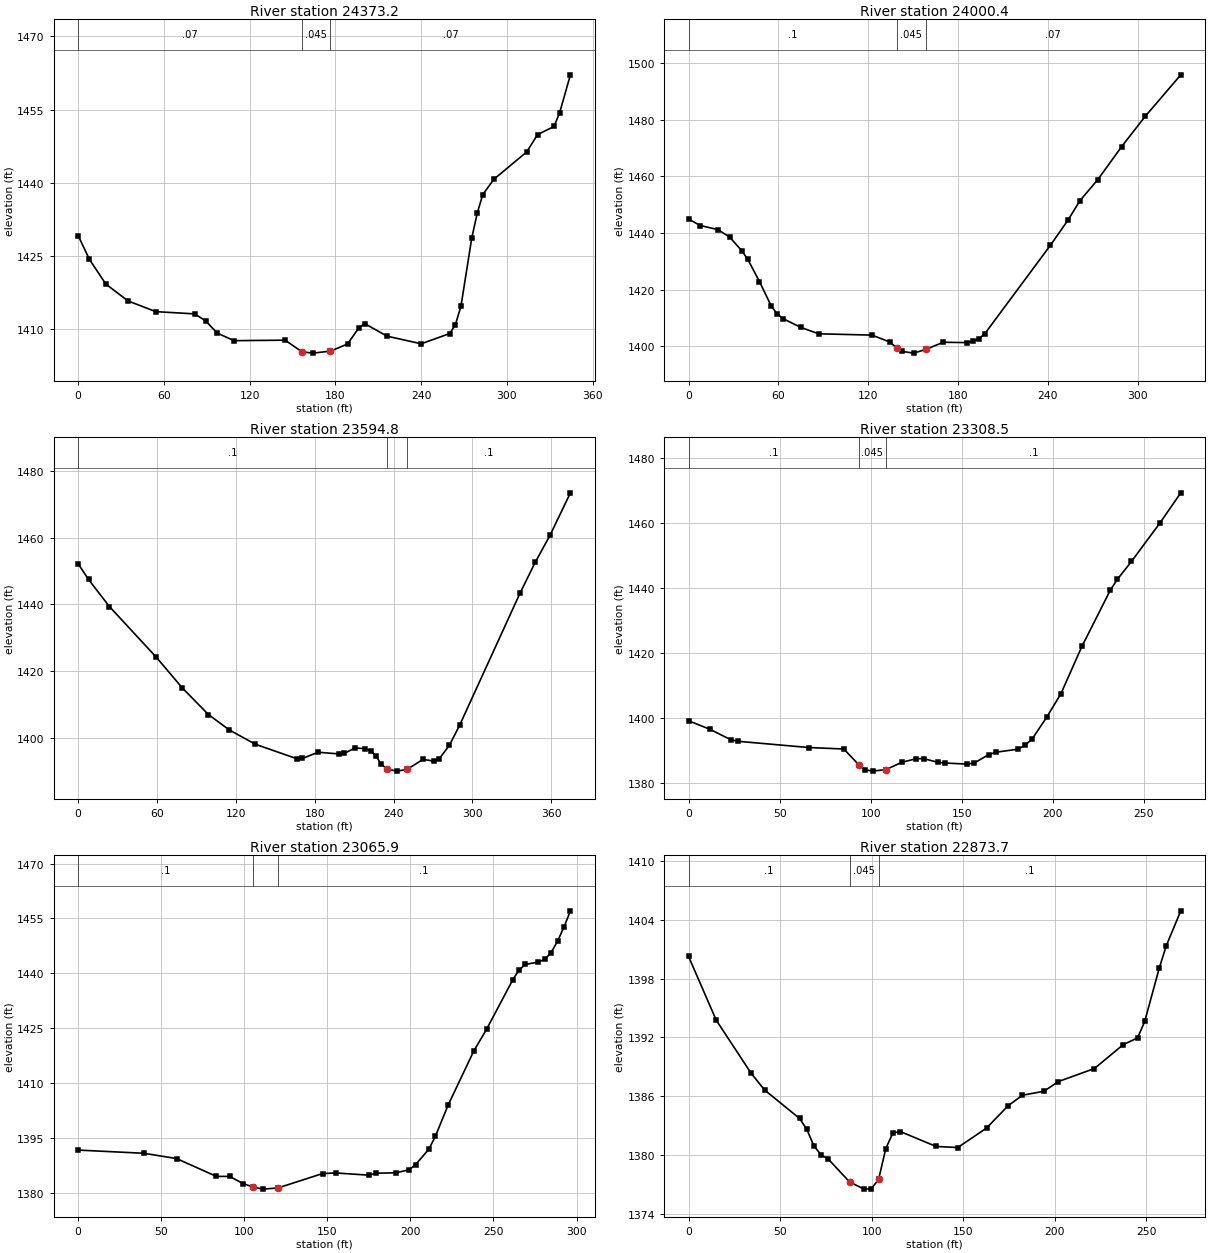
Type RM Length L Ch R = 1 ,24373.2 ,376.4,372.7,366.8
XS GIS Cut Line= 4
     1794994.593      319296.102     1795022.805      319380.737
     1795115.036      319533.732     1795149.758      319602.091
#Sta/Elev= 30
       0 1429.22     7.8 1424.38    19.4 1419.28    34.9 1415.84    54.3 1413.65
    81.5 1413.19    89.2 1411.77    97.2 1409.28   109.1 1407.71   144.8 1407.81
   156.7 1405.42   164.6 1405.16   176.6 1405.58   188.5 1407.02   196.4 1410.31
   200.4 1411.22   216.2 1408.63   240.1 1407.07   259.9 1409.16   263.9 1410.88
   267.9 1414.76   275.5 1428.78   279.4 1433.92   283.2 1437.61   290.9 1440.72
   313.9 1446.32   321.5 1449.86     333 1451.53   336.9 1454.28   344.5  1462.1
#Mann= 3 , 0 , 0
       0     .07       0   156.7    .045       0   176.6     .07       0
Bank Sta=156.7,176.6
XS Rating Curve= 0 ,0
Exp/Cntr=0.3,0.1

Type RM Length L Ch R = 1 ,24000.4 ,411.5,405.7,398
XS GIS Cut Line= 3
     1794698.369       319576.05     1794740.687      319628.133
     1794918.638       319820.19
#Sta/Elev= 30
       0  1444.9     7.9 1442.63    19.7 1441.18    27.6 1438.49    35.5 1433.78
    39.5 1430.78    47.4 1422.87    55.3 1414.21    59.2 1411.48    63.2  1409.8
      75 1406.72    86.9 1404.47   122.6    1404   134.6 1401.55     139 1399.49
   142.5 1398.28   150.4 1397.65   158.4 1398.94   170.2 1401.48   186.1 1401.36
   190.1 1401.85     194 1402.73     198 1404.53   241.7 1435.61   253.6  1444.6
   261.5 1451.39   273.4 1458.79   289.3  1470.4   305.1 1481.11   328.9 1495.76
#Mann= 3 , 0 , 0
       0      .1       0     139    .045       0   158.4     .07       0
Bank Sta=139,158.4
XS Rating Curve= 0 ,0
Exp/Cntr=0.3,0.1

Type RM Length L Ch R = 1 ,23594.8 ,287.3,286.2,282.6
XS GIS Cut Line= 4
     1794340.296      319891.805     1794484.611      319935.208
     1794601.798      320003.567     1794671.243       320057.82
#Sta/Elev= 30
       0 1452.15     7.9 1447.44    23.8 1439.32    59.5 1424.12    79.3  1414.9
    99.1 1406.97     115 1402.34   134.8 1398.06   166.7 1393.67   170.6  1393.8
   182.6 1395.66   198.6 1395.15   202.6 1395.33   210.6 1396.96   218.5 1396.71
   222.5 1396.08   226.5 1394.57   230.5 1392.14   235.1 1390.61   242.5    1390
   250.1  1390.5   262.4 1393.52   270.4 1393.02   274.4 1393.53   282.4 1397.73
   290.2 1403.73   336.2 1443.37   347.7 1452.56   359.2 1460.85   374.5 1473.41
#Mann= 3 , 0 , 0
       0      .1       0   235.1    .045       0   250.1      .1       0
Bank Sta=235.1,250.1
XS Rating Curve= 0 ,0
Exp/Cntr=0.3,0.1

Type RM Length L Ch R = 1 ,23308.5 ,244.1,242.7,242.5
XS GIS Cut Line= 4
     1794289.298      320135.945     1794357.658      320186.944
     1794460.739      320229.261     1794510.652      320283.515
#Sta/Elev= 30
       0 1399.25    11.6 1396.66    23.3 1393.41    27.1 1392.95    65.9 1391.04
    85.3 1390.58    93.5 1385.74    97.2 1384.16   101.2 1383.79   108.5 1384.27
   117.1 1386.49   125.1  1387.6   129.1 1387.63     137 1386.49     141 1386.28
   152.9 1385.95   156.9 1386.27   164.9 1388.87   168.9  1389.6   180.8 1390.51
   184.8  1391.7   188.8 1393.69   196.7 1400.31   204.5  1407.5   216.1 1422.09
   231.6 1439.24   235.5 1442.62   243.3 1448.14   258.8 1459.85   270.4 1469.21
#Mann= 3 , 0 , 0
       0      .1       0    93.5    .045       0   108.5      .1       0
Bank Sta=93.5,108.5
XS Rating Curve= 0 ,0
Exp/Cntr=0.3,0.1

Type RM Length L Ch R = 1 ,23065.9 ,190.1,192.2,194.4
XS GIS Cut Line= 4
     1794138.474      320362.725     1794199.237      320380.086
     1794335.956       320436.51     1794415.166      320467.977
#Sta/Elev= 30
       0 1391.68    39.5 1390.81    59.2 1389.37    83.2 1384.49    91.2 1384.48
    99.2 1382.53   105.2  1381.6   111.2 1381.01   120.2 1381.33   147.1 1385.26
   155.1 1385.43   175.1 1384.82   179.1 1385.37   191.1 1385.46   199.1 1386.28
   203.1  1387.7   211.1 1391.92     215 1395.42   222.7 1403.99   238.2 1418.81
     246 1424.83   261.5 1438.14   265.3 1440.86   269.2 1442.43     277 1443.06
   280.8  1443.8   284.7 1445.66   288.6 1448.81   292.5 1452.71   296.3 1457.07
#Mann= 3 , 0 , 0
       0      .1       0   105.2    .045       0   120.2      .1       0
Bank Sta=105.2,120.2
XS Rating Curve= 0 ,0
Exp/Cntr=0.3,0.1

Type RM Length L Ch R = 1 ,22873.7 ,236.5,234,230.5
XS GIS Cut Line= 3
      1794084.22      320500.529     1794120.027      320549.357
     1794304.489      320645.928
#Sta/Elev= 30
       0 1400.26    15.1 1393.77    34.1 1388.37    41.6 1386.63    60.6 1383.75
    64.5 1382.67    68.4 1380.97    72.3 1380.04    76.3  1379.6      88 1377.26
    95.9 1376.54    99.8 1376.58   103.8 1377.53   107.7 1380.68   111.6 1382.26
   115.6 1382.41   135.2 1380.89     147 1380.78   162.7 1382.76   174.5 1385.04
   182.3 1386.11   194.1 1386.52     202 1387.51   221.6 1388.83   237.3 1391.26
   245.2 1391.96   249.1 1393.64     257 1399.05   260.9 1401.37   268.8 1404.91
#Mann= 3 , 0 , 0
       0      .1       0      88    .045       0   103.8      .1       0
Bank Sta=88,103.8
XS Rating Curve= 0 ,0
Exp/Cntr=0.3,0.1

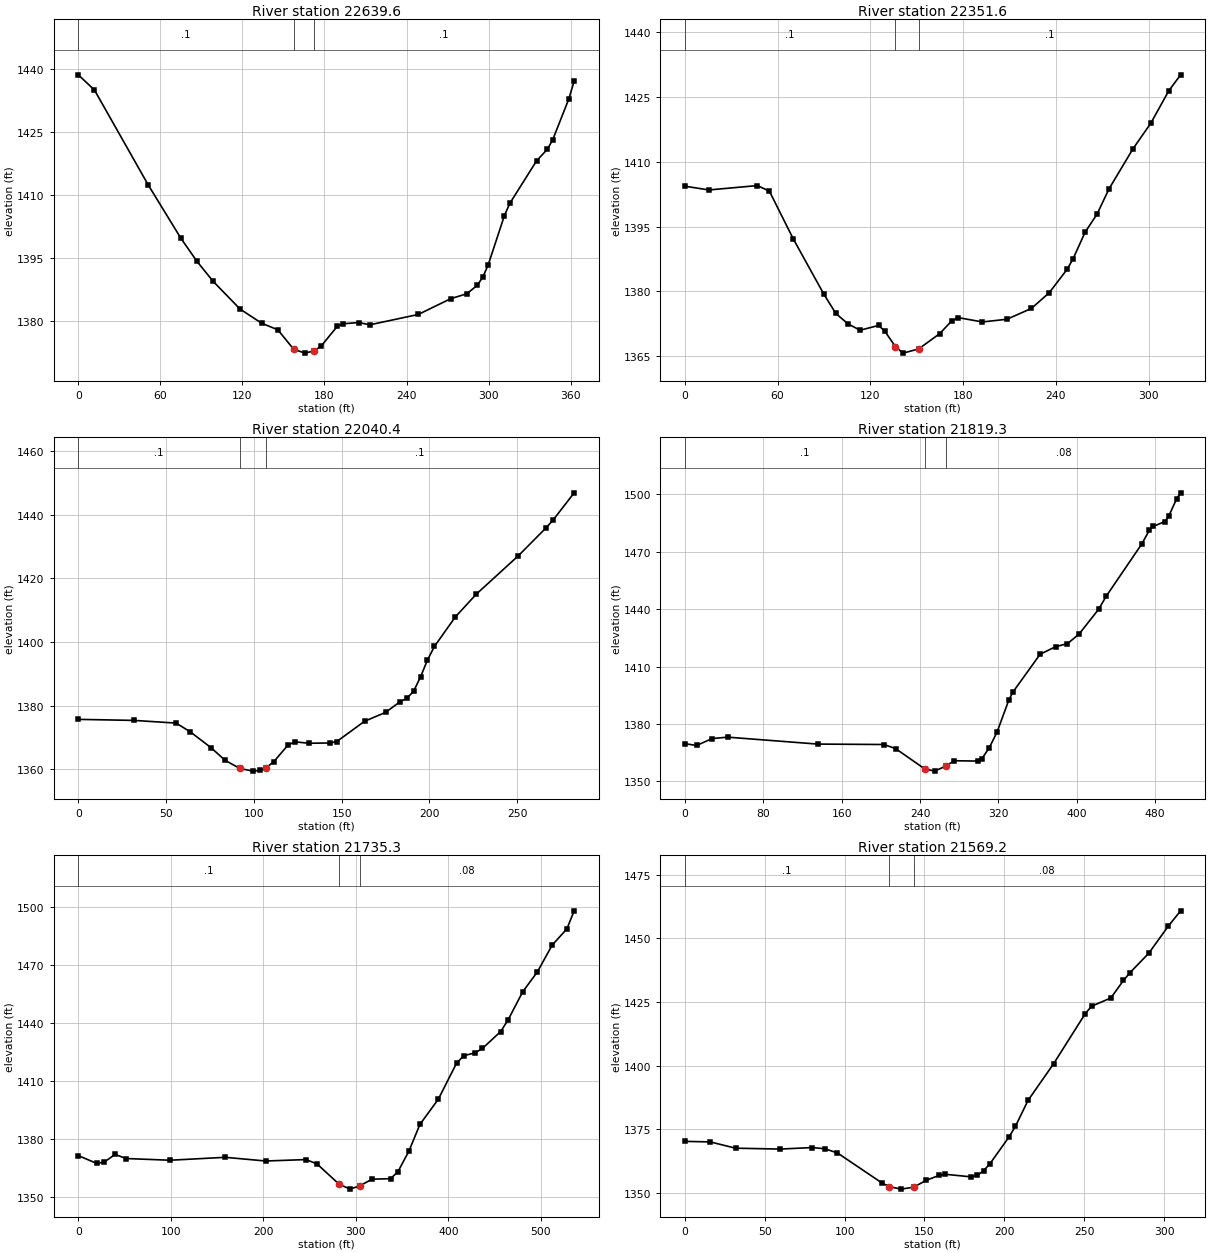
Type RM Length L Ch R = 1 ,22639.6 ,289.9,288,285.1
XS GIS Cut Line= 4
     1793927.313      320719.204     1794050.583      320771.796
     1794173.196      320816.284     1794253.491      320872.708
#Sta/Elev= 30
       0 1438.66    11.8 1435.03    51.2 1412.35    74.9 1399.73    86.7  1394.2
    98.5 1389.44   118.2 1382.82     134 1379.43   145.9 1377.85   157.4 1373.25
   165.6 1372.29   172.4 1372.82   177.5 1373.94   189.4 1378.69   193.3 1379.28
   205.2 1379.59   213.1 1379.04   248.6 1381.51   272.3 1385.27   284.1 1386.45
   291.9  1388.5   295.9  1390.5   299.8 1393.39   311.6  1405.1   315.5 1407.98
   335.1 1418.14     343 1420.91   346.9 1423.16   358.7 1432.92   362.6 1437.17
#Mann= 3 , 0 , 0
       0      .1       0   157.4    .045       0   172.4      .1       0
Bank Sta=157.4,172.4
XS Rating Curve= 0 ,0
Exp/Cntr=0.3,0.1

Type RM Length L Ch R = 1 ,22351.6 ,304.4,311.2,318
XS GIS Cut Line= 4
     1793838.771       321053.84     1793943.161      321038.723
     1794058.178       321068.02     1794148.239      321102.742
#Sta/Elev= 30
       0 1404.36    15.6 1403.49    46.9  1404.5    54.7 1403.22    70.3 1392.06
    89.8 1379.44    97.7 1374.88   105.5 1372.49   113.4    1371   125.3 1372.11
   129.2 1370.86   136.2 1367.23   141.1  1365.7   151.2 1366.66   164.8 1370.19
   172.7 1373.18   176.7 1373.93   192.5 1372.92   208.3 1373.54   224.2 1376.05
   235.8 1379.72   247.3 1385.12   251.2 1387.59   258.9  1393.7   266.6 1397.86
   274.4 1403.75   289.8 1412.97   301.4 1418.94     313 1426.43   320.7 1430.15
#Mann= 3 , 0 , 0
       0      .1       0   136.2    .045       0   151.2      .1       0
Bank Sta=136.2,151.2
XS Rating Curve= 0 ,0
Exp/Cntr=0.3,0.1

Type RM Length L Ch R = 1 ,22040.4 ,232.7,221.1,209.3
XS GIS Cut Line= 2
      1793842.25      321300.225     1794083.135      321447.794
#Sta/Elev= 30
       0  1375.7    31.8 1375.37    55.7 1374.53    63.7 1371.81    75.6 1366.81
    83.6 1362.84      92 1360.28    99.5 1359.44   103.4 1359.66     107  1360.5
   111.4 1362.42   119.4 1367.59   123.3 1368.65   131.3  1368.2   143.2 1368.28
   147.2 1368.72   163.1 1375.11   175.1  1377.9     183 1381.13     187 1382.26
     191 1384.49     195 1389.07   198.9 1394.31   202.9 1398.62   214.8 1407.87
   226.8 1415.06   250.7 1427.09   266.6 1435.93   270.6 1438.38   282.5 1446.86
#Mann= 3 , 0 , 0
       0      .1       0      92    .045       0     107      .1       0
Bank Sta=92,107
XS Rating Curve= 0 ,0
Exp/Cntr=0.3,0.1

Type RM Length L Ch R = 1 ,21819.3 ,84.5,84,83.4
XS GIS Cut Line= 2
     1793612.215      321555.216     1794117.857      321571.492
#Sta/Elev= 30
       0 1369.76      12 1368.79    27.9  1372.4    43.8 1373.14   135.4 1369.53
   203.2  1369.3   215.1 1367.16   244.8 1356.56   254.9  1355.4   266.9 1358.18
   274.9 1360.83   298.8 1360.65   302.8 1361.69   310.7 1367.62   318.7 1375.94
   330.6 1392.52   334.6 1396.55   362.5 1416.42   378.4 1420.41   390.4 1421.95
   402.3    1427   422.2  1439.9   430.2 1446.92   466.1 1473.92     474  1481.2
     478 1483.24     490 1485.75     494 1488.85   501.9  1497.7   505.9 1500.75
#Mann= 3 , 0 , 0
       0      .1       0   244.8    .045       0   266.9     .08       0
Bank Sta=244.8,266.9
XS Rating Curve= 0 ,0
Exp/Cntr=0.3,0.1

Type RM Length L Ch R = 1 ,21735.3 ,166.2,166.1,166.1
XS GIS Cut Line= 2
     1793561.217      321645.277     1794097.241      321648.532
#Sta/Elev= 30
       0 1371.46    19.8 1367.46    27.8 1368.06    39.7 1372.08    51.6 1369.96
    99.3 1369.08   158.8 1370.59   202.5 1368.68   246.2 1369.42   258.1 1367.14
   281.9 1356.69   293.8 1354.15   304.2 1355.86   317.6 1359.29   337.5 1359.56
   345.4 1363.06   357.4 1373.85   369.3 1387.62   389.1 1400.57     409 1419.36
   416.9 1423.14   428.8 1424.54   436.8 1426.82   456.6 1435.59   464.6 1441.63
   480.4 1456.12   496.3 1466.45   512.2 1480.22   528.1  1488.6     536 1497.95
#Mann= 3 , 0 , 0
       0      .1       0   281.9    .045       0   304.2     .08       0
Bank Sta=281.9,304.2
XS Rating Curve= 0 ,0
Exp/Cntr=0.3,0.1

Type RM Length L Ch R = 1 ,21569.2 ,320.2,320.5,320.5
XS GIS Cut Line= 2
     1793713.126      321812.378     1794023.456      321813.463
#Sta/Elev= 30
       0 1370.29    15.9 1370.08    31.8 1367.61    59.7 1367.27    79.6 1367.86
    87.5 1367.41    95.5 1365.76   123.3 1354.01   127.8 1352.56   135.3 1351.55
   143.2  1352.3   151.2 1355.04   159.1 1356.92   163.1 1357.37     179 1356.38
     183 1356.92     187 1358.79     191 1361.54   202.9 1372.02   206.9 1376.18
   214.8 1386.36   230.8 1400.74   250.6  1420.4   254.6 1423.34   266.6 1426.54
   274.5 1433.42   278.5 1436.42   290.4 1444.14   302.4 1454.61   310.3 1460.76
#Mann= 3 , 0 , 0
       0      .1       0   127.8    .045       0   143.2     .08       0
Bank Sta=127.8,143.2
XS Rating Curve= 0 ,0
Exp/Cntr=0.3,0.1

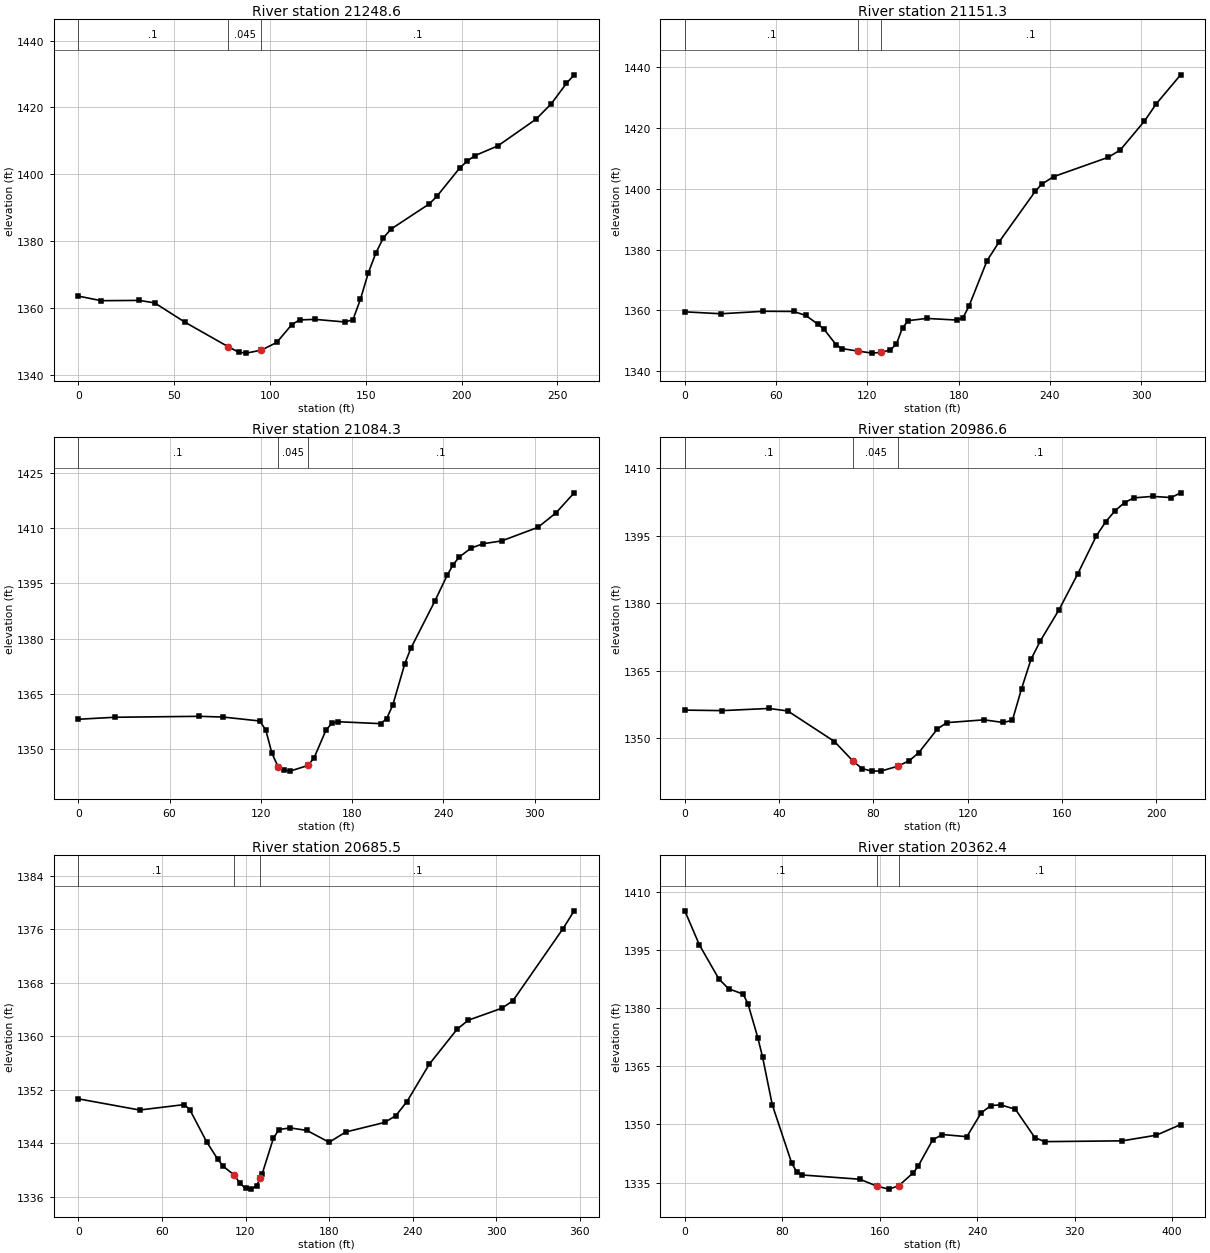
Type RM Length L Ch R = 1 ,21248.6 ,97.3,97.4,96.6
XS GIS Cut Line= 2
     1793796.894      322130.086     1794055.574      322131.822
#Sta/Elev= 30
       0 1363.54    11.9 1362.17    31.8 1362.25    39.8 1361.52    55.7  1355.7
    78.1 1348.42    83.6 1346.76    87.6 1346.47    95.5 1347.37   103.5 1349.66
   111.4 1355.02   115.4  1356.4   123.4 1356.58   139.3 1355.78   143.3 1356.51
   147.2  1362.6   151.2 1370.32   155.2 1376.42   159.2 1381.02   163.2 1383.62
   183.1 1391.14     187 1393.36     199 1401.89     203 1404.02     207 1405.61
   218.9 1408.51   238.8  1416.5   246.8 1421.14   254.7 1427.24   258.7 1429.78
#Mann= 3 , 0 , 0
       0      .1       0    78.1    .045       0    95.5      .1       0
Bank Sta=78.1,95.5
XS Rating Curve= 0 ,0
Exp/Cntr=0.3,0.1

Type RM Length L Ch R = 1 ,21151.3 ,66.8,67,67.2
XS GIS Cut Line= 3
     1793779.533      322227.308     1793958.352      322225.572
     1794102.449      322196.058
#Sta/Elev= 30
       0 1359.56    23.8 1358.93    51.7 1359.74    71.5 1359.69    79.5 1358.38
    87.4 1355.54    91.4 1353.92    99.4 1348.79   103.3  1347.5   113.8 1346.68
   123.2 1346.01   128.8 1346.25   135.1 1347.04   139.1 1349.01   143.1 1354.35
     147 1356.68     159  1357.4   178.8 1356.86   182.8 1357.57   186.8 1361.44
   198.7 1376.39   206.7 1382.59   230.5 1399.21   234.5 1401.41   242.4 1403.92
   278.2 1410.25   286.2 1412.65   302.1 1422.14     310  1427.9   325.9 1437.34
#Mann= 3 , 0 , 0
       0      .1       0   113.8    .045       0   128.8      .1       0
Bank Sta=113.8,128.8
XS Rating Curve= 0 ,0
Exp/Cntr=0.3,0.1

Type RM Length L Ch R = 1 ,21084.3 ,107.9,97.7,87.5
XS GIS Cut Line= 3
     1793781.269      322291.544     1793960.088      322289.808
     1794104.185      322260.294
#Sta/Elev= 30
       0 1358.12    23.8 1358.66    79.5 1358.92    95.4 1358.71   119.2 1357.65
   123.2 1355.22   127.2 1348.94   131.3 1345.23   135.1 1344.32   139.1 1344.04
     151 1345.58     155 1347.69   162.9 1355.29   166.9 1357.09   170.9 1357.45
   198.7 1356.93   202.7 1358.32   206.7 1361.99   214.6 1373.22   218.6 1377.43
   234.5 1390.33   242.4 1397.18   246.4 1400.11   250.4 1402.17   258.3 1404.63
   266.3 1405.79   278.2 1406.53   302.1 1410.22     314 1414.16   325.9 1419.59
#Mann= 3 , 0 , 0
       0      .1       0   131.3    .045       0     151      .1       0
Bank Sta=131.3,151
XS Rating Curve= 0 ,0
Exp/Cntr=0.3,0.1

Type RM Length L Ch R = 1 ,20986.6 ,290.9,301.1,311.3
XS GIS Cut Line= 2
      1793892.38      322411.336     1794081.616      322319.322
#Sta/Elev= 30
       0 1356.28    15.9 1356.17    35.7 1356.65    43.7 1356.09    63.5 1349.31
    71.5 1344.89    75.3 1343.28    79.4 1342.73    83.4 1342.76    90.3 1343.81
    95.3 1345.06    99.3 1346.84   107.2  1352.1   111.2  1353.5     127 1354.12
     135 1353.54     139    1354   142.9 1361.03   146.9 1367.55   150.9 1371.68
   158.8 1378.57   166.8  1386.6   174.7 1395.04   178.7 1398.16   182.6 1400.58
   186.6 1402.37   190.6 1403.42   198.5 1403.75   206.4 1403.49   210.4 1404.54
#Mann= 3 , 0 , 0
       0      .1       0    71.5    .045       0    90.3      .1       0
Bank Sta=71.5,90.3
XS Rating Curve= 0 ,0
Exp/Cntr=0.3,0.1

Type RM Length L Ch R = 1 ,20685.5 ,332.8,323.1,313.3
XS GIS Cut Line= 2
     1793927.102      322661.336     1794283.005      322661.336
#Sta/Elev= 30
       0 1350.66      44 1348.99      76  1349.8      80 1349.05      92 1344.28
     100 1341.66     104 1340.59     112 1339.27     116 1338.04     120 1337.28
     124 1337.18     128 1337.69   130.7  1338.9     132 1339.48     140 1344.77
     144 1346.08     152 1346.32     164 1345.95     180 1344.18     192 1345.71
   219.9 1347.14   227.9 1348.15   235.9 1350.25   251.9 1355.83   271.9 1361.06
   279.9  1362.4   303.9 1364.18   311.9 1365.29   347.9 1376.07   355.9 1378.73
#Mann= 3 , 0 , 0
       0      .1       0     112    .045       0   130.7      .1       0
Bank Sta=112,130.7
XS Rating Curve= 0 ,0
Exp/Cntr=0.3,0.1

Type RM Length L Ch R = 1 ,20362.4 ,150.4,151.1,151
XS GIS Cut Line= 2
     1793960.088       323043.28      1794329.88      322873.142
#Sta/Elev= 30
       0 1405.08      12 1396.28    27.9 1387.56    35.9 1384.99    47.9 1383.61
    51.9 1381.07    59.9  1372.4    63.8 1367.44    71.8 1355.08    87.8 1339.99
    91.8 1337.82    95.8 1336.99   143.7 1335.88     158 1334.06   167.6 1333.33
   175.6 1334.19   187.6 1337.56   191.6 1339.28   203.5 1346.04   211.5 1347.41
   231.5 1346.85   243.4 1353.03   251.4 1354.89   259.4 1355.05   271.4 1353.91
   287.3 1346.63   295.3 1345.57   359.2 1345.78   387.1 1347.24     407 1349.97
#Mann= 3 , 0 , 0
       0      .1       0     158    .045       0   175.6      .1       0
Bank Sta=158,175.6
XS Rating Curve= 0 ,0
Exp/Cntr=0.3,0.1