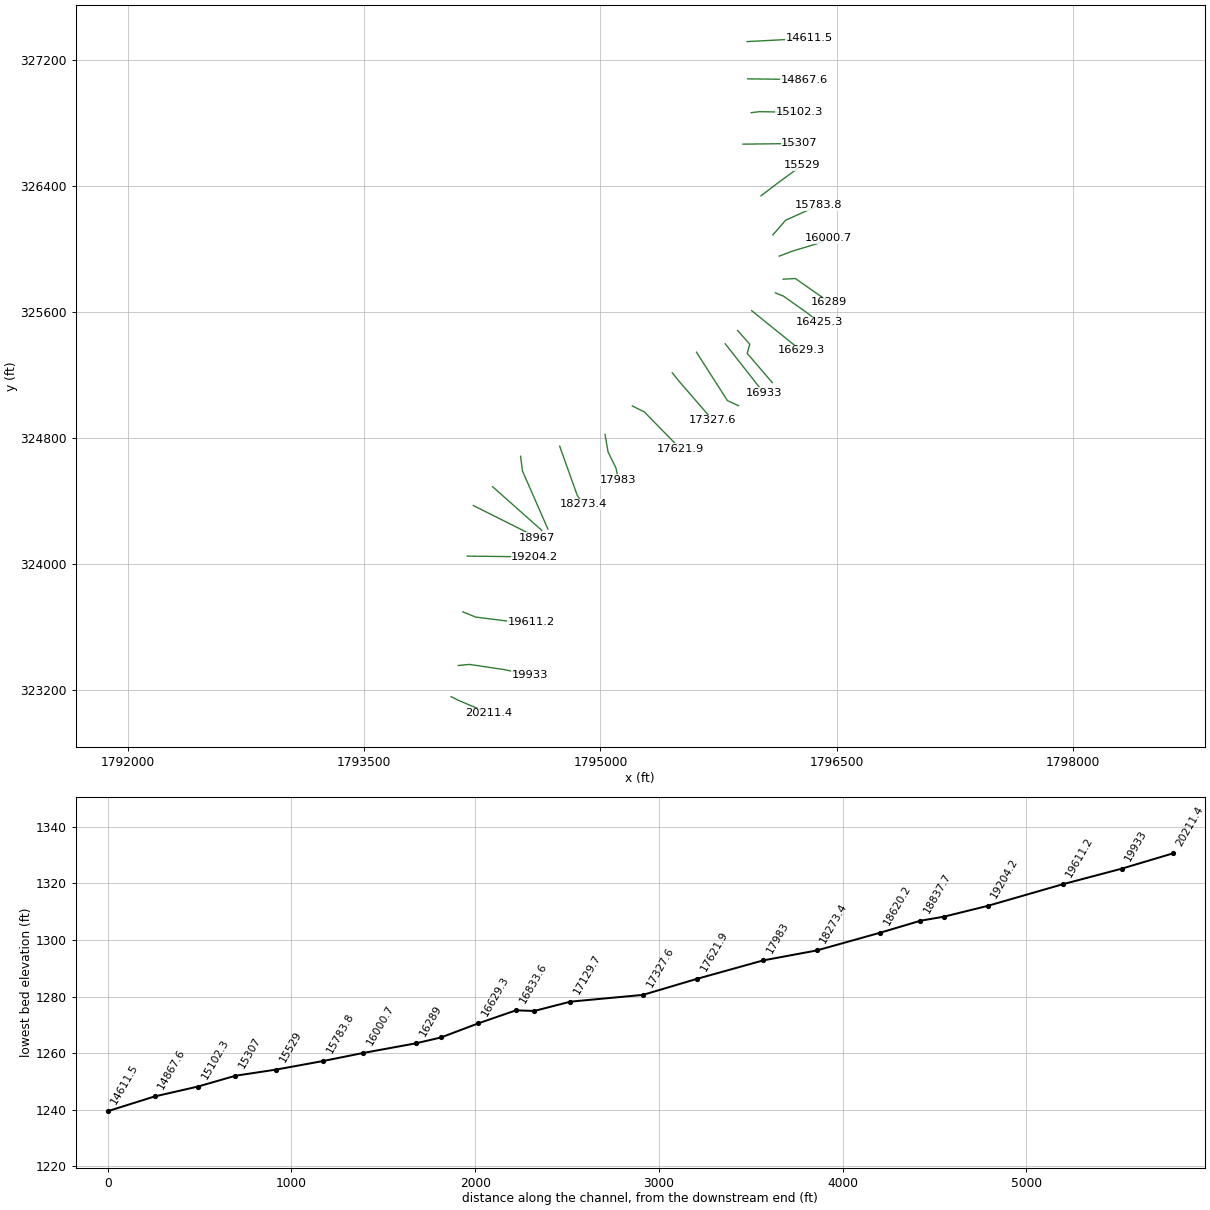
HEC-RAS study WESTFK1.prj: WESTFK1

--- WESTFK1.g01 (geometry) --- (continued)

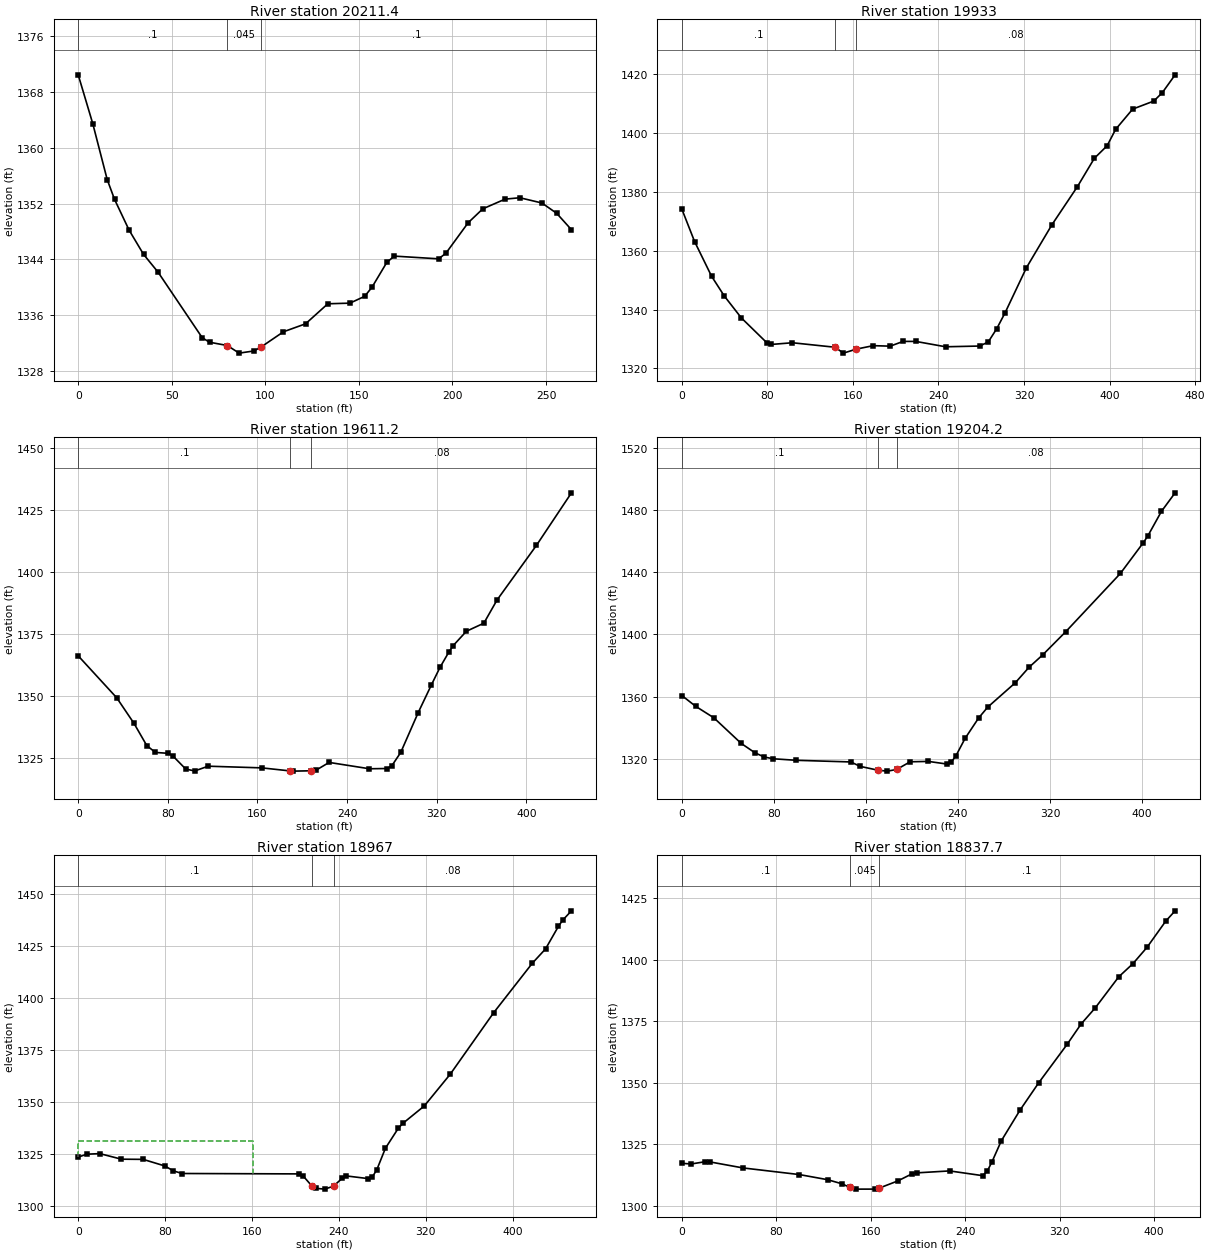
Type RM Length L Ch R = 1 ,20211.4 ,271.7,278.4,284.3
XS GIS Cut Line= 3
     1794052.102        323159.6     1794097.241       323137.03
     1794293.421      323053.697
#Sta/Elev= 30
       0 1370.45     7.8 1363.44    15.5 1355.44    19.4 1352.62    27.2  1348.2
    34.9 1344.74    42.7 1342.17    66.3 1332.78    70.2 1332.14    79.7 1331.67
      86 1330.58    93.9 1330.89    97.8 1331.47   109.7 1333.64   121.5 1334.78
   133.4 1337.65   145.2 1337.74   153.1 1338.72     157 1340.02   164.9 1343.57
   168.9 1344.48   192.6 1344.09   196.5 1344.89   208.4 1349.26   216.2 1351.25
   228.1 1352.64     236 1352.84   247.8 1352.09   255.7 1350.61   263.6 1348.26
#Mann= 3 , 0 , 0
       0      .1       0    79.7    .045       0    97.8      .1       0
Bank Sta=79.7,97.8
XS Rating Curve= 0 ,0
Exp/Cntr=0.3,0.1

Type RM Length L Ch R = 1 ,19933   ,319,321.8,323
XS GIS Cut Line= 4
     1794097.241      323357.517     1794168.421      323364.461
     1794388.908      323331.475     1794552.102      323296.753
#Sta/Elev= 30
       0 1374.18    11.9 1363.15    27.8 1351.34    39.7 1344.62    55.6 1337.19
    79.5 1328.71    83.5 1328.14   103.4 1328.72   143.2 1327.19   151.1 1325.19
   163.1 1326.55     179 1327.73   194.9 1327.56   206.9 1329.18   218.8 1329.17
   246.7 1327.35   278.5  1327.6   286.5 1328.97   294.5  1333.5   302.4 1338.99
   322.3 1354.27   346.1 1368.85   369.9 1381.79   385.8 1391.46   397.7 1395.71
   405.7  1401.3   421.6 1408.18   441.4 1410.92   449.4  1413.8   461.3 1419.84
#Mann= 3 , 0 , 0
       0      .1       0   143.2    .045       0   163.1     .08       0
Bank Sta=143.2,163.1
XS Rating Curve= 0 ,0
Exp/Cntr=0.3,0.1

Type RM Length L Ch R = 1 ,19611.2 ,405.3,407,408.1
XS GIS Cut Line= 4
     1794126.755      323697.794     1794208.352      323664.808
     1794402.796      323640.503     1794559.046      323635.294
#Sta/Elev= 30
       0 1366.19    34.4 1349.25    49.8 1338.94    61.2 1329.99    68.9 1327.21
    80.4 1326.85    84.2 1325.93      96  1320.5     104 1319.74     116 1321.66
     164 1320.98   189.4 1319.74     192 1319.67     208 1319.81     212 1319.97
     224 1323.18     260 1320.62     276 1320.73     280 1321.87   287.9 1327.21
   303.5 1343.29   315.2  1354.4     323 1361.58   330.9 1367.74   334.8 1370.35
   346.5  1376.1   362.1 1379.36   373.9 1388.74     409 1410.73   440.3 1431.96
#Mann= 3 , 0 , 0
       0      .1       0   189.4    .045       0     208     .08       0
Bank Sta=189.4,208
XS Rating Curve= 0 ,0
Exp/Cntr=0.3,0.1

Type RM Length L Ch R = 1 ,19204.2 ,247.4,237.1,227
XS GIS Cut Line= 2
     1794154.533      324051.961     1794583.352      324046.753
#Sta/Elev= 30
       0 1360.71    11.9 1353.83    27.8 1346.38    51.6 1329.89    63.5 1323.88
    71.5 1321.16    79.4 1320.01    99.3 1319.02   146.9 1317.96   154.9 1315.13
   170.8  1312.6   178.7 1312.05   186.7  1313.1   198.5 1318.07   214.4  1318.3
   230.3 1316.62   234.3 1317.97   238.2  1321.8   246.2 1333.09   258.1 1346.35
     266  1353.3   289.9 1368.93   301.8 1378.87   313.7 1386.86   333.6 1401.68
   381.2 1439.25   401.1    1459     405  1463.3   416.9  1479.2   428.8 1491.16
#Mann= 3 , 0 , 0
       0      .1       0   170.8    .045       0   186.7     .08       0
Bank Sta=170.8,186.7
XS Rating Curve= 0 ,0
Exp/Cntr=0.3,0.1

Type RM Length L Ch R = 1 ,18967   ,137,129.3,120.2
XS GIS Cut Line= 2
     1794192.727      324373.142     1794598.977      324170.017
#Sta/Elev= 30
       0 1323.63       8 1325.02    19.9 1325.29    39.8 1322.62    59.8 1322.53
    79.7 1319.38    87.6 1317.03    95.6 1315.75   203.2 1315.56   207.2 1314.54
   215.4 1309.61   219.1 1308.61   227.1 1308.25   235.1 1309.69     243 1313.41
     247 1314.58   266.9 1313.31   270.9 1314.18   274.9 1317.47   282.9 1327.89
   294.8  1337.5   298.8 1339.75   318.7 1348.18   342.6 1363.42   382.5 1392.88
   418.3 1416.76   430.3 1423.52   442.2 1434.37   446.2  1437.4   454.2 1441.82
#Mann= 3 , 0 , 0
       0      .1       0   215.4    .045       0   235.1     .08       0
#XS Ineff= 2 , 0
           161.2 1331.22
Permanent Ineff=
       F       F
Bank Sta=215.4,235.1
XS Rating Curve= 0 ,0
Exp/Cntr=0.3,0.1

Type RM Length L Ch R = 1 ,18837.7 ,224.5,217.5,210.1
XS GIS Cut Line= 2
     1794315.334      324492.642     1794627.834      324215.298
#Sta/Elev= 30
       0 1317.27       8 1317.02    19.9 1317.94    23.9 1317.84    51.7 1315.41
    99.5 1312.71   123.4 1310.63   135.3    1309   142.6 1307.46   147.2 1306.79
   163.2  1306.8   167.1 1307.19     183 1310.14     195 1313.02     199  1313.4
   226.8 1314.19   254.7 1312.27   258.6 1314.02   262.6 1317.79   270.6 1326.43
   286.5 1338.94   302.4 1350.09   326.3  1365.6   338.2 1373.91   350.2 1380.47
   370.1 1393.09     382 1398.38     394 1405.04   409.9 1415.72   417.8 1419.89
#Mann= 3 , 0 , 0
       0      .1       0   142.6    .045       0   167.1      .1       0
Bank Sta=142.6,167.1
XS Rating Curve= 0 ,0
Exp/Cntr=0.3,0.1

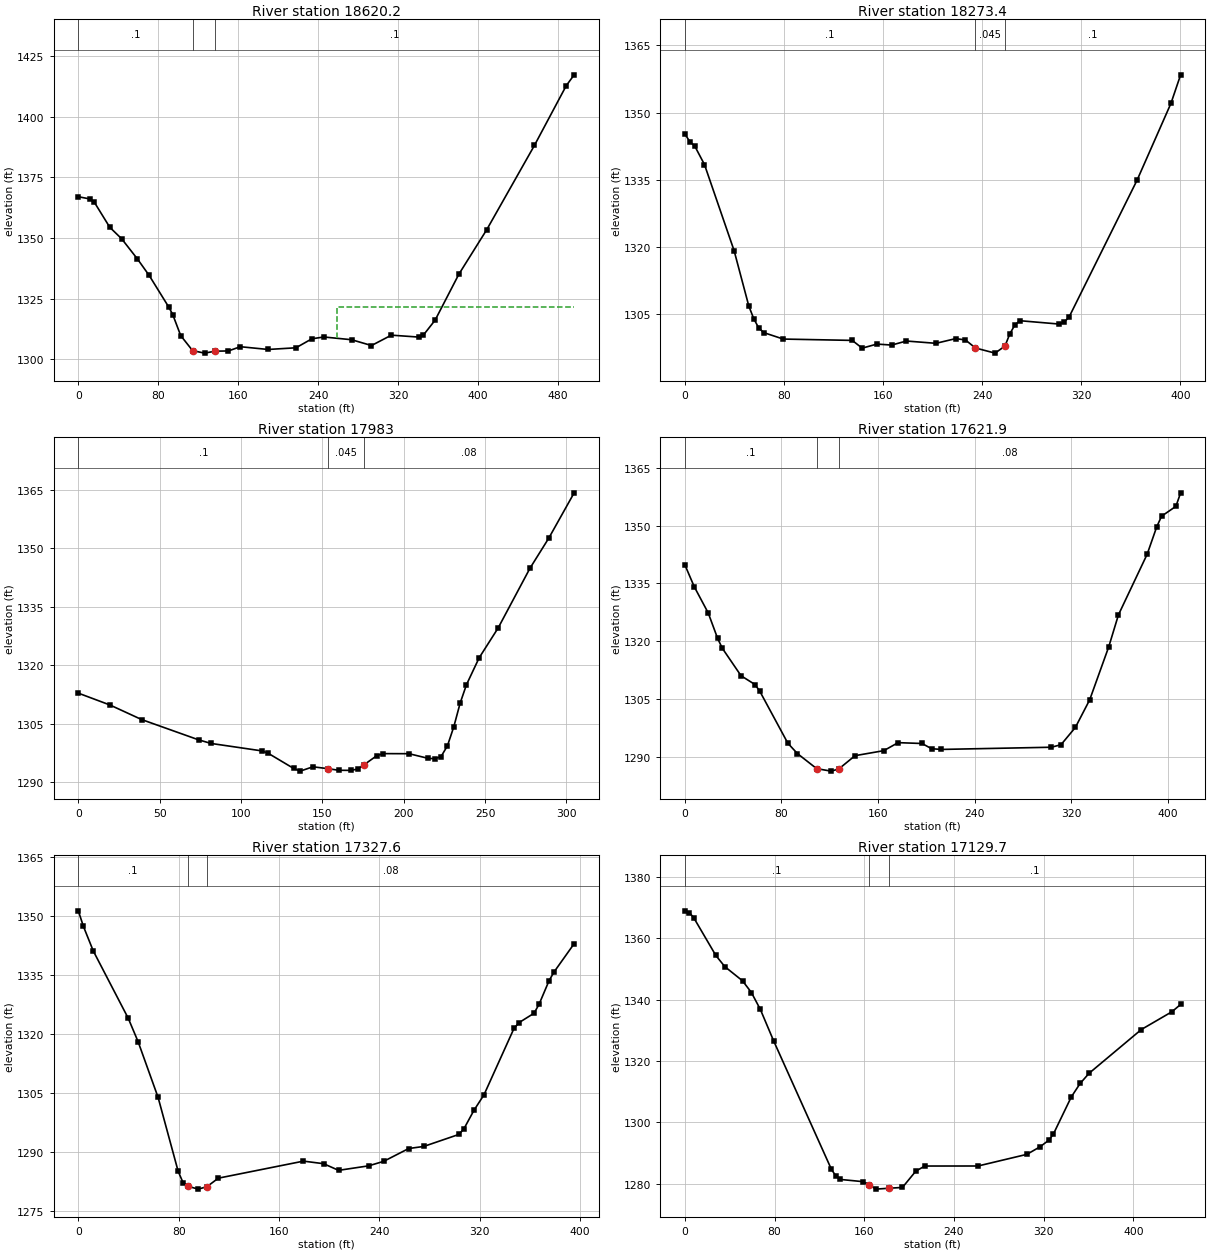
Type RM Length L Ch R = 1 ,18620.2 ,347.5,346.9,343.7
XS GIS Cut Line= 3
     1794493.074      324685.642     1794505.227      324591.892
     1794666.685      324223.836
#Sta/Elev= 30
       0 1367.02    11.8 1366.09    15.8 1364.89    31.5 1354.42    43.3 1349.73
    59.1 1341.42    70.9 1334.61    90.6 1321.52    94.5  1318.5   102.5 1309.81
   114.4 1303.62   126.4 1302.59   136.9 1303.39   150.2 1303.49   162.2 1305.23
     190  1304.1   217.9 1304.79   233.8 1308.49   245.8 1309.24   273.6 1308.11
   293.5 1305.72   313.4 1309.99   341.2 1309.19   345.2 1309.89   357.2 1316.18
     381 1335.12   408.9 1353.46   456.6 1388.14   488.5 1412.78   496.4 1417.24
#Mann= 3 , 0 , 0
       0      .1       0   114.4    .045       0   136.9      .1       0
#XS Ineff= 2 , 0
                          259.08         1321.43
Permanent Ineff=
       F       F
Bank Sta=114.4,136.9
XS Rating Curve= 0 ,0
Exp/Cntr=0.3,0.1

Type RM Length L Ch R = 1 ,18273.4 ,287.6,290.4,292.7
XS GIS Cut Line= 3
     1794741.338      324749.878     1794852.449      324439.114
     1794890.644      324380.086
#Sta/Elev= 30
       0 1345.26       4  1343.5       8 1342.53    15.9 1338.37    39.8 1319.17
    51.7 1306.78    55.7 1303.95    59.6 1301.96    63.6 1300.88    79.5 1299.43
   135.2 1299.13   143.2  1297.4   155.1 1298.31     167 1298.09   178.9 1298.99
   202.8 1298.48   218.7 1299.53   226.6 1299.23   234.6 1297.44   250.5 1296.29
   258.5 1297.87   262.4  1300.6   266.4 1302.53   270.4 1303.53   302.2 1302.78
   306.2 1303.19   310.2 1304.32   365.2 1334.93   392.5 1352.05   400.3 1358.41
#Mann= 3 , 0 , 0
       0      .1       0   234.6    .045       0   258.5      .1       0
Bank Sta=234.6,258.5
XS Rating Curve= 0 ,0
Exp/Cntr=0.3,0.1

Type RM Length L Ch R = 1 ,17983   ,353.7,361.1,368.1
XS GIS Cut Line= 4
     1795029.533       324824.53      1795048.63      324713.419
     1795098.977      324610.989     1795114.602        324534.6
#Sta/Elev= 30
       0 1312.79    19.4 1309.76    38.9 1306.02    73.9 1300.82    81.6 1299.89
   112.7 1297.99   116.7 1297.37   132.4 1293.47   136.4 1292.79   144.2  1293.9
   153.7 1293.41     160 1293.01   167.8 1292.98   171.8 1293.35   175.7 1294.44
   183.6 1296.79   187.5 1297.28   203.3 1297.26   215.1 1296.06     219 1295.99
   222.9 1296.47   226.9 1299.28   230.8 1304.15   234.7 1310.22   238.6 1314.96
   246.4 1321.86   258.1 1329.53   277.6  1344.8   289.2 1352.55   304.8 1364.17
#Mann= 3 , 0 , 0
       0      .1       0   153.7    .045       0   175.7     .08       0
Bank Sta=153.7,175.7
XS Rating Curve= 0 ,0
Exp/Cntr=0.3,0.1

Type RM Length L Ch R = 1 ,17621.9 ,295.5,294.3,292.7
XS GIS Cut Line= 3
     1795203.144      325005.086     1795279.533      324966.892
     1795506.963      324734.253
#Sta/Elev= 30
       0 1339.84     7.8 1334.13    19.4 1327.31    27.2 1320.69    31.1 1318.13
    46.6 1311.01    58.2 1308.72    62.1    1307    85.4 1293.48    93.3 1290.81
   109.2 1286.91   121.1 1286.26   127.4 1286.78     141 1290.27   164.8 1291.57
   176.7 1293.65   196.5 1293.43   204.4 1292.08   212.4 1291.89   303.6 1292.46
   311.6 1293.11   323.5 1297.59   335.4 1304.78   351.2 1318.56   359.2 1326.82
     383 1342.56   390.9 1349.65   394.9 1352.41   406.8 1354.98   410.7 1358.48
#Mann= 3 , 0 , 0
       0      .1       0   109.2    .045       0   127.4     .08       0
Bank Sta=109.2,127.4
XS Rating Curve= 0 ,0
Exp/Cntr=0.3,0.1

Type RM Length L Ch R = 1 ,17327.6 ,395.2,394.7,393
XS GIS Cut Line= 3
     1795456.616      325215.155     1795501.755        325159.6
      1795713.56      324914.808
#Sta/Elev= 30
       0 1351.26       4 1347.35    11.9 1341.08    39.8 1323.97    47.7 1317.99
    63.6 1303.87    79.6  1285.1    83.6 1282.16    87.5  1281.3    95.6 1280.59
   102.5  1281.2   111.6 1283.37   179.5  1287.7   195.5 1287.05   207.5 1285.36
   231.4  1286.5   243.4 1287.64   263.4  1290.9   275.4 1291.43   303.4 1294.48
   307.4  1295.9   315.4  1300.6   323.4 1304.53   347.3 1321.38   351.3 1322.86
   363.3 1325.25   367.3 1327.51   375.3 1333.53   379.3 1335.75   395.3 1342.92
#Mann= 3 , 0 , 0
       0      .1       0    87.5    .045       0   102.5     .08       0
Bank Sta=87.5,102.5
XS Rating Curve= 0 ,0
Exp/Cntr=0.3,0.1

Type RM Length L Ch R = 1 ,17129.7 ,194.2,196.7,198.4
XS GIS Cut Line= 3
     1795610.371      325346.136     1795806.769      325039.061
     1795877.298      325006.509
#Sta/Elev= 30
       0 1368.93       4 1368.38     7.9 1366.72    27.7 1354.37    35.7 1350.73
    51.5 1346.11    59.4  1342.3    67.4 1336.77    79.2 1326.56   130.8 1284.62
   134.7  1282.5   138.7 1281.36   158.5 1280.65   164.6  1279.6   170.4  1278.2
   182.2 1278.49   194.1 1278.75     206 1284.05     214 1285.73   261.5 1285.74
   305.1 1289.54     317 1292.04   324.9 1294.23   328.8 1296.21   344.7 1308.26
   352.6 1312.66   360.6 1315.98   407.2 1330.24   434.4 1336.02   442.2 1338.41
#Mann= 3 , 0 , 0
       0      .1       0   164.6    .045       0   182.2      .1       0
Bank Sta=164.6,182.2
XS Rating Curve= 0 ,0
Exp/Cntr=0.3,0.1

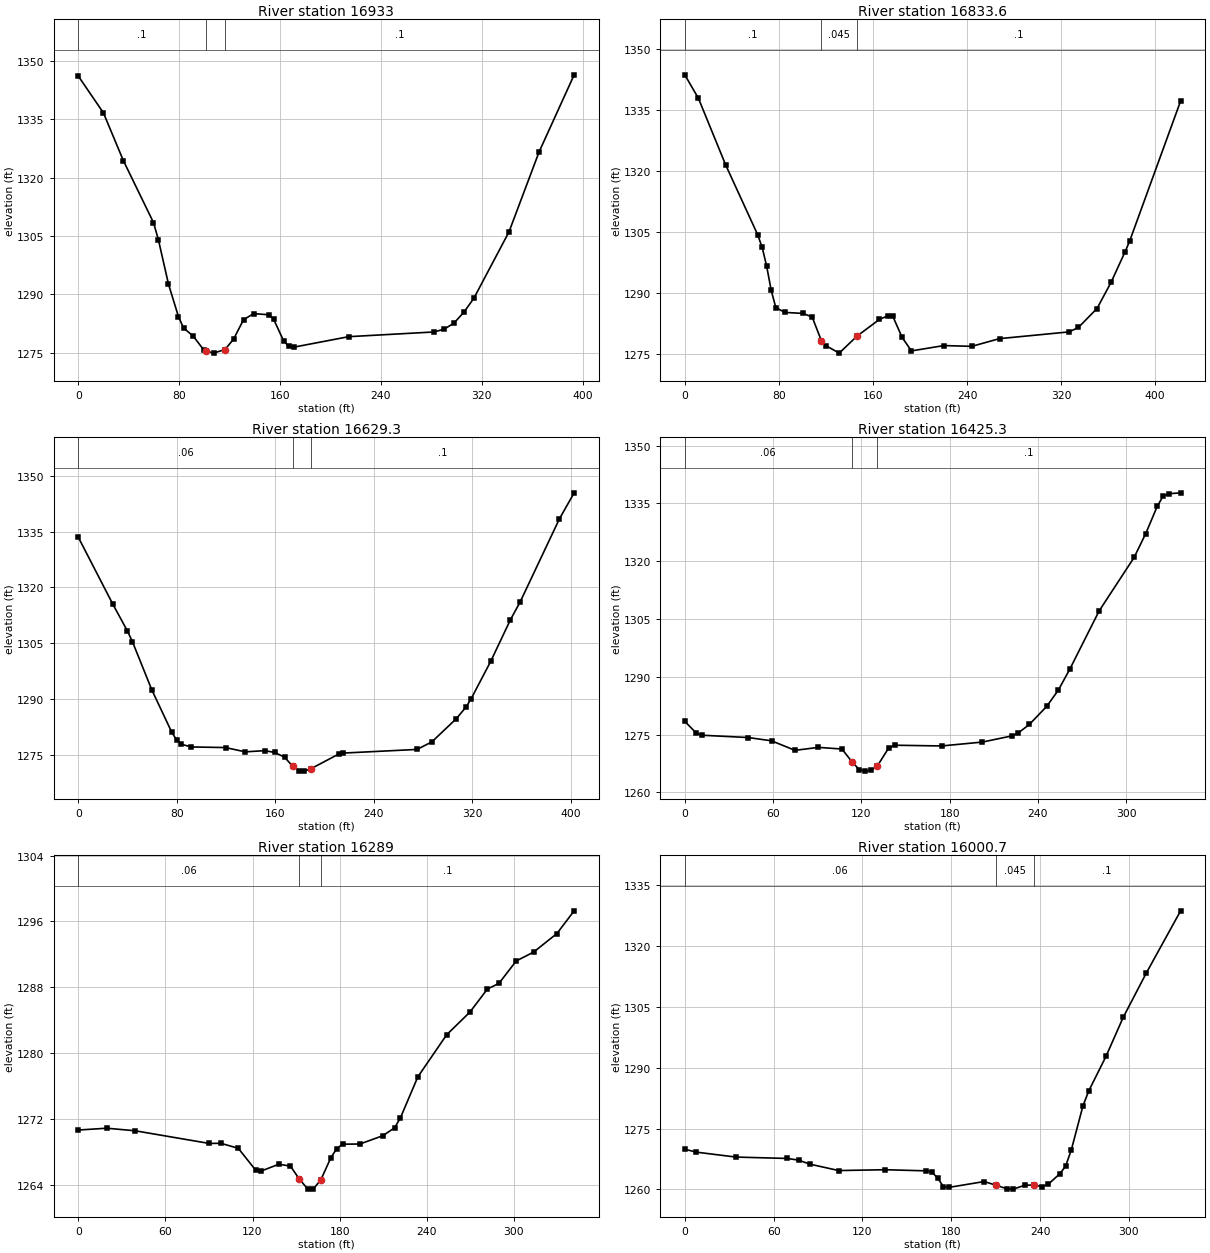
Type RM Length L Ch R = 1 ,16933   ,121,99.4,72.3
XS GIS Cut Line= 2
     1795793.421      325399.183     1796036.477      325090.155
#Sta/Elev= 30
       0 1346.13    19.9 1336.68    35.7 1324.41    59.6 1308.48    63.5 1304.05
    71.5 1292.64    79.4  1284.3    83.4 1281.39    91.3 1279.22    99.3 1275.79
   101.3 1275.48   107.2 1274.91   116.3 1275.84   123.1  1278.5     131  1283.5
     139 1285.06   150.9 1284.78   154.9 1283.59   162.8 1278.07   166.8 1276.66
   170.8 1276.44   214.4 1279.14     282 1280.35   289.9 1281.04   297.8  1282.6
   305.8 1285.45   313.7 1289.04   341.5 1306.07   365.4 1326.65   393.2 1346.46
#Mann= 3 , 0 , 0
       0      .1       0   101.3    .045       0   116.3      .1       0
Bank Sta=101.3,116.3
XS Rating Curve= 0 ,0
Exp/Cntr=0.3,0.1

Type RM Length L Ch R = 1 ,16833.6 ,177.5,204.3,236.4
XS GIS Cut Line= 4
     1795871.763      325484.036     1795948.803       325397.23
     1795932.527      325338.636     1796092.033       325153.09
#Sta/Elev= 30
       0 1343.69    11.6 1337.89    34.8 1321.46    61.9 1304.34    65.8 1301.18
    69.6 1296.54    73.5 1290.57    77.4 1286.33    85.1 1285.16   100.6 1284.91
   108.3 1284.02   116.1 1278.22   119.9 1276.99   131.3 1275.13   146.5 1279.34
   165.5 1283.43   173.1 1284.39   176.9 1284.19   184.8 1278.99   192.7 1275.68
   220.3 1276.99     244  1276.8   267.6  1278.7   326.8 1280.36   334.7 1281.46
   350.5 1286.12   362.4 1292.54   374.2 1299.99   378.2 1302.69   421.6 1337.25
#Mann= 3 , 0 , 0
       0      .1       0   116.1    .045       0   146.5      .1       0
Bank Sta=116.1,146.5
XS Rating Curve= 0 ,0
Exp/Cntr=0.3,0.1

Type RM Length L Ch R = 1 ,16629.3 ,202.5,204,205.4
XS GIS Cut Line= 2
     1795960.739      325609.904     1796274.324      325357.083
#Sta/Elev= 30
       0 1333.47    27.9 1315.55    39.9 1308.25    43.9 1305.42    59.8 1292.34
    75.8 1281.08    79.8 1278.95    83.8 1277.77    91.7 1277.06   119.6 1276.89
   135.6 1275.74   151.6 1276.06   159.5 1275.57   167.5 1274.31     174 1271.91
   179.5 1270.69   183.5 1270.55     189  1271.2   211.4 1275.12   215.4 1275.41
   275.2 1276.39   287.2 1278.42   307.1 1284.67   315.1 1287.85   319.1 1290.03
     335 1300.08     351 1311.27   358.9 1316.06   390.8 1338.42   402.8 1345.44
#Mann= 3 , 0 , 0
       0     .06       0     174    .045       0     189      .1       0
Bank Sta=174,189
XS Rating Curve= 0 ,0
Exp/Cntr=0.3,0.1

Type RM Length L Ch R = 1 ,16425.3 ,136.1,136.3,136.3
XS GIS Cut Line= 4
     1796111.564      325722.751     1796162.562      325702.135
     1796305.791      325601.223     1796390.427      325536.119
#Sta/Elev= 30
       0 1278.44     7.9 1275.37    11.8 1274.85    43.2 1274.25      59  1273.4
    74.9 1270.93    90.8  1271.7   106.8 1271.27   113.5 1268.02   118.7 1265.88
   122.7 1265.54   126.7  1265.8   130.7 1266.78   138.6 1271.56   142.6 1272.26
   174.5 1272.07   202.3 1273.08   222.2 1274.67   226.2 1275.32   234.2 1277.65
     246 1282.35   253.9 1286.56   261.8 1292.08   281.6 1307.09   305.4 1320.98
   313.3 1327.17   321.2 1334.31   325.1 1336.86   329.1  1337.5     337 1337.73
#Mann= 3 , 0 , 0
       0     .06       0   113.5    .045       0   130.7      .1       0
Bank Sta=113.5,130.7
XS Rating Curve= 0 ,0
Exp/Cntr=0.3,0.1

Type RM Length L Ch R = 1 ,16289   ,267.2,288.3,308.5
XS GIS Cut Line= 3
     1796160.392      325809.557     1796238.517      325813.897
     1796454.446      325663.072
#Sta/Elev= 30
       0 1270.66    19.6 1270.88    39.1 1270.57    90.2 1269.03    98.2 1269.05
   110.2 1268.44   122.1  1265.8   126.1 1265.69   138.1  1266.5   146.1 1266.28
   152.1 1264.74   158.1 1263.48     162 1263.52   167.1 1264.62     174  1267.3
     178  1268.4     182 1268.94     194 1268.96   209.9 1269.98   217.9 1270.93
   221.9 1272.14   233.9 1277.12   253.8 1282.24   269.8 1284.99   281.8 1287.78
   289.8 1288.48   301.7  1291.2   313.7 1292.28   329.7 1294.53   341.6 1297.29
#Mann= 3 , 0 , 0
       0     .06       0   152.1    .045       0   167.1      .1       0
Bank Sta=152.1,167.1
XS Rating Curve= 0 ,0
Exp/Cntr=0.3,0.1

Type RM Length L Ch R = 1 ,16000.7 ,213.6,216.9,219.5
XS GIS Cut Line= 4
      1796136.52      325956.041     1796218.986      325987.508
     1796388.257      326038.506     1796451.191      326068.888
#Sta/Elev= 30
       0  1269.9     7.7 1269.18    34.5 1267.96    69.1 1267.62    76.8 1267.21
    84.4 1266.22     104 1264.63   135.4 1264.84   162.9 1264.56   166.8 1264.29
   170.8 1262.78   174.7 1260.66   178.6 1260.49   202.2 1261.92     210 1261.04
   217.9 1260.09   221.8 1260.05   229.7 1261.02   235.7 1261.05   241.5 1260.68
   245.4 1261.23   253.3 1263.83   257.2 1265.71   261.1 1269.77   268.9 1280.55
   272.8 1284.25   284.5 1292.82   296.1 1302.42   311.6 1313.29   334.9 1328.72
#Mann= 3 , 0 , 0
       0     .06       0     210    .045       0   235.7      .1       0
Bank Sta=210,235.7
XS Rating Curve= 0 ,0
Exp/Cntr=0.3,0.1

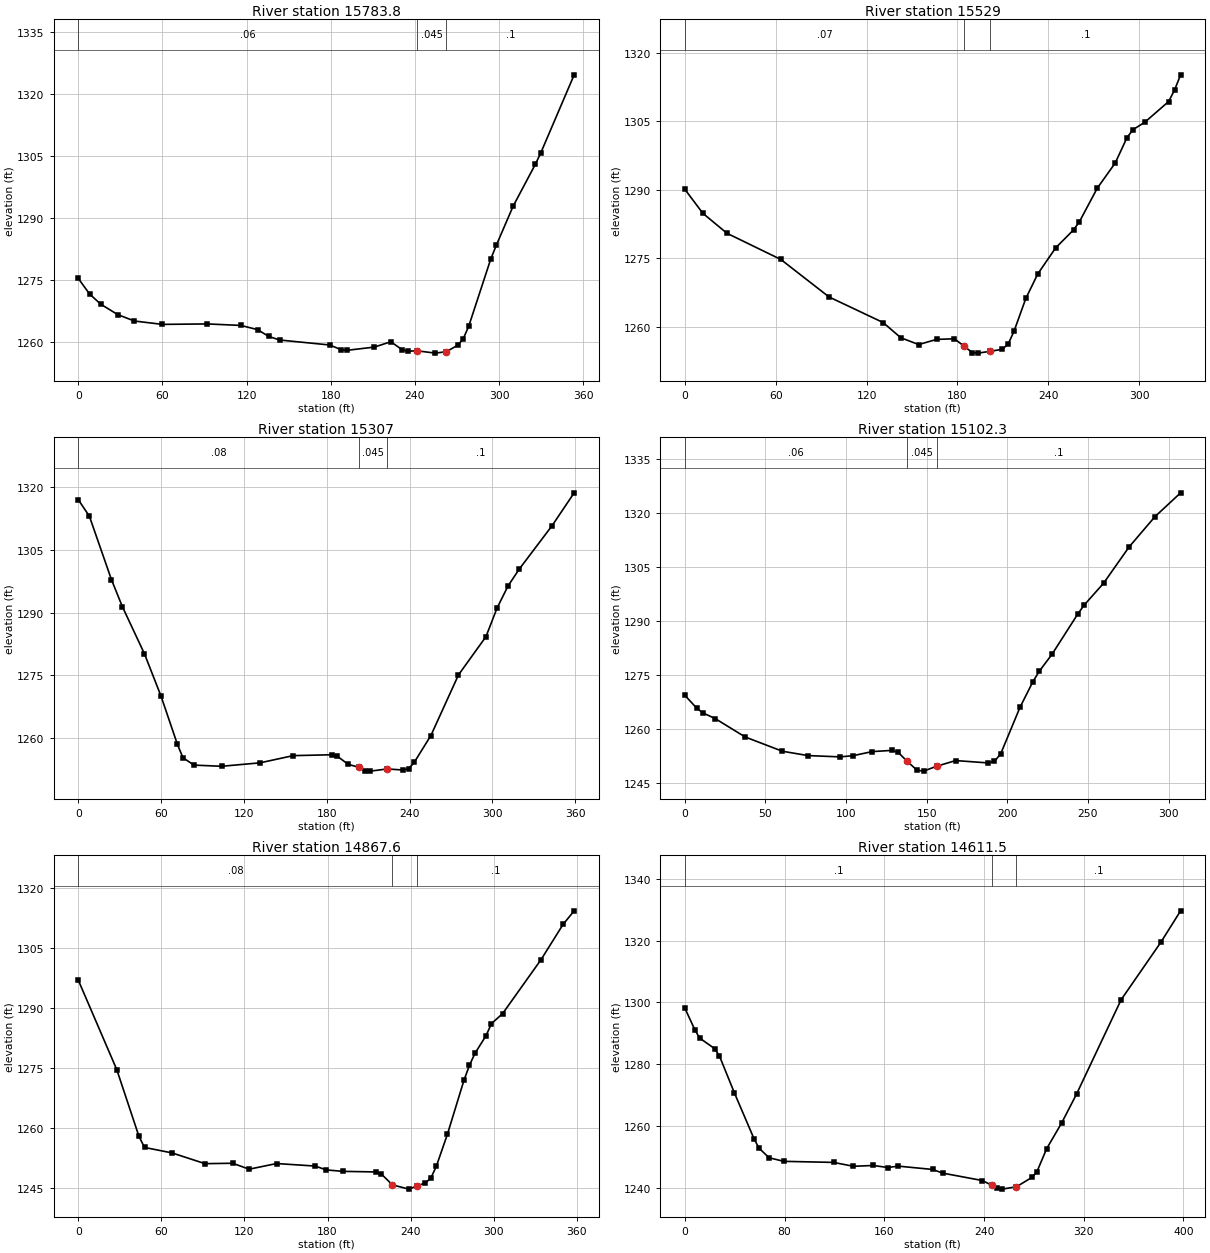
Type RM Length L Ch R = 1 ,15783.8 ,250.2,254.8,259.9
XS GIS Cut Line= 3
     1796095.288       326090.59     1796176.668      326183.905
     1796386.086      326278.307
#Sta/Elev= 30
       0 1275.32       8 1271.56      16 1269.08      28 1266.58    39.9 1265.01
    59.9 1264.19    91.9  1264.3   115.8 1263.94   127.8 1262.92   135.7 1261.27
   143.6  1260.4   179.3 1259.19   187.2 1258.07   191.2 1257.89     211 1258.68
   222.8 1259.98   230.8 1258.06   234.7 1257.68   241.3 1257.79   254.5 1257.22
   262.4 1257.57   270.4 1259.12   274.3 1260.62   278.3 1263.71   294.1  1280.1
   298.1 1283.45     310 1292.86   325.8 1302.98   329.8 1305.85   353.5  1324.7
#Mann= 3 , 0 , 0
       0     .06       0   241.3    .045       0   262.4      .1       0
Bank Sta=241.3,262.4
XS Rating Curve= 0 ,0
Exp/Cntr=0.3,0.1

Type RM Length L Ch R = 1 ,15529   ,235.5,222,207.5
XS GIS Cut Line= 3
     1796020.418       326339.07     1796124.585       326418.28
     1796283.005      326534.383
#Sta/Elev= 30
       0 1290.14    11.9 1284.87    27.8 1280.49    63.4 1274.74    95.2 1266.52
   130.9 1260.91   142.6 1257.57   154.4 1256.08   166.2 1257.21     178 1257.35
   184.3 1255.73   189.8 1254.32   193.7  1254.2   201.6 1254.61   209.4 1255.02
   213.4 1256.14   217.3 1258.98   225.1 1266.18     233 1271.57   244.8 1277.28
   256.6 1281.22   260.5 1283.02   272.3 1290.39   284.1 1295.88   291.9 1301.46
   295.8 1303.19   303.7 1304.85   319.4 1309.38   323.3 1311.91   327.3 1315.23
#Mann= 3 , 0 , 0
       0     .07       0   184.3    .045       0   201.6      .1       0
Bank Sta=184.3,201.6
XS Rating Curve= 0 ,0
Exp/Cntr=0.3,0.1

Type RM Length L Ch R = 1 ,15307   ,205.1,204.7,204
XS GIS Cut Line= 2
     1795905.401      326666.761     1796264.559      326671.102
#Sta/Elev= 30
       0 1317.01       8 1313.07      24 1297.87    31.9 1291.41    47.9 1280.12
    59.9 1269.99    71.8  1258.4    75.8 1255.23    83.8 1253.46   103.8 1253.18
   131.7 1254.01   155.6 1255.73   183.6 1255.94   187.6 1255.58   195.6 1253.63
   203.5 1252.92   207.5  1252.1   211.5 1252.02   223.8 1252.54   235.5 1252.28
   239.5 1252.64   243.4 1254.15   255.4 1260.54   275.4 1275.07   295.3 1284.22
   303.3 1291.04   311.3 1296.37   319.3 1300.35   343.2  1310.8   359.2 1318.67
#Mann= 3 , 0 , 0
       0     .08       0   203.5    .045       0   223.8      .1       0
Bank Sta=203.5,223.8
XS Rating Curve= 0 ,0
Exp/Cntr=0.3,0.1

Type RM Length L Ch R = 1 ,15102.3 ,233.8,234.7,233.9
XS GIS Cut Line= 3
     1795957.484      326866.414     1796009.567      326872.925
     1796264.559      326868.584
#Sta/Elev= 30
       0 1269.32     7.5 1265.68    11.2 1264.42    18.8 1262.84    37.5 1257.69
    60.5 1253.73    76.4 1252.52    96.3 1252.16   104.3 1252.49   116.2 1253.63
   128.2 1253.96   132.2 1253.46     138 1250.88   144.1 1248.42   148.1 1248.19
   156.1 1249.54     168 1251.13     188 1250.48     192 1250.88   195.9    1253
   207.9 1265.98   215.9 1273.12   219.8 1275.99   227.8 1280.78   243.8 1292.01
   247.7 1294.45   259.7 1300.52   275.6 1310.67   291.6 1319.08   307.5 1325.71
#Mann= 3 , 0 , 0
       0     .06       0     138    .045       0   156.1      .1       0
Bank Sta=138,156.1
XS Rating Curve= 0 ,0
Exp/Cntr=0.3,0.1

Type RM Length L Ch R = 1 ,14867.6 ,254.3,256.1,257
XS GIS Cut Line= 2
     1795934.698      327081.258      1796292.77      327076.918
#Sta/Elev= 30
       0 1296.87    27.8 1274.52    43.8 1257.87    47.8 1255.12    67.6 1253.76
    91.5 1251.07   111.4 1251.17   123.4 1249.69   143.2  1251.1   171.1 1250.47
     179 1249.51     191 1249.15   214.9    1249   218.8  1248.5   226.8 1245.78
   238.7 1244.71   244.8 1245.54   250.7 1246.28   254.6 1247.46   258.6 1250.45
   266.6 1258.45   278.5 1271.88   282.5 1275.66   286.5 1278.65   294.4    1283
   298.4 1286.05   306.4 1288.53   334.2 1302.03   350.1 1310.82   358.1 1314.21
#Mann= 3 , 0 , 0
       0     .08       0   226.8    .045       0   244.8      .1       0
Bank Sta=226.8,244.8
XS Rating Curve= 0 ,0
Exp/Cntr=0.3,0.1

Type RM Length L Ch R = 1 ,14611.5 ,236.7,236.7,236.7
XS GIS Cut Line= 2
     1795931.442      327317.803     1796328.578      327338.419
#Sta/Elev= 30
       0 1298.16       8 1291.17    11.9 1288.43    23.9 1285.01    27.8 1282.61
    39.8 1270.64    55.7 1255.64    59.6 1252.73    67.6 1249.64    79.5 1248.48
   119.3 1248.14   135.2 1246.88   151.1 1247.14     163 1246.48     171 1246.94
   198.8 1245.85   206.8 1244.67   238.6 1242.27   246.6 1240.66   250.5  1239.7
   254.5 1239.48     266 1240.24   278.4 1243.27   282.4 1245.09   290.3 1252.63
   302.2 1260.86   314.2 1270.26     350 1300.86   381.8 1319.44   397.7 1329.65
#Mann= 3 , 0 , 0
       0      .1       0   246.6    .045       0     266      .1       0
Bank Sta=246.6,266
XS Rating Curve= 0 ,0
Exp/Cntr=0.3,0.1