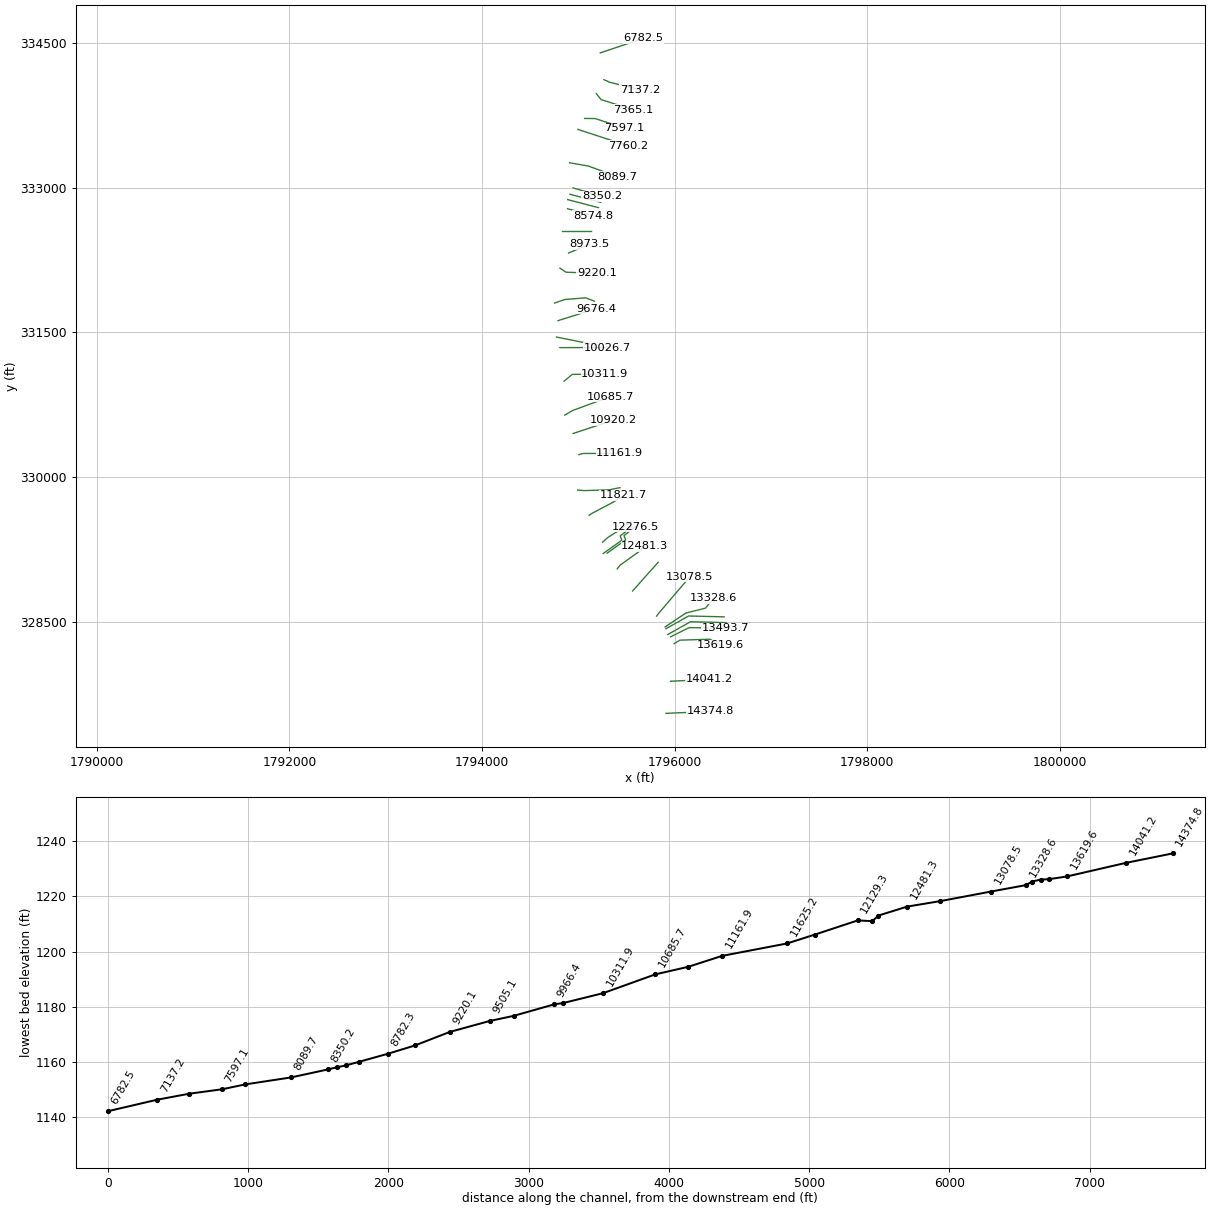
HEC-RAS study WESTFK1.prj: WESTFK1

--- WESTFK1.g01 (geometry) --- (continued)

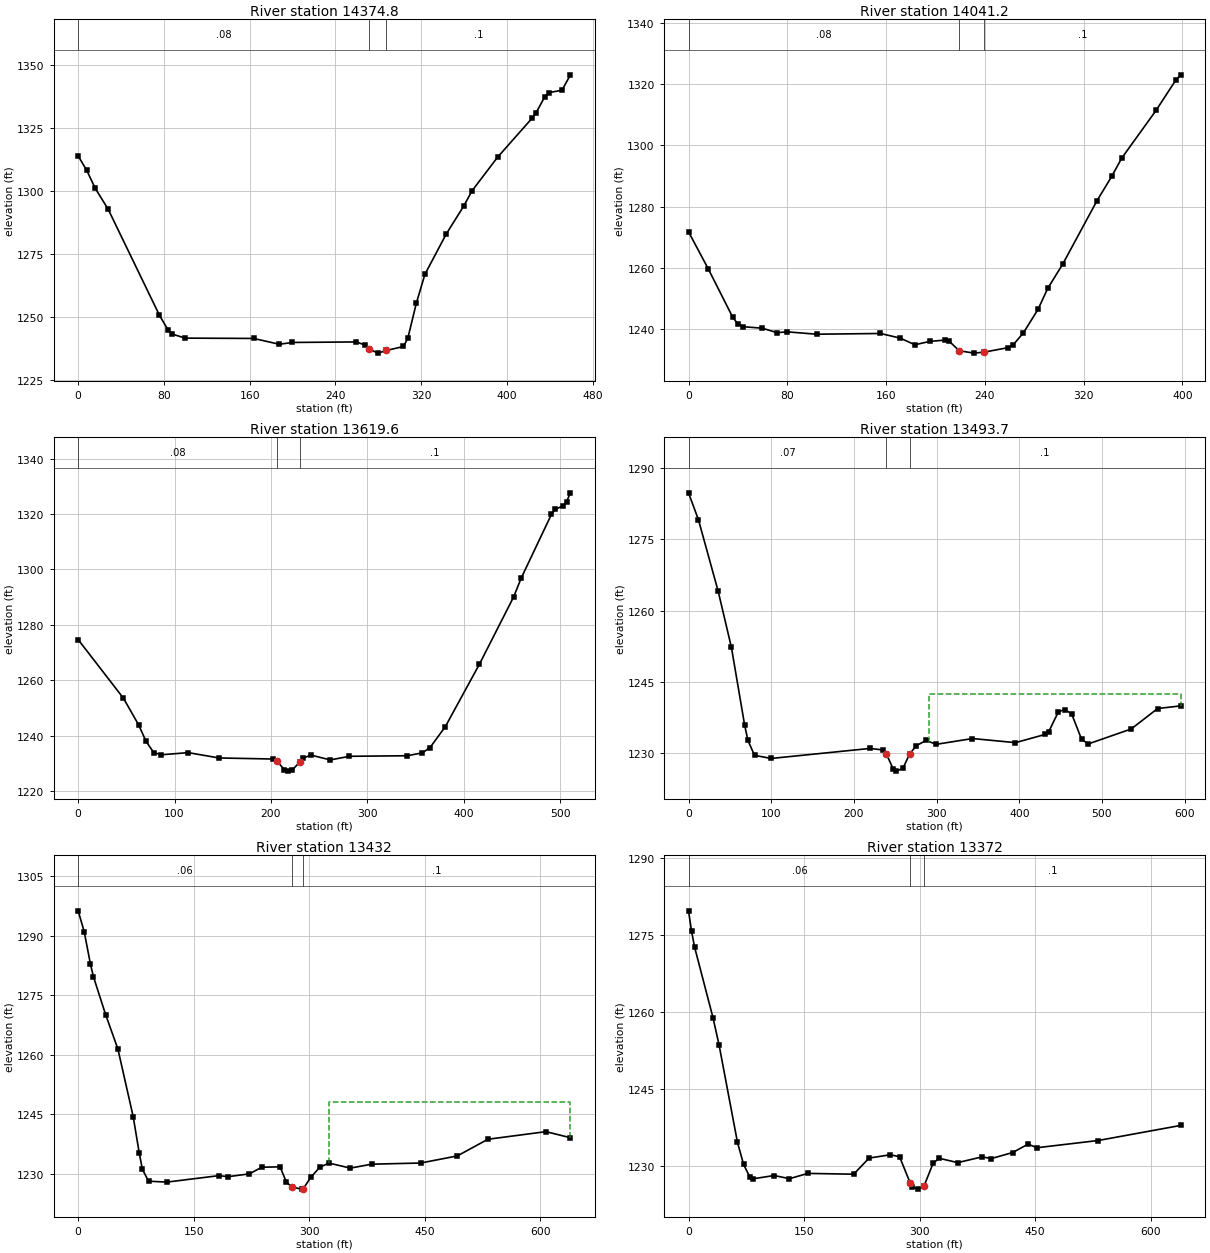
Type RM Length L Ch R = 1 ,14374.8 ,333,333.5,333.3
XS GIS Cut Line= 2
     1795910.826      327547.838      1796369.81      327568.454
#Sta/Elev= 30
       0 1313.74       8 1308.04      16 1300.87      28 1292.63    75.9 1250.55
    83.9 1244.77    87.9 1243.12    99.9 1241.53   163.8  1241.4   187.8 1239.09
   199.8 1239.81   259.7 1240.02   267.7 1238.78   271.7 1237.17   279.7 1235.58
   287.6 1236.63   303.6 1238.21   307.6 1241.42   315.6  1255.4   323.6 1266.84
   343.6 1282.89   359.6 1293.72   367.6 1299.95   391.5  1313.3   423.5 1328.66
   427.5 1330.96   435.5  1337.3   439.5 1338.87   451.5 1339.81   459.4 1345.91
#Mann= 3 , 0 , 0
       0     .08       0   271.7    .045       0   287.6      .1       0
Bank Sta=271.7,287.6
XS Rating Curve= 0 ,0
Exp/Cntr=0.3,0.1

Type RM Length L Ch R = 1 ,14041.2 ,422.2,421.7,421.3
XS GIS Cut Line= 2
     1795957.484      327880.954     1796355.704       327901.57
#Sta/Elev= 30
       0 1271.81      16 1259.69    35.9 1243.81    39.9 1241.73    43.9 1240.81
    59.8  1240.3    71.8 1238.84    79.8 1239.12   103.7 1238.34   155.5 1238.58
   171.5 1237.06   183.4 1234.89   195.4 1235.99   207.4 1236.41   211.3 1235.99
   219.3 1232.94   231.3 1232.16   239.7  1232.5   259.2 1233.97   263.2 1234.96
   271.2 1238.73   283.1 1246.43   291.1 1253.38     303 1261.13     331 1282.02
   342.9 1289.94   350.9 1295.84   378.8 1311.48   394.8 1321.39   398.8 1323.08
#Mann= 3 , 0 , 0
       0     .08       0   219.3    .045       0   239.7      .1       0
Bank Sta=219.3,239.7
XS Rating Curve= 0 ,0
Exp/Cntr=0.3,0.1

Type RM Length L Ch R = 1 ,13619.6 ,127.2,125.9,124.9
XS GIS Cut Line= 4
     1795995.461      328271.579     1796056.225      328307.386
     1796366.555      328317.152     1796479.402      328253.133
#Sta/Elev= 30
       0 1274.68      47 1253.52    62.7 1243.94    70.5 1237.93    78.5 1233.88
    86.4 1233.13   114.3 1233.89   146.2 1231.97   201.9 1231.59   205.9    1231
   213.8  1227.8   217.8 1227.22   221.8 1227.47   229.8 1230.47   233.7 1231.95
   241.7    1233   261.6 1231.26   281.5 1232.57   341.2 1232.77   357.1  1233.8
   365.1 1235.72     381 1243.28   416.4 1265.84   451.8 1290.04   459.6 1296.79
   491.1 1319.89     495 1321.66   502.9 1322.93   506.8 1324.49   510.8 1327.64
#Mann= 3 , 0 , 0
       0     .08       0   205.9    .045       0   229.8      .1       0
Bank Sta=205.9,229.8
XS Rating Curve= 0 ,0
Exp/Cntr=0.3,0.1

Type RM Length L Ch R = 1 ,13493.7 ,56.5,61.7,61.4
XS GIS Cut Line= 3
     1795958.569      328342.109     1796151.711      328437.595
     1796531.486      328431.084
#Sta/Elev= 30
       0 1284.77      12 1279.12    35.9 1264.06    51.9 1252.26    67.8 1236.01
    71.8 1232.73    79.8 1229.59    99.8 1228.92   219.4 1231.03   235.4 1230.71
   239.4 1229.84   247.4 1226.74   251.4 1226.26   259.2 1226.83   267.4 1229.86
   275.4 1231.61   287.4 1232.71   299.4 1231.89   343.4 1233.11   395.4 1232.25
   431.4 1233.98   435.4 1234.48   447.4 1238.78   455.4 1239.19   463.4 1238.25
   475.3 1232.96   483.3 1231.97   535.3 1235.12   567.3 1239.42   595.3 1239.98
#Mann= 3 , 0 , 0
       0     .07       0   239.4    .045       0   267.4      .1       0
#XS Ineff= 2 , 0
                           290.7         1242.41
Permanent Ineff=
       F       F
Bank Sta=239.4,267.4
XS Rating Curve= 0 ,0
Exp/Cntr=0.3,0.1

Type RM Length L Ch R = 1 ,13432   ,65.2,60.1,59.9
XS GIS Cut Line= 3
     1795929.272       328365.98     1796164.732      328498.359
     1796533.656      328489.678
#Sta/Elev= 30
       0 1296.24     7.9 1290.95    15.9 1282.85    19.9 1279.59    35.8    1270
    51.6 1261.41    71.5 1244.32    79.4 1235.08    83.4 1231.08    91.4 1228.08
   115.2 1227.85   182.7 1229.48   194.6 1229.22   222.4 1229.93   238.3  1231.6
   262.2  1231.7   270.1 1227.96   277.2 1226.61     290 1226.08   292.2 1226.15
   301.9 1229.02   313.8 1231.61   325.7 1232.64   353.4 1231.38   381.2 1232.37
   444.7 1232.66   492.3 1234.45     532 1238.65   607.4 1240.57   639.2 1239.04
#Mann= 3 , 0 , 0
       0     .06       0   277.2    .045       0   292.2      .1       0
#XS Ineff= 2 , 0
                          325.51         1248.16
Permanent Ineff=
       F       F
Bank Sta=277.2,292.2
XS Rating Curve= 0 ,0
Exp/Cntr=0.3,0.1

Type RM Length L Ch R = 1 ,13372   ,37.2,43.4,49.5
XS GIS Cut Line= 3
     1795909.741      328425.659     1796145.201      328558.037
     1796514.125      328549.357
#Sta/Elev= 30
       0 1279.77       4 1275.74     7.9 1272.68    31.8 1258.89    39.7 1253.54
    63.6 1234.52    71.5 1230.24    79.4 1227.82    83.4 1227.41   111.2 1228.06
   131.1 1227.44   154.9 1228.47   214.5 1228.32   234.4 1231.46   262.2 1232.12
   274.1 1231.71     288 1226.53     290 1225.88   297.9  1225.4   305.8 1226.01
   317.7  1230.5   325.7 1231.42   349.5 1230.58   381.2  1231.7   393.1 1231.37
   420.9 1232.55   440.8 1234.18   452.6 1233.49     532  1234.9   639.2 1237.85
#Mann= 3 , 0 , 0
       0     .06       0     288    .045       0   305.8      .1       0
Bank Sta=288,305.8
XS Rating Curve= 0 ,0
Exp/Cntr=0.3,0.1

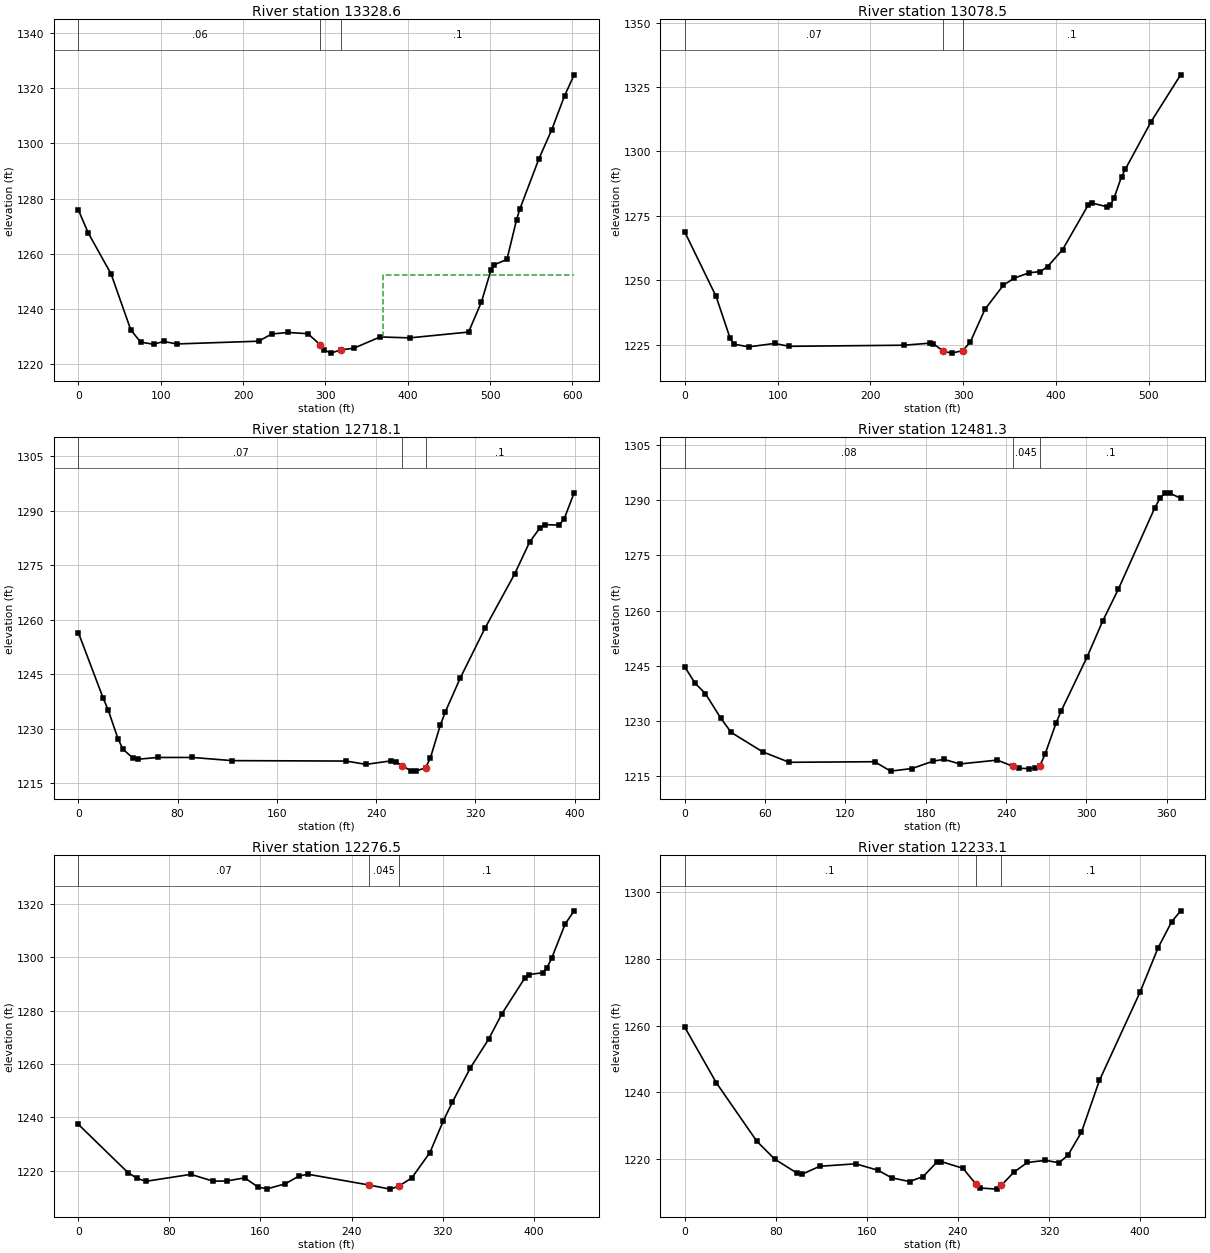
Type RM Length L Ch R = 1 ,13328.6 ,235.9,250,264.1
XS GIS Cut Line= 4
      1795901.06      328444.105     1796115.904      328588.419
     1796320.982      328639.418     1796403.448      328742.499
#Sta/Elev= 30
       0 1275.98      12 1267.62    39.8 1252.74    63.7 1232.52    75.6 1228.09
    91.6  1227.3   103.5 1228.35   119.4 1227.42     219 1228.42   234.9 1231.04
   254.8 1231.57   278.8 1231.14   293.9  1227.1   298.7 1225.25   306.7  1224.1
   318.6 1225.26   334.6 1225.88   366.5 1229.96   402.4 1229.62     474 1231.73
   489.6 1242.65   501.2 1254.21   505.1 1256.07   520.6 1258.04   532.3 1272.47
   536.1 1276.16   559.4 1294.45     575 1304.98   590.5 1317.24   602.2 1324.85
#Mann= 3 , 0 , 0
       0     .06       0   293.9    .045       0   318.6      .1       0
#XS Ineff= 2 , 0
                          370.15         1252.45
Permanent Ineff=
       F       F
Bank Sta=293.9,318.6
XS Rating Curve= 0 ,0
Exp/Cntr=0.3,0.1

Type RM Length L Ch R = 1 ,13078.5 ,360.7,360.5,359.9
XS GIS Cut Line= 3
      1795813.17      328556.952     1795840.296       328592.76
     1796158.222      328964.938
#Sta/Elev= 30
       0 1268.75    33.7 1243.78    48.9 1227.47    52.9 1225.25    68.8 1224.18
    96.7 1225.52   112.6  1224.4   235.9 1224.83   263.8 1225.61   267.8 1225.43
   278.6 1222.52   287.7 1221.76   299.6 1222.74   307.6    1226   323.5 1238.76
   343.4 1248.15   355.3  1250.9   371.2 1252.93   383.2 1253.41   391.1 1255.37
   407.1 1261.86   434.9 1279.31   438.9 1279.98   454.8 1278.58   458.8 1279.26
   462.8 1282.11   470.7  1290.2   474.7 1293.06   502.6 1311.59   534.4 1329.75
#Mann= 3 , 0 , 0
       0     .07       0   278.6    .045       0   299.6      .1       0
Bank Sta=278.6,299.6
XS Rating Curve= 0 ,0
Exp/Cntr=0.3,0.1

Type RM Length L Ch R = 1 ,12718.1 ,241.7,236.7,231.7
XS GIS Cut Line= 2
     1795563.604      328817.369     1795829.446      329115.763
#Sta/Elev= 30
       0 1256.44      20  1238.4      24 1235.19      32 1227.16      36 1224.33
      44 1221.89      48 1221.58    63.9 1222.07    91.9 1222.07   123.9  1221.2
   215.8 1221.08   231.8 1220.17   251.8 1221.12   255.8 1220.91   261.2 1219.77
   267.8 1218.42   271.8 1218.31   279.8 1219.21   283.7 1221.91   291.7 1230.92
   295.7 1234.55   307.7 1243.84   327.7 1257.61   351.7 1272.59   363.7 1281.32
   371.7 1285.08   375.7 1286.12   387.6    1286   391.6 1287.77   399.6 1294.87
#Mann= 3 , 0 , 0
       0     .07       0   261.2    .045       0   279.8      .1       0
Bank Sta=261.2,279.8
XS Rating Curve= 0 ,0
Exp/Cntr=0.3,0.1

Type RM Length L Ch R = 1 ,12481.3 ,179.7,204.8,230.3
XS GIS Cut Line= 4
     1795404.099      329047.404     1795435.566      329086.466
     1795620.027      329218.845     1795690.557      329279.609
#Sta/Elev= 30
       0 1244.65     7.7 1240.22    15.4  1237.4      27 1230.64    34.7 1226.83
    58.1 1221.57      78 1218.71   141.8 1218.87   153.7 1216.31   169.7 1217.02
   185.6 1219.04   193.6 1219.51   205.5 1218.26   233.4 1219.31   244.8 1217.66
   249.3 1217.08   257.3    1217   261.3 1217.12   265.3 1217.83   269.2 1221.06
   277.2 1229.32   281.1 1232.68   300.5  1247.4   312.1 1257.14   323.8 1265.81
   350.9 1287.85   354.8  1290.5   358.7 1292.02   362.5 1291.84   370.3 1290.58
#Mann= 3 , 0 , 0
       0     .08       0   244.8    .045       0   265.3      .1       0
Bank Sta=244.8,265.3
XS Rating Curve= 0 ,0
Exp/Cntr=0.3,0.1

Type RM Length L Ch R = 1 ,12276.5 ,38,43.5,34.4
XS GIS Cut Line= 4
      1795298.84      329209.656     1795491.549      329347.676
     1795475.056      329392.815     1795594.847      329483.961
#Sta/Elev= 30
       0 1237.38    43.5  1219.3    51.4 1217.19    59.3    1216    98.8 1218.61
   118.5 1216.05   130.4 1216.13   146.2  1217.3     158  1213.8   165.9 1213.18
   181.7 1215.05   193.6 1217.92   201.5 1218.67   255.5 1214.61     274 1213.07
   281.4 1214.13     293 1217.31   308.9 1226.81   320.7 1238.75   328.7 1245.78
   344.5 1258.63   360.4 1269.29   372.2 1278.92     392 1292.11     396  1293.6
   407.9 1294.26   411.8 1296.21   415.8 1299.68   427.7 1312.57   435.6  1317.5
#Mann= 3 , 0 , 0
       0     .07       0   255.5    .045       0   281.4      .1       0
Bank Sta=255.5,281.4
XS Rating Curve= 0 ,0
Exp/Cntr=0.3,0.1

Type RM Length L Ch R = 1 ,12233.1 ,134.5,103.7,85.3
XS GIS Cut Line= 4
      1795258.91      329206.183     1795451.618      329344.204
     1795435.125      329389.343     1795554.917      329480.489
#Sta/Elev= 30
       0 1259.47    27.6 1242.91    63.2 1225.39      79    1220    98.8 1215.77
   102.7 1215.45   118.5 1217.86   150.1 1218.61   169.9 1216.66   181.7 1214.42
   197.5  1213.3   209.4  1214.8   221.2 1219.03   225.2 1219.28   244.4 1217.26
   255.5 1212.63   259.2 1211.38     274 1211.03   278.1 1212.19   289.1  1216.1
   300.9    1219   316.8 1219.65   328.7 1218.92   336.6 1221.16   348.5 1228.09
   364.3  1243.6     400 1270.01   415.8 1283.26   427.7 1291.02   435.6 1294.32
#Mann= 3 , 0 , 0
       0      .1       0   255.5    .045       0   278.1      .1       0
Bank Sta=255.5,278.1
XS Rating Curve= 0 ,0
Exp/Cntr=0.3,0.1

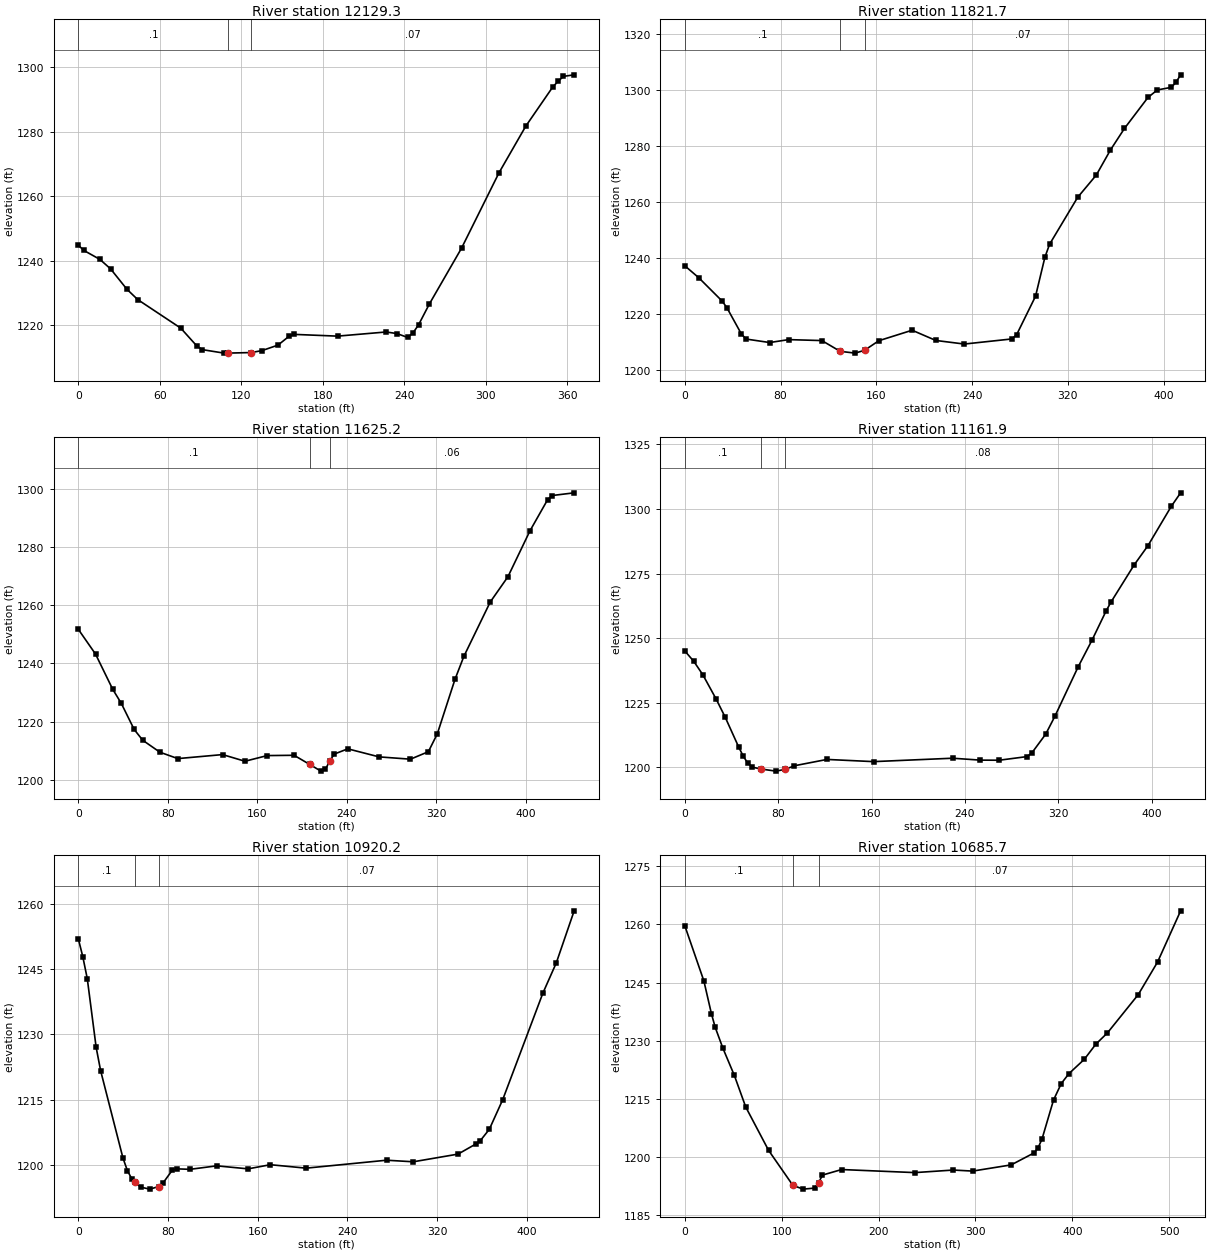
Type RM Length L Ch R = 1 ,12129.3 ,308.9,307.6,306
XS GIS Cut Line= 4
     1795251.104      329323.011     1795304.272      329370.754
     1795458.352      329469.496     1795548.413      329533.515
#Sta/Elev= 30
       0 1244.77       4 1243.17    15.9 1240.37    23.8 1237.41    35.7 1231.15
    43.7 1227.92    75.4 1219.06    87.4 1213.45    91.4 1212.38   107.3 1211.31
   110.5 1211.32   127.2 1211.49   135.1 1212.08     147  1213.8     155  1216.5
     159 1217.12   190.8 1216.58   226.6 1217.87   234.6 1217.37   242.5 1216.16
   246.5 1217.66   250.5 1220.12   258.4 1226.54   282.1 1243.86   309.7 1267.26
   329.4  1281.7   349.2 1293.81   353.1 1295.57   357.1 1297.13     365 1297.61
#Mann= 3 , 0 , 0
       0      .1       0   110.5    .045       0   127.2     .07       0
Bank Sta=110.5,127.2
XS Rating Curve= 0 ,0
Exp/Cntr=0.3,0.1

Type RM Length L Ch R = 1 ,11821.7 ,207.1,196.5,185.2
XS GIS Cut Line= 4
     1795112.215      329602.959     1795141.512      329622.491
     1795366.121      329740.763     1795470.288      329810.208
#Sta/Elev= 30
       0 1237.32    11.7 1233.04    31.3 1224.68    35.2 1222.33    47.1 1213.11
    51.1 1211.18    70.9 1209.93    86.8 1210.97   114.5 1210.63   129.8 1206.79
   142.3 1206.15   150.2 1207.17   162.1 1210.58   189.9 1214.32   209.7 1210.67
   233.5 1209.39   273.2 1211.21   277.2 1212.72     293 1226.45   300.8 1240.33
   304.7 1244.98   328.2 1261.75   343.8 1269.72   355.6 1278.66   367.3 1286.34
   386.9 1297.37   394.7 1300.06   406.4 1300.99   410.3 1302.77   414.2 1305.46
#Mann= 3 , 0 , 0
       0      .1       0   129.8    .045       0   150.2     .07       0
Bank Sta=129.8,150.2
XS Rating Curve= 0 ,0
Exp/Cntr=0.3,0.1

Type RM Length L Ch R = 1 ,11625.2 ,462.5,463.3,461.9
XS GIS Cut Line= 4
     1794992.857      329864.461     1795065.557      329859.036
     1795317.293      329866.631     1795433.395      329889.418
#Sta/Elev= 30
       0 1251.74    15.4 1243.21    30.7 1231.14    38.4 1226.27    49.9 1217.29
    57.6 1213.57    72.9 1209.47    88.9 1207.27   128.9 1208.65   148.9 1206.36
   168.8 1208.31   192.8 1208.41   206.6  1205.3   216.8 1202.96   220.8 1203.54
   224.8 1206.59   228.8 1208.84   240.8 1210.63   268.8 1207.86   296.8 1207.07
   312.8 1209.64   320.8 1215.79   336.6 1234.54   344.5 1242.41   368.1 1261.14
   383.9 1269.83   403.6 1285.63   419.4 1296.36   423.4 1297.78   443.1 1298.71
#Mann= 3 , 0 , 0
       0      .1       0   206.6    .045       0   224.8     .06       0
Bank Sta=206.6,224.8
XS Rating Curve= 0 ,0
Exp/Cntr=0.3,0.1

Type RM Length L Ch R = 1 ,11161.9 ,233.5,241.7,248.1
XS GIS Cut Line= 3
     1795006.963        330232.3     1795051.451      330244.235
      1795430.14      330244.235
#Sta/Elev= 30
       0 1245.02     7.7 1240.98    15.4 1235.83    26.9 1226.34    34.6 1219.36
    46.1 1207.86      50 1204.32      54 1201.49      58 1199.98    65.3 1199.28
      78 1198.46    85.9 1199.12    93.9 1200.54   121.8 1202.99   161.7 1202.14
   229.4 1203.46   253.3 1202.72   269.3 1202.68   293.2 1204.09   297.2 1205.43
   309.2 1212.78   317.1 1219.72     337 1238.85     349  1249.3     361 1260.55
     365 1263.84   384.9 1278.28   396.8 1285.78   416.8 1301.03   424.8 1306.26
#Mann= 3 , 0 , 0
       0      .1       0    65.3    .045       0    85.9     .08       0
Bank Sta=65.3,85.9
XS Rating Curve= 0 ,0
Exp/Cntr=0.3,0.1

Type RM Length L Ch R = 1 ,10920.2 ,233.9,234.5,234.8
XS GIS Cut Line= 2
     1794946.199      330451.484     1795366.121      330590.373
#Sta/Elev= 30
       0 1251.88       4 1247.79       8 1242.73    15.9    1227    19.9 1221.65
    39.8 1201.64    43.8 1198.72    47.8 1196.81    50.5 1196.07    55.8 1194.94
    63.8  1194.5    71.7 1195.09    75.7 1195.96    83.7  1198.8    87.7 1199.15
    99.6 1199.04   123.5 1199.84   151.4 1199.15   171.3  1200.1   203.2 1199.31
   274.9 1201.13   298.8 1200.77   338.7 1202.53   354.6 1204.85   358.6 1205.62
   366.6 1208.21   378.5 1214.97   414.4 1239.45   426.4 1246.41   442.3 1258.32
#Mann= 3 , 0 , 0
       0      .1       0    50.5    .045       0    71.7     .07       0
Bank Sta=50.5,71.7
XS Rating Curve= 0 ,0
Exp/Cntr=0.3,0.1

Type RM Length L Ch R = 1 ,10685.7 ,380.7,373.8,366.8
XS GIS Cut Line= 3
     1794860.479      330642.456     1794941.859      330690.199
     1795333.569      330834.513
#Sta/Elev= 30
       0 1259.66    19.7 1245.42    27.5 1236.96    31.4 1233.46    39.3  1228.1
    51.1  1221.1    62.9 1212.93    86.5 1201.75   111.6 1192.72   122.2 1191.76
   134.1 1192.03   138.1 1193.42   142.1 1195.38   161.9 1196.81   237.5 1196.02
   277.2 1196.68   297.1 1196.41   336.9 1198.01   360.7 1201.12   364.7 1202.43
   368.7 1204.66   380.6 1214.72   388.6 1218.98   396.5 1221.53   412.4 1225.23
   424.3 1229.13   436.3 1232.05   468.1 1241.92     488  1250.3   511.8  1263.5
#Mann= 3 , 0 , 0
       0      .1       0   111.6    .045       0   138.1     .07       0
Bank Sta=111.6,138.1
XS Rating Curve= 0 ,0
Exp/Cntr=0.3,0.1

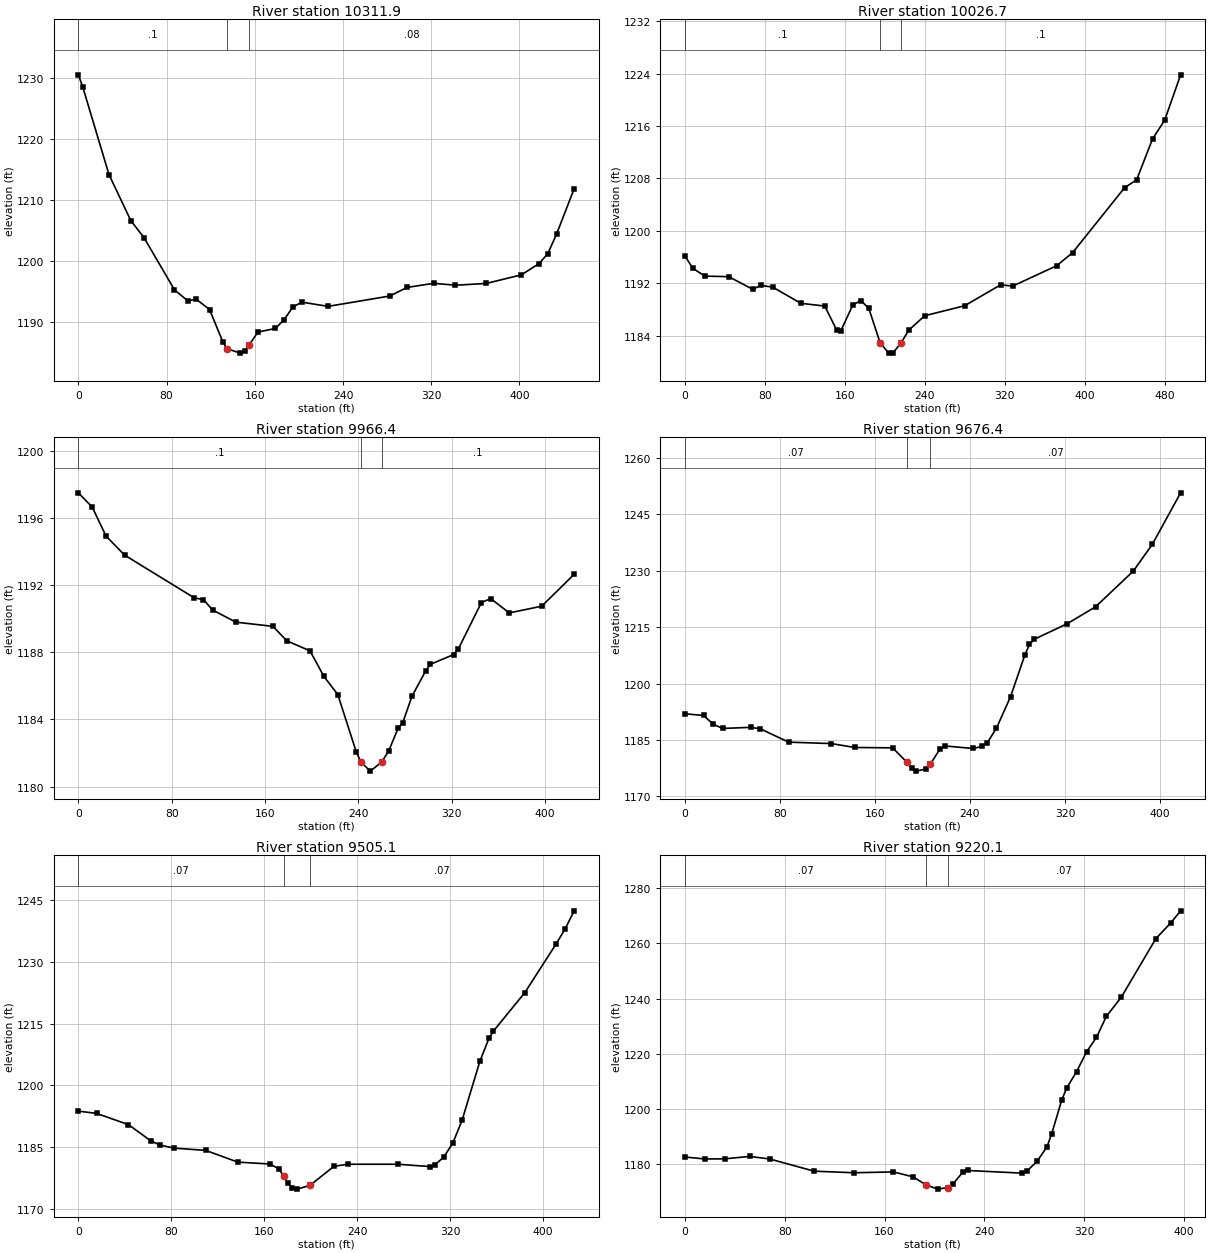
Type RM Length L Ch R = 1 ,10311.9 ,286.2,285.2,284.2
XS GIS Cut Line= 3
     1794851.798      330994.018     1794937.519      331064.548
      1795276.06      331067.803
#Sta/Elev= 30
       0 1230.46       4 1228.48    27.8 1214.14    47.6 1206.61    59.5 1203.83
    87.2 1195.28    99.1 1193.51     107 1193.74     119 1192.06   130.9 1186.83
   134.9 1185.65   146.8 1184.93   150.8 1185.23   154.8 1186.22   162.8 1188.38
   178.7 1188.96   186.7 1190.43   194.6 1192.49   202.6 1193.27   226.5 1192.58
   282.3 1194.27   298.2 1195.68   322.1 1196.35     342 1196.04   369.9 1196.33
   401.8 1197.74   417.7 1199.57   425.7 1201.21   433.6 1204.38   449.6 1211.83
#Mann= 3 , 0 , 0
       0      .1       0   134.9    .045       0   154.8     .08       0
Bank Sta=134.9,154.8
XS Rating Curve= 0 ,0
Exp/Cntr=0.3,0.1

Type RM Length L Ch R = 1 ,10026.7 ,64.9,60.4,55.9
XS GIS Cut Line= 2
     1794808.395      331342.326     1795304.272      331343.411
#Sta/Elev= 30
       0 1196.21       8 1194.29      20  1193.1      44 1193.01      68 1191.08
      76 1191.69      88 1191.41     116 1188.95     140 1188.53     152 1184.84
     156 1184.72     168 1188.69     176 1189.37     184  1188.2   195.4 1182.89
     204 1181.35     208 1181.36     216 1182.84   223.9 1184.83   239.9 1187.05
   279.9 1188.58   315.9 1191.77   327.9 1191.57   371.9 1194.68   387.9 1196.68
   439.9 1206.59   451.9 1207.78   467.9 1214.05   479.9 1216.86   495.9  1223.8
#Mann= 3 , 0 , 0
       0      .1       0   195.4    .045       0     216      .1       0
Bank Sta=195.4,216
XS Rating Curve= 0 ,0
Exp/Cntr=0.3,0.1

Type RM Length L Ch R = 1 ,9966.4  ,278.3,290,301.2
XS GIS Cut Line= 2
     1794773.673      331451.918      1795190.34      331368.367
#Sta/Elev= 30
       0 1197.49    11.9 1196.64    23.8 1194.91    39.7 1193.78    99.3 1191.24
   107.2 1191.13   115.2 1190.51     135 1189.79   166.8 1189.54   178.7 1188.68
   198.6 1188.08   210.5 1186.56   222.4 1185.48   238.3 1182.05   242.3 1181.46
   250.2 1180.92   259.9 1181.45   266.1 1182.13     274 1183.46     278 1183.79
     286 1185.38   297.9 1186.91   301.8 1187.28   321.7 1187.86   325.7 1188.19
   345.5 1190.96   353.5 1191.19   369.4 1190.34   397.2 1190.74     425 1192.64
#Mann= 3 , 0 , 0
       0      .1       0   242.3    .045       0   259.9      .1       0
Bank Sta=242.3,259.9
XS Rating Curve= 0 ,0
Exp/Cntr=0.3,0.1

Type RM Length L Ch R = 1 ,9676.4  ,176.4,171.3,166.4
XS GIS Cut Line= 2
     1794789.949      331622.274      1795188.17      331747.057
#Sta/Elev= 30
       0 1191.98    15.9 1191.52    23.8 1189.22    31.8 1188.08    55.6 1188.37
    63.6 1187.97    87.4 1184.44   123.2 1184.06   143.1 1183.02   174.9 1182.93
   186.8 1179.15   190.8 1177.52   194.8 1176.74   202.7 1177.31   206.7 1178.61
   214.6 1182.53   218.6 1183.44   242.4 1182.76   250.4  1183.3   254.4 1184.18
   262.3 1188.16   274.2 1196.55   286.2 1207.61   290.1 1210.39   294.1 1211.76
   321.9 1215.92   345.8 1220.42   377.6 1229.93   393.5 1237.01   417.3 1250.68
#Mann= 3 , 0 , 0
       0     .07       0   186.8    .045       0   206.7     .07       0
Bank Sta=186.8,206.7
XS Rating Curve= 0 ,0
Exp/Cntr=0.3,0.1

Type RM Length L Ch R = 1 ,9505.1  ,286.7,285,281.9
XS GIS Cut Line= 4
     1794753.057      331804.565     1794860.479      331841.458
     1795076.408      331858.819     1795166.468      331824.096
#Sta/Elev= 30
       0 1193.78    15.7 1193.23    43.1 1190.51    62.7 1186.51    70.5 1185.56
    82.2 1184.82   109.7 1184.26   137.2 1181.42   164.8 1180.97   172.7 1179.79
   176.6 1178.05   180.5 1176.27   184.3 1175.26   188.4 1174.88   199.3 1175.78
   219.9 1180.39   231.7 1180.91   275.1 1180.91   302.6 1180.34   306.6 1180.72
   314.4  1182.6   322.3 1186.06   330.2 1191.52   345.6 1205.89   353.4 1211.43
   357.2 1213.16   384.3 1222.52   411.3 1234.34     419 1237.98   426.7 1242.31
#Mann= 3 , 0 , 0
       0     .07       0   176.6    .045       0   199.3     .07       0
Bank Sta=176.6,199.3
XS Rating Curve= 0 ,0
Exp/Cntr=0.3,0.1

Type RM Length L Ch R = 1 ,9220.1  ,236.9,246.6,256.1
XS GIS Cut Line= 3
     1794809.481      332166.978     1794872.415      332124.661
     1795193.595       332113.81
#Sta/Elev= 30
       0 1182.56      16 1181.84    31.9 1181.88    51.9 1182.76    67.9 1181.85
   103.6 1177.41   135.4 1176.84   167.1 1177.14     183 1175.34   193.1 1172.45
   202.8  1170.9   210.7 1171.49   214.7 1172.71   222.6 1176.98   226.6 1177.66
   270.2  1176.7   274.2 1177.48   282.2    1181   290.1 1186.17     294 1191.07
     302  1203.3     306 1207.62   313.9 1213.55   321.8 1220.64   329.8 1225.95
   337.7 1233.55   349.6 1240.46   377.4 1261.78   389.3 1267.46   397.2 1271.84
#Mann= 3 , 0 , 0
       0     .07       0   193.1    .045       0   210.7     .07       0
Bank Sta=193.1,210.7
XS Rating Curve= 0 ,0
Exp/Cntr=0.3,0.1

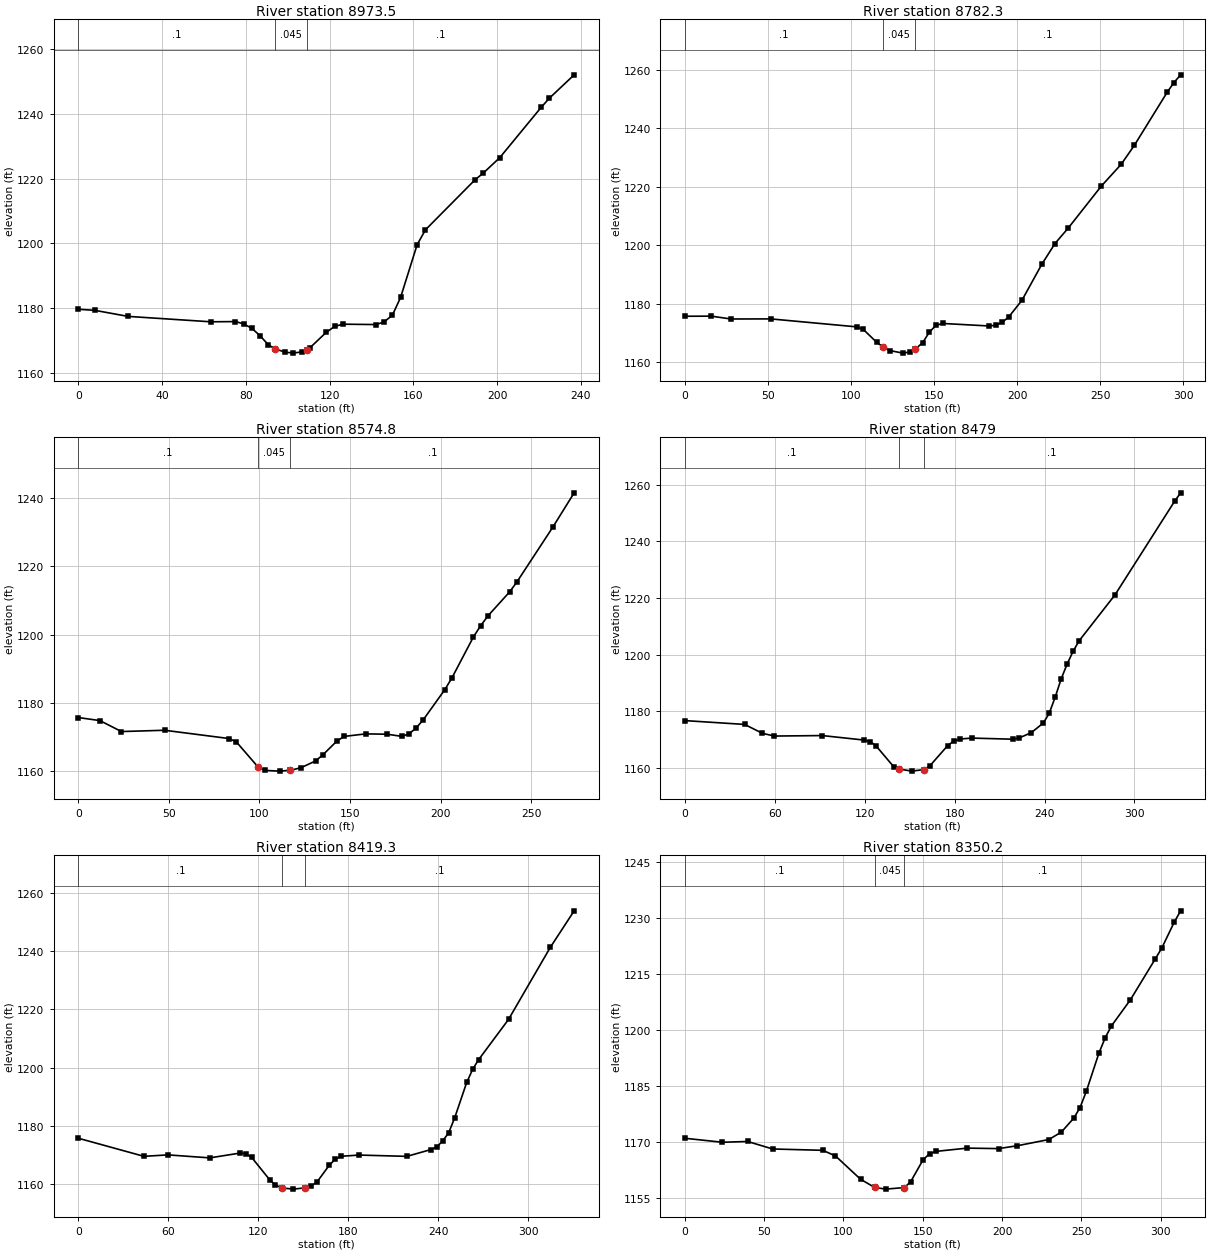
Type RM Length L Ch R = 1 ,8973.5  ,200,191.2,182
XS GIS Cut Line= 2
     1794898.456      332323.228     1795116.555      332415.459
#Sta/Elev= 30
       0 1179.59     7.9 1179.26    23.7 1177.39    63.2 1175.72      75 1175.78
    78.9  1175.1    82.9 1173.68    86.8  1171.4    90.8 1168.57      94 1167.33
    98.7 1166.35   102.6 1166.03   106.6 1166.41     109 1167.15   110.5 1167.61
   118.4 1172.46   122.4 1174.28   126.3 1174.98   142.1 1174.86     146 1175.66
     150 1177.77   153.9 1183.24   161.8 1199.55   165.8 1204.17   189.4 1219.59
   193.4  1221.7   201.3 1226.49     221 1241.99     225 1244.88   236.8 1252.08
#Mann= 3 , 0 , 0
       0      .1       0      94    .045       0     109      .1       0
Bank Sta=94,109
XS Rating Curve= 0 ,0
Exp/Cntr=0.3,0.1

Type RM Length L Ch R = 1 ,8782.3  ,213.7,207.5,201.4
XS GIS Cut Line= 2
     1794833.352      332551.093     1795131.746      332551.093
#Sta/Elev= 30
       0 1175.68    15.9 1175.71    27.8 1174.74    51.7 1174.77   103.4 1172.05
   107.4 1171.18   115.4  1166.8   119.4 1165.12   123.3 1163.94   131.3 1163.05
   135.3 1163.44   138.7  1164.4   143.2 1166.67   147.2 1170.25   151.2 1172.58
   155.2 1173.21     183 1172.35     187 1172.58     191 1173.57     195 1175.47
   202.9 1181.14   214.8 1193.42   222.8 1200.59   230.8  1205.9   250.6  1220.2
   262.6 1227.69   270.5 1234.16   290.4 1252.46   294.4 1255.72   298.4 1258.35
#Mann= 3 , 0 , 0
       0      .1       0   119.4    .045       0   138.7      .1       0
Bank Sta=119.4,138.7
XS Rating Curve= 0 ,0
Exp/Cntr=0.3,0.1

Type RM Length L Ch R = 1 ,8574.8  ,95.4,95.8,96.2
XS GIS Cut Line= 2
     1794888.691      332783.298     1795152.362      332709.513
#Sta/Elev= 30
       0 1175.78    11.9 1174.89    23.8 1171.68    47.6 1172.06    83.3 1169.63
    87.3 1168.63    99.2 1161.33   103.2 1160.31   111.1  1160.1   117.1 1160.35
     123  1161.1     131 1163.09   134.9 1164.79   142.8 1168.91   146.8 1170.26
   158.7    1171   170.6  1170.9   178.6 1170.27   182.5 1170.98   186.5 1172.69
   190.5 1175.15   202.4 1183.96   206.3 1187.38   218.2  1199.4   222.2 1202.67
   226.2 1205.54   238.1 1212.51   242.1 1215.39   261.9  1231.4   273.8 1241.54
#Mann= 3 , 0 , 0
       0      .1       0    99.2    .045       0   117.1      .1       0
Bank Sta=99.2,117.1
XS Rating Curve= 0 ,0
Exp/Cntr=0.3,0.1

Type RM Length L Ch R = 1 ,8479    ,59.7,59.6,59.7
XS GIS Cut Line= 2
     1794889.776      332877.699     1795209.871      332794.149
#Sta/Elev= 30
       0 1176.64    39.9 1175.29    51.8 1172.14    59.8 1171.18    91.7 1171.35
   119.6 1169.76   123.6 1169.24   127.6  1167.7   139.5 1160.25     143 1159.51
   151.5 1158.78   159.4 1159.32   163.4 1160.59   175.4 1167.81   179.4 1169.39
   183.4 1170.11   191.3 1170.46   219.2 1170.06   223.2 1170.52   231.2  1172.4
   239.2 1175.78   243.1  1179.2   247.1  1184.9   251.1 1191.37   255.1 1196.66
   259.1 1201.18   263.1 1204.86     287 1221.07   326.8 1254.18   330.8 1257.15
#Mann= 3 , 0 , 0
       0      .1       0     143    .045       0   159.4      .1       0
Bank Sta=143,159.4
XS Rating Curve= 0 ,0
Exp/Cntr=0.3,0.1

Type RM Length L Ch R = 1 ,8419.3  ,69.7,69.2,68.6
XS GIS Cut Line= 2
     1794913.647      332933.037     1795233.743      332849.487
#Sta/Elev= 30
       0 1175.66    43.8 1169.43    59.8 1169.93    87.7  1168.9   107.6 1170.53
   111.6 1170.39   115.6 1169.09   127.6  1161.4   131.5 1159.53     136 1158.53
   143.5 1158.14   151.5  1158.6   155.4 1159.18   159.4 1160.72   167.4 1166.34
   171.4 1168.48   175.4 1169.45   187.3 1169.87   219.2 1169.42   235.2 1171.76
   239.2 1172.68   243.1 1174.74   247.1 1177.56   251.1  1182.7   259.1 1194.87
   263.1 1199.39     267 1202.67     287 1216.56   314.9 1241.39   330.8 1253.96
#Mann= 3 , 0 , 0
       0      .1       0     136    .045       0   151.5      .1       0
Bank Sta=136,151.5
XS Rating Curve= 0 ,0
Exp/Cntr=0.3,0.1

Type RM Length L Ch R = 1 ,8350.2  ,262.2,260.5,258.9
XS GIS Cut Line= 2
     1794945.114      332999.227     1795245.678      332913.506
#Sta/Elev= 30
       0 1170.93    23.7 1169.86    39.6 1170.07    55.4 1168.06      87  1167.7
      95 1166.19   110.8 1159.96   119.6 1157.78   126.6 1157.31   138.5 1157.73
   142.4  1159.3   150.3 1165.22   154.3 1166.76   158.2 1167.41     178 1168.29
   197.8 1168.16   209.7 1168.93   229.5 1170.59   237.4 1172.58   245.3 1176.35
   249.2 1179.16   253.2 1183.56   261.1 1193.75   265.1 1197.89     269 1201.03
   280.9 1207.98   296.7 1219.01   300.7 1221.84   308.6 1228.82   312.6 1231.83
#Mann= 3 , 0 , 0
       0      .1       0   119.6    .045       0   138.5      .1       0
Bank Sta=119.6,138.5
XS Rating Curve= 0 ,0
Exp/Cntr=0.3,0.1

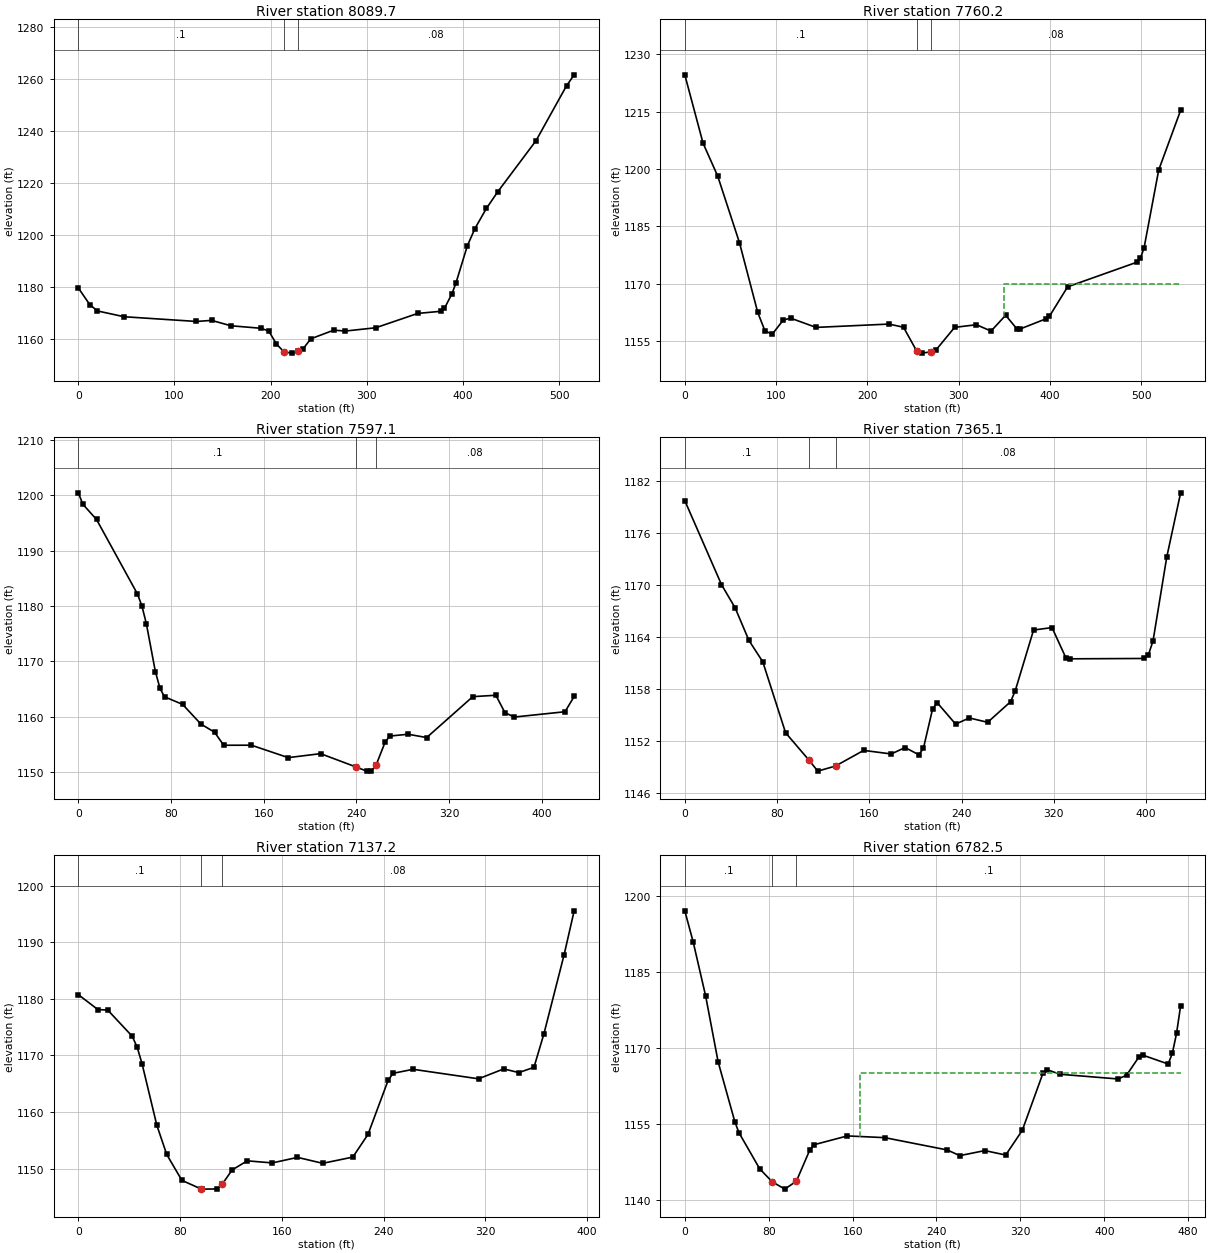
Type RM Length L Ch R = 1 ,8089.7  ,328.8,329.5,330.3
XS GIS Cut Line= 3
     1794909.307      333259.643     1795104.619      333226.006
     1795403.013      333117.499
#Sta/Elev= 30
       0 1179.56    11.9 1173.15    19.8 1170.71    47.6 1168.47   122.9 1166.65
   138.7 1167.07   158.6 1164.99   190.3 1164.01   198.2 1162.89   206.1 1157.92
   213.9 1154.93     222 1154.44   228.9 1155.12   233.9 1156.17   241.8 1159.96
   265.7  1163.3   277.6 1162.95   309.3 1164.22     353 1169.75   376.8 1170.56
   380.8  1171.7   388.7 1177.42   392.7 1181.43   404.6 1195.81   412.5 1202.48
   424.4 1210.21   436.3 1216.69     476 1236.33   507.8 1257.54   515.7 1261.74
#Mann= 3 , 0 , 0
       0      .1       0   213.9    .045       0   228.9     .08       0
Bank Sta=213.9,228.9
XS Rating Curve= 0 ,0
Exp/Cntr=0.3,0.1

Type RM Length L Ch R = 1 ,7760.2  ,163,163.1,163
XS GIS Cut Line= 2
     1794996.112       333605.78     1795512.606      333437.595
#Sta/Elev= 30
       0 1224.59      20 1206.73      36 1198.17    59.9 1180.74    79.9 1162.53
    87.9 1157.65    95.9 1156.87   107.8  1160.5   115.8 1161.04   143.8 1158.61
   223.7 1159.48   239.6 1158.65   254.2 1152.38   259.6 1151.89   269.2  1152.2
   275.6 1152.83   295.6 1158.62   319.5 1159.31   335.5 1157.65   351.5 1161.78
   363.5 1158.32   367.4  1158.2   395.4 1160.83   399.4 1161.49   419.4 1169.21
   495.3 1175.64   499.2  1176.7   503.2 1179.45   519.2 1199.74   543.2 1215.32
#Mann= 3 , 0 , 0
       0      .1       0   254.2    .045       0   269.2     .08       0
#XS Ineff= 2 , 0
                          349.69          1169.9
Permanent Ineff=
       F       F
Bank Sta=254.2,269.2
XS Rating Curve= 0 ,0
Exp/Cntr=0.3,0.1

Type RM Length L Ch R = 1 ,7597.1  ,232.8,231.9,230.2
XS GIS Cut Line= 3
     1795065.557      333719.713     1795175.149      333718.628
     1795477.883      333619.886
#Sta/Elev= 30
       0 1200.47     3.9  1198.4    15.7 1195.65    50.9 1182.23    54.8 1180.08
    58.7 1176.82    66.5 1168.14    70.5  1165.1    74.4 1163.58      90 1162.21
   105.7 1158.67   117.6 1157.17   125.5 1154.82   149.4 1154.83   181.2 1152.58
   209.1  1153.3     240 1150.87   248.9 1150.14   252.9 1150.14   256.9 1151.17
   264.8 1155.37   268.8 1156.48   284.7 1156.81   300.7 1156.21   340.5 1163.61
   360.4 1163.86   368.3  1160.7   376.3 1159.92   420.1 1160.88     428 1163.64
#Mann= 3 , 0 , 0
       0      .1       0     240    .045       0   256.9     .08       0
Bank Sta=240,256.9
XS Rating Curve= 0 ,0
Exp/Cntr=0.3,0.1

Type RM Length L Ch R = 1 ,7365.1  ,225.4,228,231.2
XS GIS Cut Line= 3
     1795187.085      333976.874     1795236.998      333915.025
     1795571.199      333809.774
#Sta/Elev= 30
       0 1179.74    31.8 1170.06    43.7 1167.36    55.6 1163.62    67.6 1161.16
    87.4 1152.97   107.4 1149.86   115.3 1148.55   130.7 1149.14   155.1 1150.94
     179 1150.53     191 1151.27   202.9 1150.44   206.9 1151.19   214.8  1155.7
   218.8 1156.45   234.8 1153.97   246.7 1154.68   262.6 1154.18   282.5 1156.56
   286.5 1157.82   302.4 1164.82   318.4  1165.1   330.3 1161.65   334.3  1161.5
     398 1161.54     402 1161.97     406 1163.58   417.9 1173.25   429.9 1180.64
#Mann= 3 , 0 , 0
       0      .1       0   107.4    .045       0   130.7     .08       0
Bank Sta=107.4,130.7
XS Rating Curve= 0 ,0
Exp/Cntr=0.3,0.1

Type RM Length L Ch R = 1 ,7137.2  ,341.2,354.7,367.3
XS GIS Cut Line= 3
     1795266.295      334122.274     1795325.974      334095.147
     1795640.644      334017.022
#Sta/Elev= 30
       0 1180.75    15.4 1178.11    23.1 1178.03    42.4 1173.39    46.3 1171.43
    50.1 1168.54    61.7 1157.68    69.5 1152.51    81.4 1147.94    96.7  1146.4
    97.2 1146.39     109 1146.42     113 1147.22   120.9 1149.78   132.8 1151.39
   152.5 1151.02   172.3    1152   192.1 1150.95   215.8 1152.05   227.7 1156.05
   243.5 1165.59   247.4 1166.85   263.2 1167.56   314.6 1165.88   334.4 1167.63
   346.3 1166.98   358.2 1167.91     366 1173.81   381.9  1187.8   389.8 1195.56
#Mann= 3 , 0 , 0
       0      .1       0    96.7    .045       0     113     .08       0
Bank Sta=96.7,113
XS Rating Curve= 0 ,0
Exp/Cntr=0.3,0.1

Type RM Length L Ch R = 1 ,6782.5  ,306,304.9,304
XS GIS Cut Line= 2
     1795228.317      334400.051     1795676.451      334550.876
#Sta/Elev= 30
       0 1197.06       8 1190.92    19.9 1180.24    31.8 1167.27    47.7 1155.48
    51.6 1153.33    71.5 1146.17    83.4 1143.63    95.4 1142.19   106.4 1143.76
   119.2 1149.91   123.2 1150.94     155 1152.68   190.7 1152.34   250.3 1149.91
   262.2 1148.79   286.1 1149.79     306 1148.91   321.8 1153.78   341.7 1165.14
   345.7 1165.73   357.6 1164.84   413.2 1163.91   421.2 1164.65   433.1 1168.26
   437.1 1168.58   460.9 1166.86   464.9 1168.96   468.9 1172.89   472.8 1178.34
#Mann= 3 , 0 , 0
       0      .1       0    83.4    .045       0   106.4      .1       0
#XS Ineff= 2 , 0
                           167.4          1165.1
Permanent Ineff=
       F       F
Bank Sta=83.4,106.4
XS Rating Curve= 0 ,0
Exp/Cntr=0.3,0.1