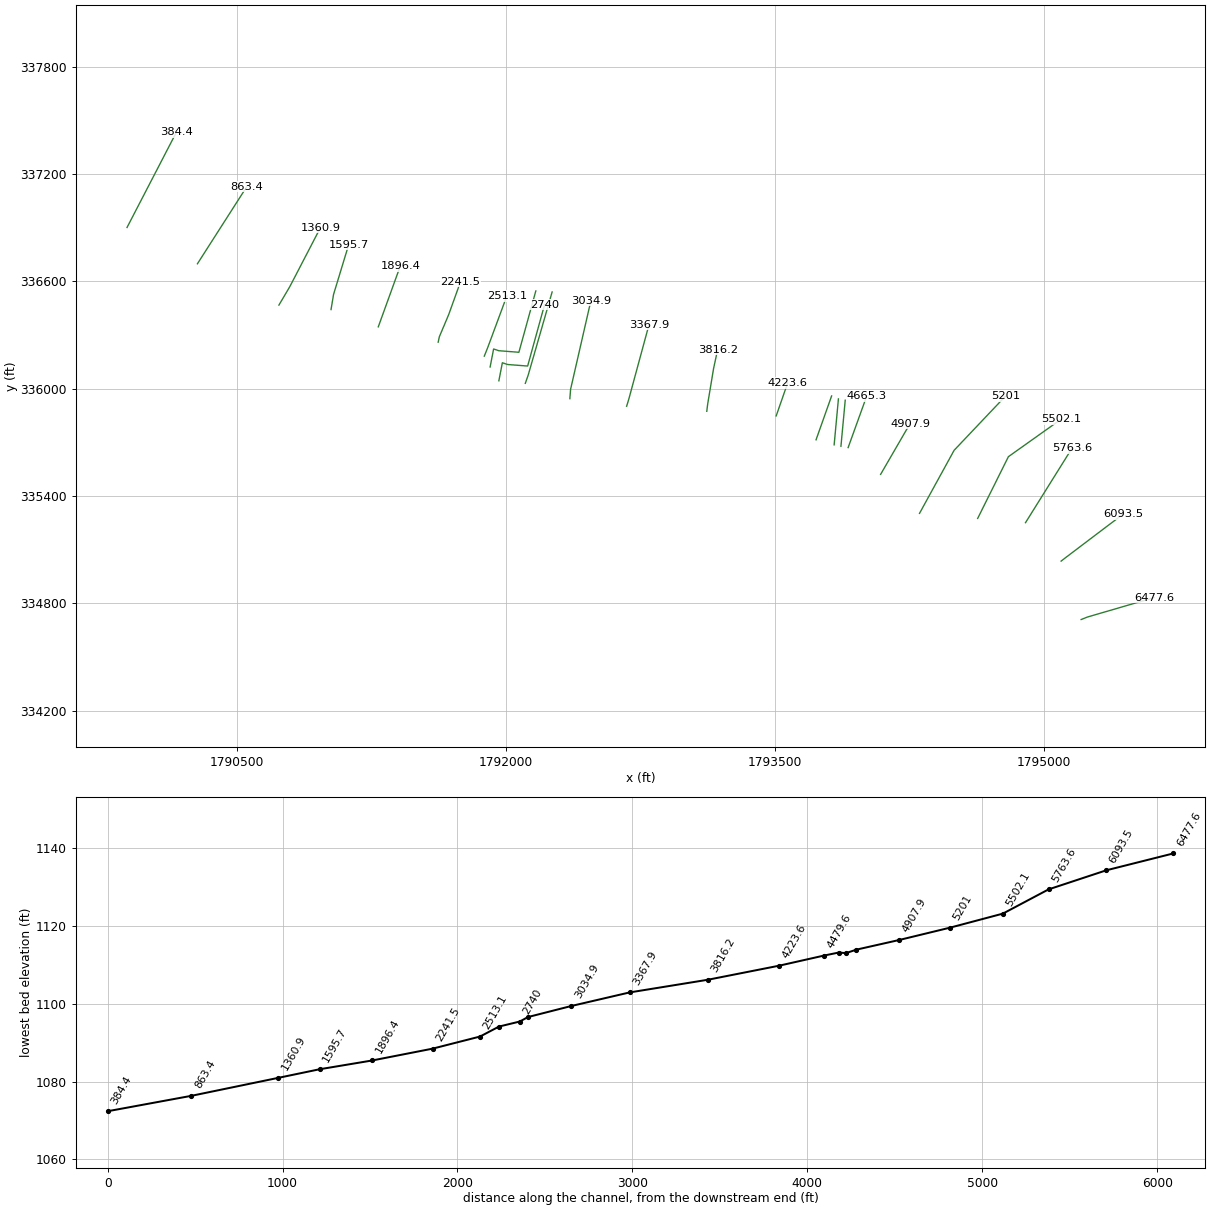
HEC-RAS study WESTFK1.prj: WESTFK1

--- WESTFK1.g01 (geometry) --- (continued)

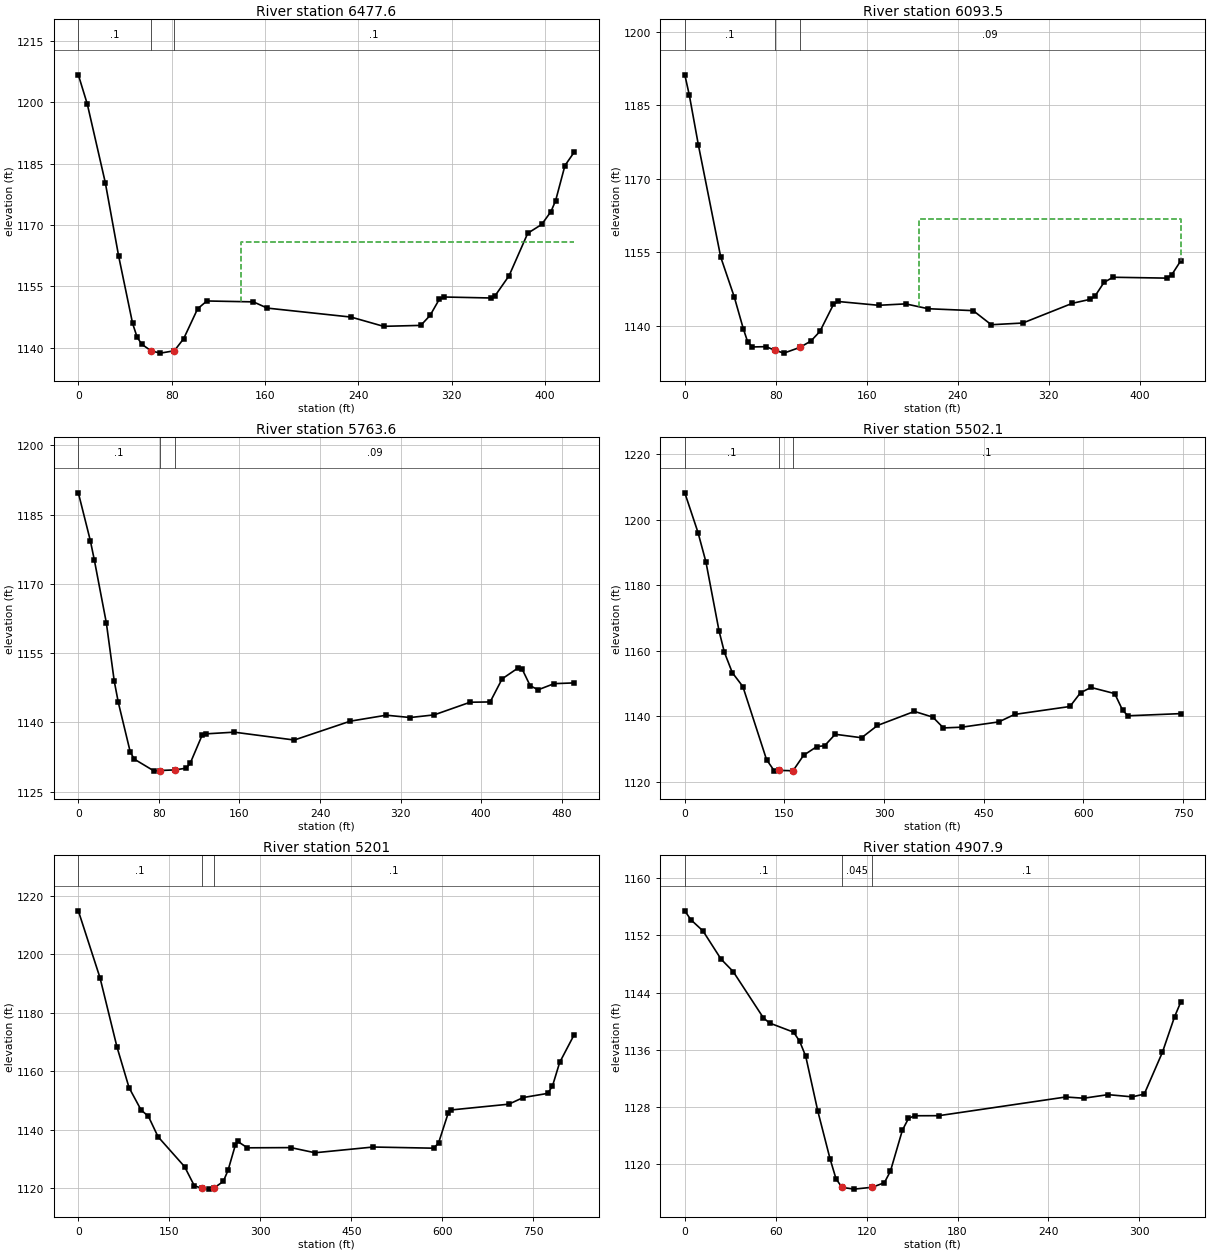
Type RM Length L Ch R = 1 ,6477.6  ,376,384,392.1
XS GIS Cut Line= 3
     1795209.871      334709.296     1795245.678      334723.402
     1795616.772      334831.909
#Sta/Elev= 30
       0 1206.66     7.7  1199.5    23.1 1180.37    34.6 1162.36    46.5 1146.01
    50.4 1142.62    54.4 1140.91    62.4 1139.27    70.4 1138.73    82.3 1139.31
    90.3 1142.25   102.3 1149.56   110.2 1151.46   150.1 1151.24     162 1149.72
   233.8 1147.53   261.7 1145.27   293.6  1145.5   301.6 1147.94   309.5 1151.89
   313.5 1152.43   353.4 1152.19   357.4 1152.77   369.3 1157.62   385.3 1167.99
   397.2 1170.13   405.2 1173.27   409.2 1175.95   417.2 1184.52   425.1 1187.77
#Mann= 3 , 0 , 0
       0      .1       0    62.4    .045       0    82.3      .1       0
#XS Ineff= 2 , 0
                          139.06         1165.82
Permanent Ineff=
       F       F
Bank Sta=62.4,82.3
XS Rating Curve= 0 ,0
Exp/Cntr=0.3,0.1

Type RM Length L Ch R = 1 ,6093.5  ,321.5,330,338.2
XS GIS Cut Line= 3
     1795098.109      335035.902     1795126.321      335057.603
     1795445.331      335299.574
#Sta/Elev= 30
       0 1191.23       4 1187.06    11.9 1176.95    31.6 1153.99    43.5 1145.86
    51.4  1139.4    55.4  1136.6    59.4 1135.64    71.3  1135.7    79.2 1134.98
    87.1 1134.38   101.2 1135.55   110.9 1136.85   118.8 1138.81   130.7 1144.32
   134.7 1144.93   170.4 1144.15   194.2 1144.44     214 1143.45   253.6 1143.06
   269.5 1140.18   297.2 1140.53   340.8 1144.56   356.7 1145.38   360.7 1146.02
   368.6 1148.82   376.5 1149.88   424.1  1149.7   428.1 1150.35     436  1153.2
#Mann= 3 , 0 , 0
       0      .1       0    79.2    .045       0   101.2     .09       0
#XS Ineff= 2 , 0
                          206.38         1161.88
Permanent Ineff=
       F       F
Bank Sta=79.2,101.2
XS Rating Curve= 0 ,0
Exp/Cntr=0.3,0.1

Type RM Length L Ch R = 1 ,5763.6  ,259,261.4,263.3
XS GIS Cut Line= 2
     1794899.541      335250.746     1795159.958      335668.498
#Sta/Elev= 30
       0 1189.69    11.9 1179.36    15.9 1175.14    27.8 1161.56    35.7 1148.89
    39.7 1144.33    51.6 1133.57    55.6 1132.06    75.4 1129.47      81  1129.6
      96 1129.74   107.2 1130.11   111.2 1131.23   123.1 1137.34     127 1137.54
   154.8  1137.9   214.4  1136.2     270 1140.28   305.7 1141.57   329.5 1141.07
   353.3 1141.64     389 1144.38   408.9 1144.44   420.8 1149.44   436.7  1151.8
   440.7 1151.53   448.6 1147.96   456.5 1147.07   472.4  1148.4   492.3 1148.56
#Mann= 3 , 0 , 0
       0      .1       0      81    .045       0      96     .09       0
Bank Sta=81,96
XS Rating Curve= 0 ,0
Exp/Cntr=0.3,0.1

Type RM Length L Ch R = 1 ,5502.1  ,302.3,301.1,299.6
XS GIS Cut Line= 3
     1794632.614      335274.617     1794804.055      335619.669
     1795098.109      335829.088
#Sta/Elev= 30
       0 1208.27    19.9 1196.13    31.8 1187.15    51.6 1166.02    59.6 1159.54
    71.5 1153.32    87.4 1149.07   123.1 1126.71     135 1123.23   141.7 1123.45
   162.9 1123.35   178.8 1128.07   198.6 1130.71   210.5    1131   226.4 1134.49
   266.1 1133.43     290 1137.18   345.6 1141.48   373.4 1139.72   389.3 1136.43
     417 1136.66   472.6 1138.27   496.4 1140.56   579.7 1142.98   595.6 1147.18
   611.4  1148.8   647.1 1146.92     659 1141.83     667 1140.14   746.3  1140.8
#Mann= 3 , 0 , 0
       0      .1       0   141.7    .045       0   162.9      .1       0
Bank Sta=141.7,162.9
XS Rating Curve= 0 ,0
Exp/Cntr=0.3,0.1

Type RM Length L Ch R = 1 ,5201    ,293.5,293.1,293.2
XS GIS Cut Line= 3
     1794308.178      335302.829     1794501.321      335655.477
     1794786.694      335957.126
#Sta/Elev= 30
       0 1214.81    35.8 1191.86    63.7 1168.25    83.6 1154.34   103.5 1146.66
   115.4 1144.57   131.4 1137.54   175.2  1127.3   191.1 1120.82   203.2 1119.91
     215 1119.63   222.9 1119.93   238.9 1122.24   246.8 1126.09   258.8 1134.69
   262.7 1135.94   278.7 1133.76   350.3 1133.83   390.1 1132.07   485.9 1134.03
   585.7 1133.63   593.7 1135.38   609.7 1145.65   613.7 1146.69   709.5 1148.68
   733.5 1150.96   773.4 1152.36   781.4 1154.78   793.4 1162.95   817.3 1172.43
#Mann= 3 , 0 , 0
       0      .1       0   203.2    .045       0   222.9      .1       0
Bank Sta=203.2,222.9
XS Rating Curve= 0 ,0
Exp/Cntr=0.3,0.1

Type RM Length L Ch R = 1 ,4907.9  ,238.5,242.5,246.6
XS GIS Cut Line= 2
     1794091.165      335520.928      1794255.01      335804.131
#Sta/Elev= 30
       0 1155.46       4 1154.21      12 1152.64    23.9 1148.69    31.9 1146.95
    51.9 1140.44    55.9 1139.73    71.8 1138.44    75.8 1137.17    79.8 1135.06
    87.8 1127.35    95.8 1120.72    99.8 1117.87   103.7 1116.68   111.7 1116.43
   123.7 1116.69   131.7 1117.33   135.7 1118.95   143.6  1124.7   147.6 1126.34
   151.6 1126.72   167.6 1126.73   251.4 1129.35   263.3 1129.18   279.3 1129.68
   295.3 1129.37   303.2 1129.76   315.2 1135.63   323.2  1140.6   327.2 1142.62
#Mann= 3 , 0 , 0
       0      .1       0   103.7    .045       0   123.7      .1       0
Bank Sta=103.7,123.7
XS Rating Curve= 0 ,0
Exp/Cntr=0.3,0.1

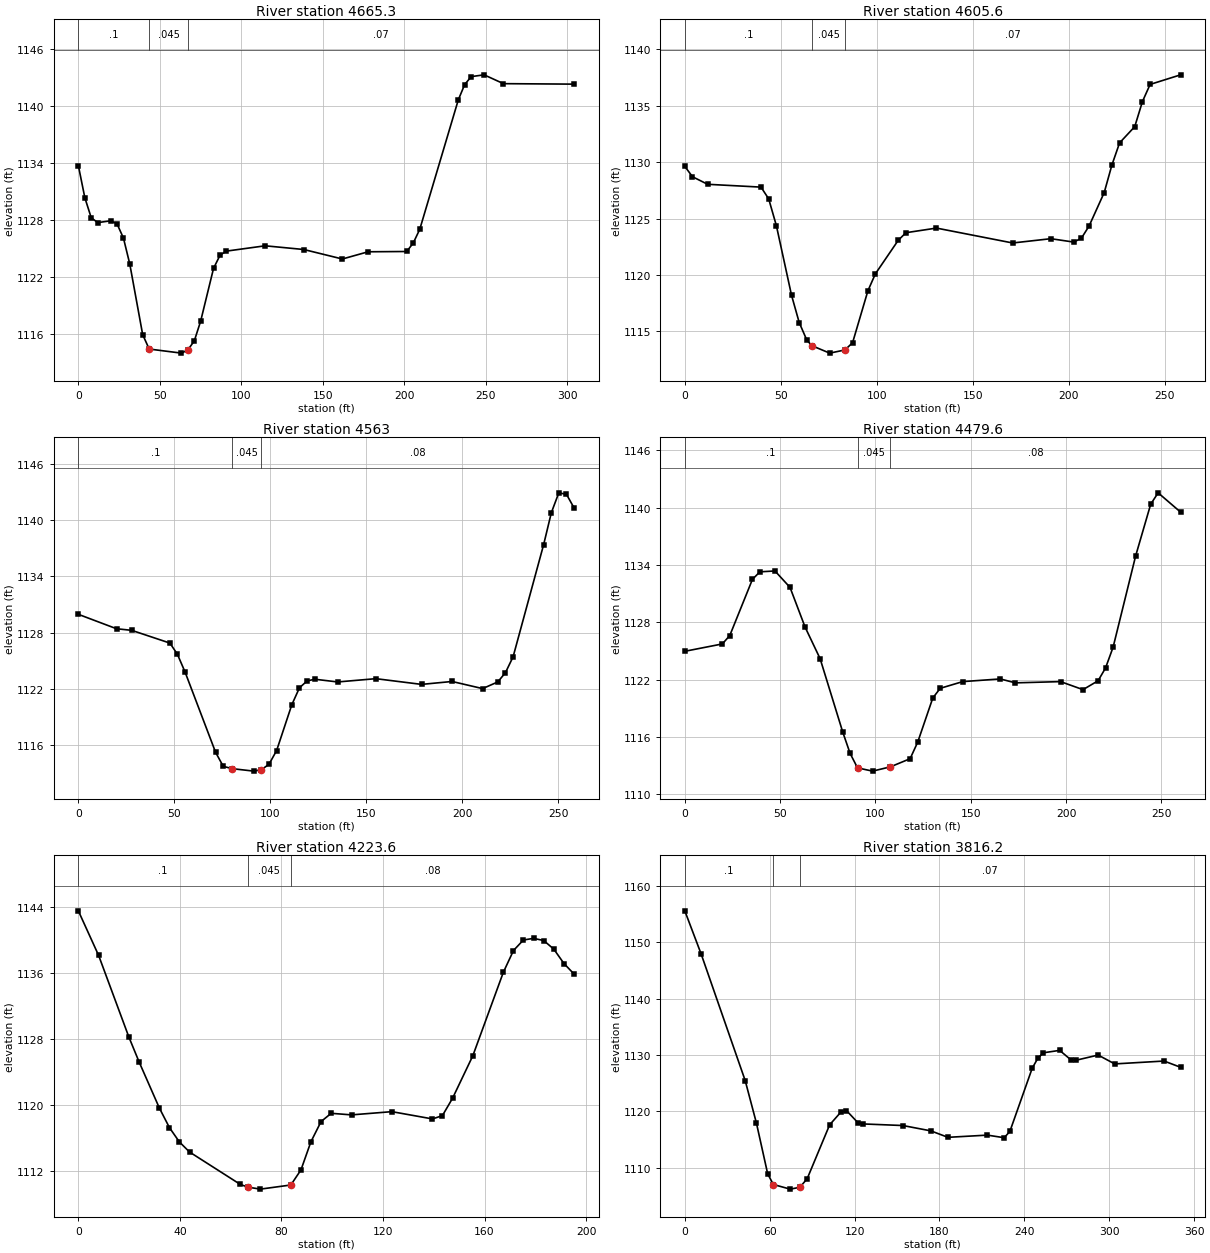
Type RM Length L Ch R = 1 ,4665.3  ,53.4,59.7,66.1
XS GIS Cut Line= 2
     1793909.958      335670.668      1794013.04      335957.126
#Sta/Elev= 30
       0 1133.72       4 1130.33     7.9 1128.23    11.9 1127.71    19.8  1127.9
    23.7  1127.6    27.7 1126.08    31.6 1123.34    39.5 1115.92    43.5  1114.4
    63.3 1113.97    67.2  1114.3    71.2 1115.26    75.1 1117.34      83 1122.89
      87 1124.28    90.9 1124.71   114.7 1125.27   138.4 1124.88   162.1 1123.88
   177.9 1124.64   201.6 1124.67   205.6 1125.56   209.6    1127   233.3 1140.65
   237.2 1142.25   241.2 1143.08   249.1 1143.27     261 1142.34   304.4 1142.29
#Mann= 3 , 0 , 0
       0      .1       0    43.5    .045       0    67.2     .07       0
Bank Sta=43.5,67.2
XS Rating Curve= 0 ,0
Exp/Cntr=0.3,0.1

Type RM Length L Ch R = 1 ,4605.6  ,42.6,42.6,42.2
XS GIS Cut Line= 2
      1793869.81      335678.263     1793893.682      335935.425
#Sta/Elev= 30
       0 1129.63       4 1128.71    11.9 1128.04    39.7 1127.79    43.7 1126.75
    47.7 1124.38    55.6 1118.21    59.6 1115.79    63.6 1114.22    66.3 1113.73
    75.5 1113.08    83.4 1113.36    87.4    1114    95.4 1118.61    99.3 1120.11
   111.2 1123.08   115.2 1123.75   131.1 1124.16   170.8 1122.84   190.7 1123.22
   202.6 1122.92   206.6 1123.26   210.6 1124.34   218.5 1127.31   222.5 1129.75
   226.5 1131.71   234.4 1133.15   238.4 1135.37   242.4 1136.89   258.3 1137.74
#Mann= 3 , 0 , 0
       0      .1       0    66.3    .045       0    83.4     .07       0
Bank Sta=66.3,83.4
XS Rating Curve= 0 ,0
Exp/Cntr=0.3,0.1

Type RM Length L Ch R = 1 ,4563    ,89.6,83.4,77.5
XS GIS Cut Line= 2
     1793831.833      335685.859     1793855.704       335943.02
#Sta/Elev= 30
       0 1129.95    19.9 1128.41    27.8 1128.24    47.7 1126.88    51.6 1125.69
    55.6 1123.79    71.5 1115.22    75.5 1113.72    80.3 1113.47    91.4 1113.21
    95.3 1113.36    99.3 1113.93   103.3 1115.41   111.2 1120.29   115.2 1122.11
   119.2 1122.84   123.2 1123.02   135.1 1122.73     155 1123.08   178.8 1122.47
   194.7 1122.78   210.6 1122.02   218.5 1122.73   222.5 1123.72   226.5 1125.42
   242.4 1137.39   246.4 1140.79   250.3 1142.92   254.3 1142.76   258.3 1141.29
#Mann= 3 , 0 , 0
       0      .1       0    80.3    .045       0    95.3     .08       0
Bank Sta=80.3,95.3
XS Rating Curve= 0 ,0
Exp/Cntr=0.3,0.1

Type RM Length L Ch R = 1 ,4479.6  ,255.8,256,256
XS GIS Cut Line= 2
     1793730.921       335714.07     1793817.727      335959.296
#Sta/Elev= 30
       0 1124.97    19.7 1125.74    23.6 1126.62    35.5  1132.5    39.4 1133.28
    47.3 1133.37    55.2 1131.65    63.1  1127.5      71 1124.19    82.8 1116.56
    86.7  1114.3    90.6 1112.78    98.5 1112.44   107.9 1112.89   118.2 1113.74
   122.2 1115.48   130.1 1120.09     134  1121.1   145.8  1121.8   165.5 1122.08
   173.4 1121.67   197.1  1121.8   208.9 1120.96   216.8 1121.89   220.7 1123.22
   224.7 1125.41   236.5 1134.94   244.4 1140.35   248.3 1141.54   260.1 1139.52
#Mann= 3 , 0 , 0
       0      .1       0    90.6    .045       0   107.9     .08       0
Bank Sta=90.6,107.9
XS Rating Curve= 0 ,0
Exp/Cntr=0.3,0.1

Type RM Length L Ch R = 1 ,4223.6  ,403.3,407.4,411
XS GIS Cut Line= 2
     1793508.482      335847.534     1793572.501      336031.996
#Sta/Elev= 30
       0  1143.5       8  1138.1    19.9 1128.24    23.9 1125.25    31.9 1119.66
    35.9 1117.27    39.8 1115.55    43.8 1114.33    63.8 1110.41    66.8 1110.08
    71.7 1109.84    83.7 1110.34    87.7 1112.17    91.6 1115.56    95.6 1118.01
    99.6 1119.01   107.6 1118.82   123.5 1119.21   139.5 1118.33   143.4 1118.73
   147.4 1120.83   155.4 1125.98   167.4 1136.06   171.4  1138.7   175.3 1139.97
   179.3 1140.17   183.3 1139.91   187.3 1138.86   191.3 1137.12   195.3 1135.84
#Mann= 3 , 0 , 0
       0      .1       0    66.8    .045       0    83.7     .08       0
Bank Sta=66.8,83.7
XS Rating Curve= 0 ,0
Exp/Cntr=0.3,0.1

Type RM Length L Ch R = 1 ,3816.2  ,449.5,448.3,444.9
XS GIS Cut Line= 4
     1793121.112      335873.576     1793126.538      335915.893
      1793159.09      336112.291     1793181.876      336218.628
#Sta/Elev= 30
       0 1155.54    11.6 1147.86    42.7 1125.45    50.6 1117.96    58.6 1108.92
    62.6 1107.04    74.5 1106.22    81.3 1106.54    86.5 1108.06   102.4 1117.62
   110.4 1119.89   114.3 1120.14   122.3 1118.01   126.3 1117.77   154.2 1117.49
     174 1116.54     186  1115.4   213.9 1115.79   225.8 1115.33   229.8 1116.45
   245.6 1127.66   249.5 1129.38   253.4 1130.38     265 1130.81   272.8 1129.16
   276.7 1129.07   292.2 1129.98   303.9 1128.41   338.8 1128.92   350.5 1127.81
#Mann= 3 , 0 , 0
       0      .1       0    62.6    .045       0    81.3     .07       0
Bank Sta=62.6,81.3
XS Rating Curve= 0 ,0
Exp/Cntr=0.3,0.1

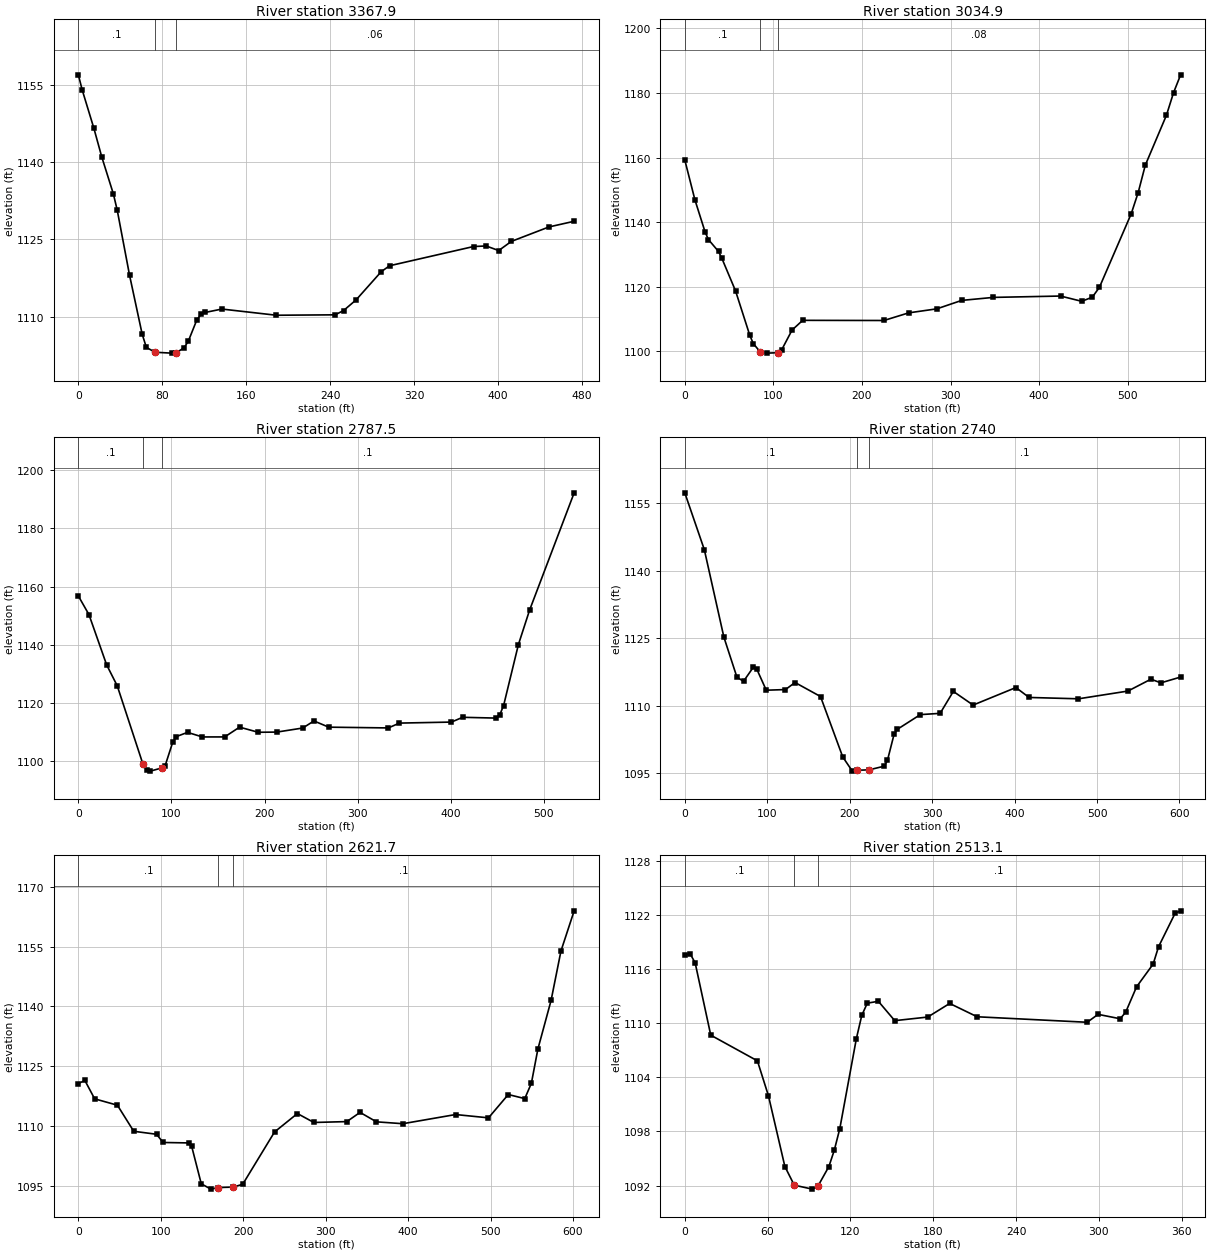
Type RM Length L Ch R = 1 ,3367.9  ,332,333,333.8
XS GIS Cut Line= 3
     1792674.064      335901.787        1792686.       335940.85
     1792798.847      336357.517
#Sta/Elev= 30
       0 1156.94     3.7    1154    14.8 1146.58    22.3 1141.03    33.4 1133.83
    37.1 1130.65    48.8 1118.07    60.8 1106.66    64.8 1104.07    73.1 1103.12
    88.8 1102.95    92.8 1102.95   100.8    1104   104.8 1105.27   112.8 1109.33
   116.8 1110.48   120.8 1110.84   136.8  1111.5   188.7  1110.3   244.7 1110.38
   252.7  1111.2   264.7 1113.28   288.7 1118.76   296.6  1119.9   376.6 1123.63
   388.6 1123.74   400.6 1122.85   412.6 1124.62   448.5 1127.43   472.5 1128.53
#Mann= 3 , 0 , 0
       0      .1       0    73.1    .045       0    92.8     .06       0
Bank Sta=73.1,92.8
XS Rating Curve= 0 ,0
Exp/Cntr=0.3,0.1

Type RM Length L Ch R = 1 ,3034.9  ,248.5,247.4,246
XS GIS Cut Line= 3
     1792357.224      335944.105     1792361.564      335997.274
     1792474.411       336490.98
#Sta/Elev= 30
       0 1159.24    11.4 1146.93    22.9 1136.96    26.7  1134.6    38.1 1130.92
    41.9 1128.77    57.3 1118.72    73.3 1105.04    77.3 1102.42      85 1099.89
    93.2 1099.46   105.2 1099.59   109.2 1100.39   121.1  1106.6   133.1 1109.61
   224.8 1109.56   252.7 1111.92   284.6 1113.17   312.6 1115.78   348.4 1116.71
   424.2 1117.13   448.1  1115.5   460.1 1116.78   468.1 1119.82     504 1142.58
   511.9 1149.17   519.9 1157.62   543.8  1173.1   551.8 1180.07   559.8  1185.6
#Mann= 3 , 0 , 0
       0      .1       0      85    .045       0   105.2     .08       0
Bank Sta=85,105.2
XS Rating Curve= 0 ,0
Exp/Cntr=0.3,0.1

Type RM Length L Ch R = 1 ,2787.5  ,86.6,47.5,17.1
XS GIS Cut Line= 3
     1792108.743      336029.826     1792125.019      336076.484
     1792258.482      336540.893
#Sta/Elev= 30
       0 1156.79    11.4  1150.4    30.4 1133.13    41.8 1125.92    69.4 1099.02
    73.4    1097    77.4 1096.62    89.5  1097.7    93.3 1098.55   101.3 1106.46
   105.3 1108.49   117.3 1109.93   133.3 1108.36   157.2 1108.37   173.2 1111.73
   193.2 1109.97   213.2 1110.03   241.1 1111.43   253.1 1113.86     269 1111.72
     333 1111.46   344.9 1113.12   400.8 1113.47   412.8 1115.11   448.8 1114.84
   452.8 1116.05   456.8 1119.14   472.7 1140.08   484.7 1151.91   532.6 1192.22
#Mann= 3 , 0 , 0
       0      .1       0    69.4    .045       0    89.5      .1       0
Bank Sta=69.4,89.5
XS Rating Curve= 0 ,0
Exp/Cntr=0.3,0.1

Type RM Length L Ch R = 1 ,2740    ,149.7,118.3,109.5
XS GIS Cut Line= 5
     1791961.173      336043.932     1791980.704      336144.843
     1792010.001      336135.077     1792121.763      336126.397
     1792216.165      336469.279
#Sta/Elev= 30
       0 1157.26    23.7 1144.63    47.4 1125.22    63.2 1116.34    71.2  1115.4
      83  1118.5      87 1118.24    98.8 1113.43   122.1 1113.57   133.7 1115.14
   164.6 1112.03   191.6  1098.6   203.2 1095.46   208.4 1095.65   223.4 1095.74
   241.9 1096.56   245.8 1097.85   253.8 1103.62   257.8 1104.75   285.7 1108.01
   309.7 1108.29   325.7 1113.16   349.7 1110.13   401.6 1114.02   417.6 1111.82
   477.5 1111.52   537.5 1113.24   565.4 1115.88   577.4 1115.06   601.4 1116.35
#Mann= 3 , 0 , 0
       0      .1       0   208.4    .045       0   223.4      .1       0
Bank Sta=208.4,223.4
XS Rating Curve= 0 ,0
Exp/Cntr=0.3,0.1

Type RM Length L Ch R = 1 ,2621.7  ,39.3,108.6,145.6
XS GIS Cut Line= 5
     1791912.345      336120.971     1791931.876      336221.883
     1791961.173      336212.117     1792072.935      336203.437
     1792167.336      336546.319
#Sta/Elev= 30
       0 1120.64     7.9 1121.44    19.8 1116.82    47.4 1115.22    67.2 1108.68
    94.9 1107.93   102.8 1105.87   133.7 1105.76   137.5 1104.89   149.1 1095.52
   160.7 1094.17   169.9 1094.57   187.8 1094.68   199.4 1095.39     238 1108.51
   265.7 1113.13   285.7 1110.89   325.7 1111.11   341.7 1113.42   361.6 1111.05
   393.6 1110.58   457.6 1112.88   497.5 1112.05   521.5  1117.9   541.5 1116.88
   549.5 1120.72   557.4  1129.3   573.4  1141.5   585.4 1153.91   601.4 1163.98
#Mann= 3 , 0 , 0
       0      .1       0   169.9    .045       0   187.8      .1       0
Bank Sta=169.9,187.8
XS Rating Curve= 0 ,0
Exp/Cntr=0.3,0.1

Type RM Length L Ch R = 1 ,2513.1  ,272.7,271.6,270.6
XS GIS Cut Line= 3
     1791879.793      336181.735     1791899.324      336230.563
     1792005.661      336518.107
#Sta/Elev= 30
       0 1117.56     3.8 1117.74     7.5 1116.72    18.8 1108.69    52.6 1105.84
    60.6 1101.96    72.5 1094.11    79.3 1092.04    92.4  1091.6    96.4 1091.92
   104.4 1094.11   108.3 1095.92   112.3 1098.32   124.3 1108.31   128.2 1110.88
   132.2 1112.24   140.2 1112.45   152.1  1110.3     176  1110.7   191.9 1112.21
   211.8 1110.73   291.5 1110.12   299.4    1111   315.4 1110.51   319.4 1111.24
   327.3 1114.06   339.3 1116.58   343.2  1118.5   355.2 1122.22   359.2 1122.49
#Mann= 3 , 0 , 0
       0      .1       0    79.3    .045       0    96.4      .1       0
Bank Sta=79.3,96.4
XS Rating Curve= 0 ,0
Exp/Cntr=0.3,0.1

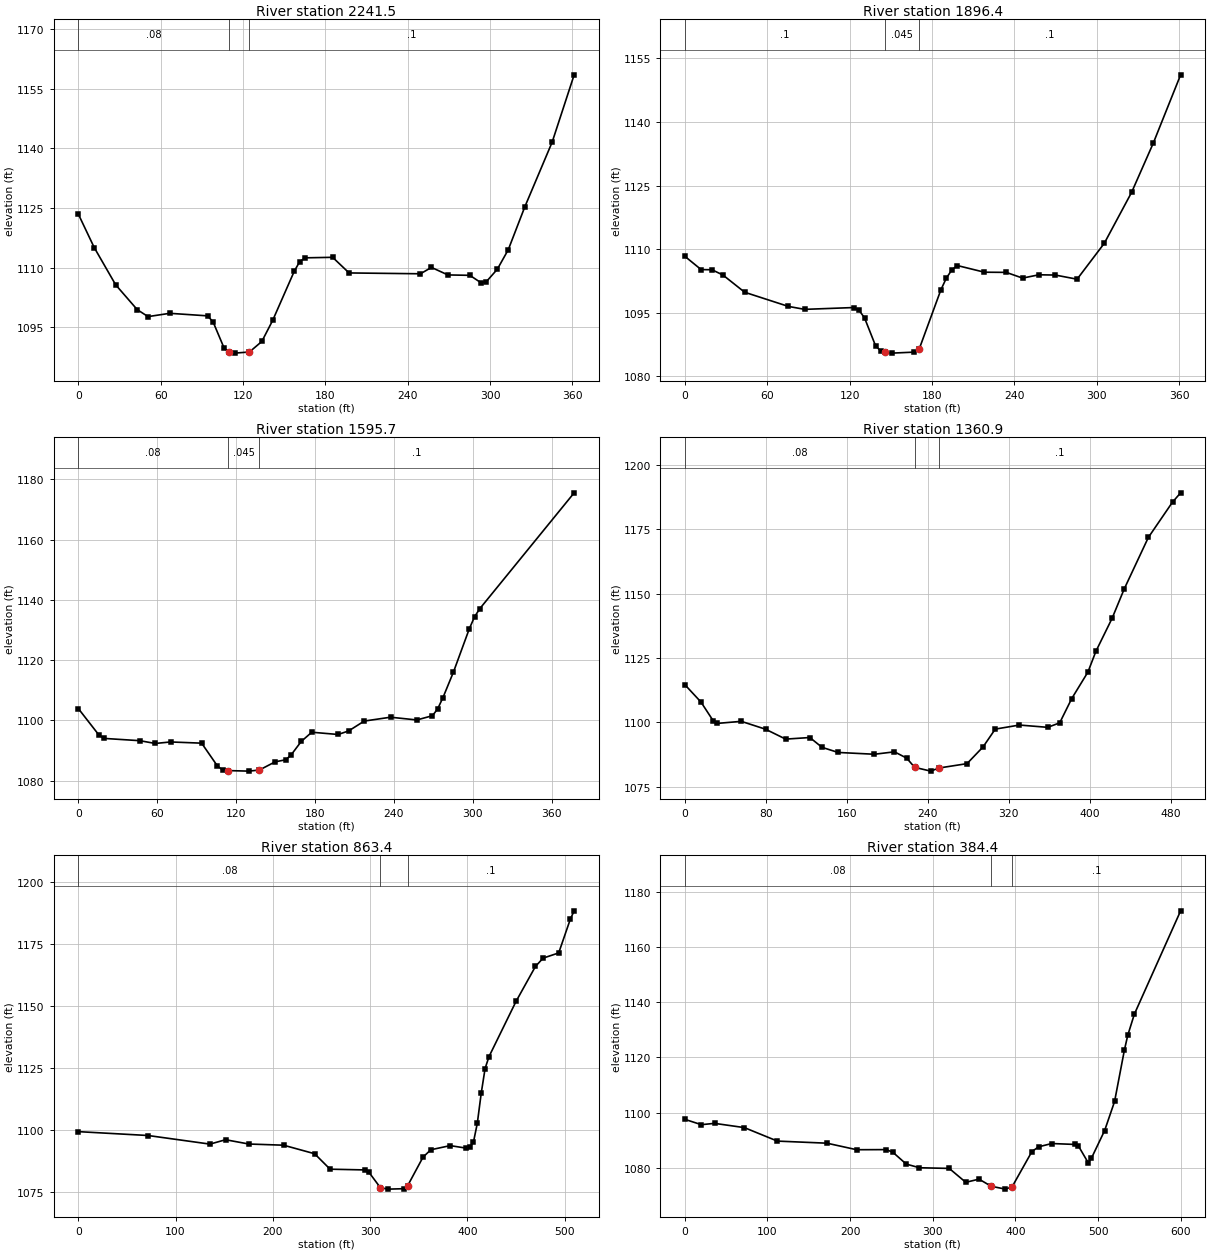
Type RM Length L Ch R = 1 ,2241.5  ,343.5,345.1,345.8
XS GIS Cut Line= 4
     1791622.632       336259.86     1791629.142      336290.242
     1791681.225       336413.94     1791747.415      336598.402
#Sta/Elev= 30
       0 1123.43    11.6 1115.01    27.2 1105.66    42.9 1099.42    50.8 1097.66
    66.6 1098.49    94.2 1097.85    98.2 1096.32   106.1 1089.85   109.7 1088.69
     114 1088.48   124.7 1088.77   133.7 1091.41   141.6  1096.7   157.4 1109.11
   161.3 1111.47   165.3 1112.44   185.3 1112.57   197.3 1108.64   249.3 1108.43
   257.3 1110.03   269.3 1108.14   285.3 1108.04   293.3  1106.2   297.3 1106.44
   305.3 1109.57   313.3 1114.49   325.3 1125.22   345.3 1141.56   361.3 1158.45
#Mann= 3 , 0 , 0
       0     .08       0   109.7    .045       0   124.7      .1       0
Bank Sta=109.7,124.7
XS Rating Curve= 0 ,0
Exp/Cntr=0.3,0.1

Type RM Length L Ch R = 1 ,1896.4  ,299.2,300.8,301.6
XS GIS Cut Line= 2
      1791288.43      336345.581     1791411.043      336685.208
#Sta/Elev= 30
       0  1108.3    11.9 1105.16    19.8 1105.12    27.8 1103.87    43.6 1099.81
    75.4 1096.47    87.3 1095.77     123  1096.2     127 1095.52   130.9 1093.76
   138.9  1087.2   142.8 1085.89   145.5 1085.65   150.8 1085.44   166.6 1085.67
   170.6 1086.31   186.5 1100.38   190.5 1103.16   194.4 1105.04   198.4 1106.12
   218.2 1104.54   234.1  1104.5     246 1103.15   257.9 1103.93   269.8 1103.87
   285.7 1102.89   305.5 1111.36   325.4 1123.39   341.2 1135.02   361.1 1151.13
#Mann= 3 , 0 , 0
       0      .1       0   145.5    .045       0   170.6      .1       0
Bank Sta=145.5,170.6
XS Rating Curve= 0 ,0
Exp/Cntr=0.3,0.1

Type RM Length L Ch R = 1 ,1595.7  ,237.6,234.8,229.9
XS GIS Cut Line= 3
     1791024.758      336442.152     1791038.864      336526.787
       1791123.5       336805.65
#Sta/Elev= 30
       0 1103.94    15.6  1095.2    19.5 1094.04    46.8 1093.28    58.5 1092.36
    70.2 1092.86    93.8 1092.46   105.8  1084.9   109.8 1083.55   113.8 1083.36
   129.7 1083.18   137.7 1083.54   149.7 1086.26   157.7 1086.94   161.6  1088.4
   169.6 1093.04   177.6 1096.09   197.6 1095.34   205.6 1096.51   217.5 1099.79
   237.5 1101.07   257.5 1100.16   269.4 1101.57   273.4 1103.87   277.4 1107.59
   285.4 1116.09   297.4 1130.38   301.4 1134.37   305.4 1137.08   377.2 1175.53
#Mann= 3 , 0 , 0
       0     .08       0   113.8    .045       0   137.7      .1       0
Bank Sta=113.8,137.7
XS Rating Curve= 0 ,0
Exp/Cntr=0.3,0.1

Type RM Length L Ch R = 1 ,1360.9  ,500.1,497.5,495.4
XS GIS Cut Line= 3
      1790733.96      336467.109     1790794.724       336570.19
     1790965.079      336898.966
#Sta/Elev= 30
       0  1114.6      16 1107.82    27.9 1100.65    31.9 1099.52    55.8 1100.33
    79.8 1097.27    99.7 1093.42   123.6 1094.04   135.6 1090.23   151.5 1088.24
   187.4 1087.54   207.2 1088.48   219.2 1086.05   227.2 1082.44   243.1 1080.98
     251 1082.18   278.9 1083.89   294.8 1090.41   306.8 1097.31   330.7 1098.89
   358.6    1098   370.5 1099.74   382.4 1109.19   398.4 1119.49   406.3 1127.57
   422.3 1140.39   434.2 1151.73   458.1  1171.8     482 1185.54     490 1189.14
#Mann= 3 , 0 , 0
       0     .08       0   227.2    .045       0     251      .1       0
Bank Sta=227.2,251
XS Rating Curve= 0 ,0
Exp/Cntr=0.3,0.1

Type RM Length L Ch R = 1 ,863.4   ,475.4,479,480.4
XS GIS Cut Line= 2
     1790279.316      336698.228     1790553.838      337127.916
#Sta/Elev= 30
       0 1099.53    71.7 1097.97   135.4  1094.5   151.4 1096.27   175.3 1094.54
   211.1 1094.06     243 1090.62   258.9 1084.39   294.8 1084.09   298.8 1083.18
   310.7 1076.89   318.7 1076.35   334.6 1076.52   338.6 1077.67   354.5 1089.26
   362.5 1092.22   382.4 1093.89   398.4 1092.91   402.3 1093.26   406.3 1095.25
   410.3 1102.89   414.3 1114.96   418.3 1124.98   422.3 1129.76   450.1 1152.02
   470.1 1166.14     478  1169.5     494 1171.58   505.9 1185.13   509.9 1188.56
#Mann= 3 , 0 , 0
       0     .08       0   310.7    .045       0   338.6      .1       0
Bank Sta=310.7,338.6
XS Rating Curve= 0 ,0
Exp/Cntr=0.3,0.1

Type RM Length L Ch R = 1 ,384.4   ,314,314.3,315
XS GIS Cut Line= 2
      1789886.52      336901.136     1790162.128      337433.905
#Sta/Elev= 30
       0 1097.62      20 1095.69      36 1096.16      72 1094.63     112 1089.75
     172 1088.99   207.9 1086.63   243.9 1086.67   251.9 1085.66   267.9 1081.43
   283.9 1080.11   319.9 1079.87   339.9 1074.84   355.9 1075.99   370.7 1073.41
   387.9 1072.38   395.9  1073.2   419.9 1085.96   427.9 1087.67   443.9 1088.87
   471.9 1088.54   475.9 1088.12   487.9 1081.98   491.9 1083.56   507.9 1093.58
   519.9 1104.07   531.8  1122.7   535.8 1127.95   543.8 1135.63   599.8 1173.02
#Mann= 3 , 0 , 0
       0     .08       0   370.7    .045       0   395.9      .1       0
Bank Sta=370.7,395.9
XS Rating Curve= 0 ,0
Exp/Cntr=0.3,0.1