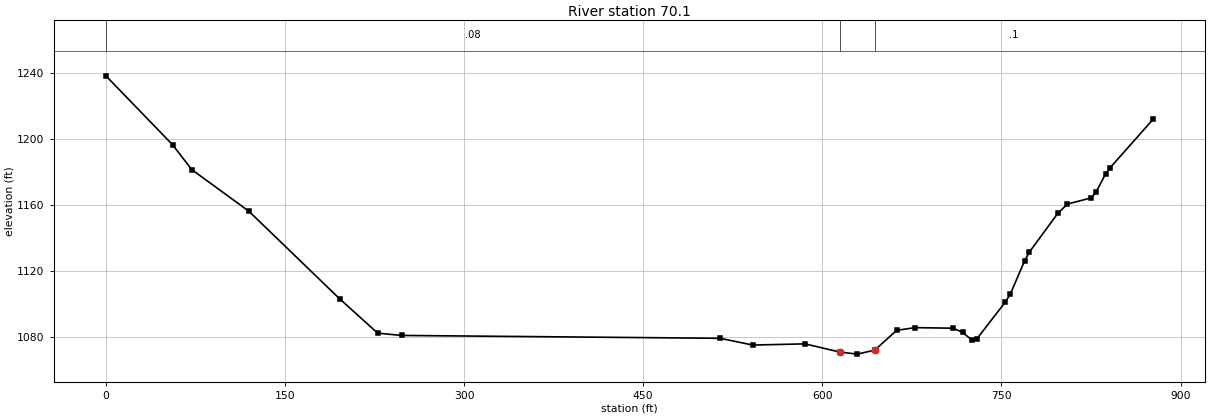
HEC-RAS study WESTFK1.prj: WESTFK1

--- WESTFK1.g01 (geometry) --- (continued)

Type RM Length L Ch R = 1 ,70.1    ,68.2,70.1,72
XS GIS Cut Line= 6
     1789527.178      336829.674     1789733.088      337266.851
     1789761.346      337326.845     1789784.329      337375.643
     1789812.507      337435.467     1789900.886       337623.11
#Sta/Elev= 30
       0 1238.37    55.9 1196.46    71.9 1181.44   119.8 1156.11   195.7    1103
   227.6 1082.13   247.6 1080.73   514.4 1078.99   541.8 1074.88   585.4 1075.61
   614.5 1070.68   629.2 1069.38   643.9  1071.8   662.3 1083.83   677.7 1085.47
   709.6 1085.12   717.5 1082.58   725.5 1077.81   729.5 1078.71   753.4 1101.13
   757.4 1105.76   769.4 1126.01   773.4 1131.35   797.3 1154.94   805.3 1160.51
   825.2 1164.25   829.2 1167.67   837.2  1178.8   841.2 1182.69     877 1211.96
#Mann= 3 , 0 , 0
       0     .08       0   614.5    .045       0   643.9      .1       0
Bank Sta=614.5,643.9
XS Rating Curve= 0 ,0
Exp/Cntr=0.3,0.1

Chan Stop Cuts=-1
Use User Specified Reach Order=0
Composite Channel Slope=5